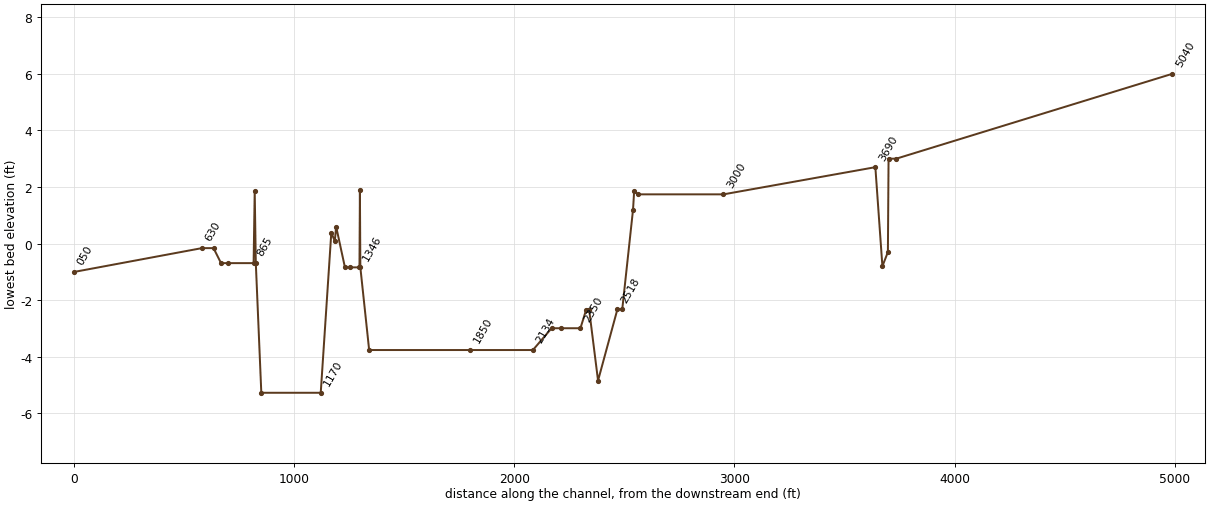
--- kick96ex.prj (project) ---

Proj Title=Kickapoo Creek 1996 Existing
Current Plan=p01
Default Exp/Contr=0.3,0.1
English Units
Geom File=g01
Geom File=g02
Flow File=f03
Flow File=f01
Flow File=f02
Plan File=p02
Plan File=p01
Plan File=p03
Plan File=p04

--- kick96ex.p01 (plan) ---

Plan Title=Kickapoo Creek Existing 96
Short Identifier=Kickex 1
Geom File=g01
Flow File=f03
Multiple Comp Mode
Subcritical Flow
K Sum by GR= 0
Std Step Tol= .01
Critical Tol= .01
Num of Std Step Trials= 20
Max Error Tol= .3
Flow Tol Ratio= .001
Log Output Level= 0
Friction Slope Method= 0
Multiple Critical Depth

--- kick96ex.f03 (steady flow) ---

Flow Title=Kickapoo Creek 120 csm
Number of Flows and Profiles and Boundary= 4, 4, 1
Rch & RM=K1          ,5040
       7      18      45      59
Rch & RM=K1          ,3690
       7      18      45      59
Rch & RM=K1          ,3000
      17      46     115     150
Rch & RM=K1          ,050
      17      46     115     150
Boundary for Rch & Prof#=K1          , 1
Up Type= 0
Up Value=0
Dn Type= 1
Dn Value=2.5
Boundary for Rch & Prof#=K1          , 2
Up Type= 0
Up Value=0
Dn Type= 1
Dn Value=2.5
Boundary for Rch & Prof#=K1          , 3
Up Type= 0
Up Value=0
Dn Type= 1
Dn Value=2.5
Boundary for Rch & Prof#=K1          , 4
Up Type= 0
Up Value=0
Dn Type= 1
Dn Value=2.5

--- kick96ex.g01 (geometry) ---

Geom Title=Kickapoo Creek 1996 Exist. JEI Sections
ViewRect= 0, 1, 1, 0
Reach=K1
Rch X Y Up & X Y Dn=0.4111776,0.951965,0.4111776,0.0480349
Rch Arrow X Y Up & X Y Dn=0,0,0,0
Rch Type=0

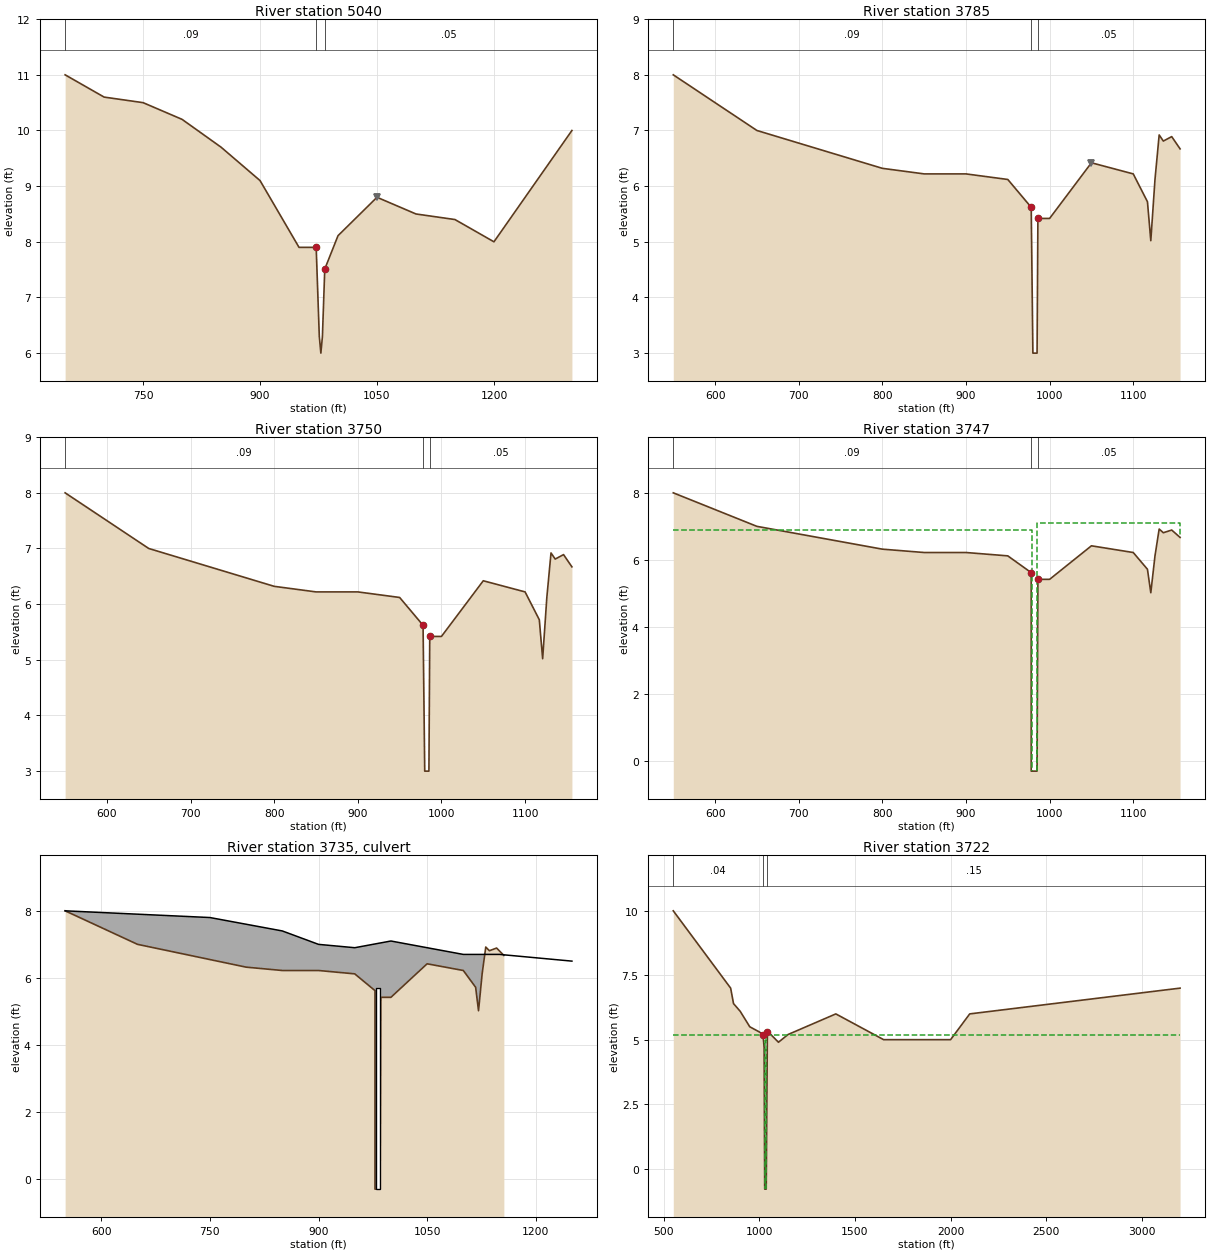
Type RM Length L Ch R =1,5040    ,1255,1255,1255,0,0,0
#Sta/Elev= 18
     650      11     700    10.6     750    10.5     800    10.2     850     9.7
     900     9.1     950     7.9     972     7.9     976     6.3     978       6
     980     6.3     983    7.51    1000    8.11    1050     8.8    1100     8.5
    1150     8.4    1200       8    1300      10
#Mann=3,0
     650     .09       0     972     .07       0     983     .05       0
Levee=0,,,-1,1050,8.8
Bank Sta=972,983
Exp/Cntr=0.3,0.1

Type RM Length L Ch R =1,3785    ,35,35,35,0,0,0
#Sta/Elev= 21
     550       8     650       7     800    6.32     850    6.22     900    6.22
     950    6.12     978    5.62     980       3     982       3     985       3
     986    5.42    1000    5.42    1050    6.42    1100    6.22    1117    5.72
    1121    5.02    1126    6.12    1131    6.92    1136    6.81    1146    6.89
    1156    6.67
#Mann=3,0
     550     .09       0     978     .07       0     986     .05       0
Levee=0,,,-1,1050,6.42
Bank Sta=978,986
Exp/Cntr=0.3,0.1

Type RM Length L Ch R =1,3750    ,3,3,3,0,0,0
#Sta/Elev= 21
     550       8     650       7     800    6.32     850    6.22     900    6.22
     950    6.12     978    5.62     980       3     982       3     985       3
     986    5.42    1000    5.42    1050    6.42    1100    6.22    1117    5.72
    1121    5.02    1126    6.12    1131    6.92    1136    6.81    1146    6.89
    1156    6.67
#Mann=3,0
     550     .09       0     978     .07       0     986     .05       0
Bank Sta=978,986
Exp/Cntr=0.3,0.1

Type RM Length L Ch R =1,3747    ,25,25,25,0,0,0
#Sta/Elev= 21
     550       8     650       7     800    6.32     850    6.22     900    6.22
     950    6.12     978    5.62     978     -.3     982     -.3     985     -.3
     986    5.42    1000    5.42    1050    6.42    1100    6.22    1117    5.72
    1121    5.02    1126    6.12    1131    6.92    1136    6.81    1146    6.89
    1156    6.67
#Mann=3,0
     550     .09       0     978     .07       0     986     .05       0
#XS Ineff= 2 , 0
             979     6.9     985             7.1
Bank Sta=978,986
Exp/Cntr=0.3,0.1

Type RM Length L Ch R =2,3735    ,,,,0,0,0
Node Desc=OLD BAYSHORE RD.
Bridge Culvert--1,0,-1,-1
Deck Dist Width WeirC Skew NumUp NumDn MinLoCord MaxHiCord MaxSubmerge Is_Ogee
0,25,2.6,,12,12,,,0.95,0
     550     750     800     850     900     950    1000    1050    1100    1150
    1200    1250
       8     7.8     7.6     7.4       7     6.9     7.1     6.9     6.7     6.7
     6.6     6.5
      -1      -1      -1      -1      -1      -1      -1      -1      -1      -1
      -1      -1
     750     800     850     900     950    1000    1050    1100    1150    1200
    1250    1400
     7.8     7.6     7.4       7     6.9     7.1     6.9     6.7     6.7     6.6
     6.5       6
      -1      -1      -1      -1      -1      -1      -1      -1      -1      -1
      -1      -1
Culvert=2,6,6,25,0.012,0.2,0.2,8,1,-0.3,982,-0.76,1032,Culvert #1  , 0

Type RM Length L Ch R =1,3722    ,32,32,32,0,0,0
#Sta/Elev= 19
     550      10     850       7     865     6.4     900     6.1     950     5.5
    1000     5.3    1019     5.2    1025     4.7    1028     -.8    1036     -.8
    1042     5.3    1060     5.2    1100     4.9    1150     5.2    1400       6
    1650       5    2000       5    2100       6    3200       7
#Mann=3,0
     550     .04       0    1019     .07       0    1042     .15       0
#XS Ineff= 2 , 0
            1029     5.2    1035             5.2
Bank Sta=1019,1042
Exp/Cntr=0.3,0.1

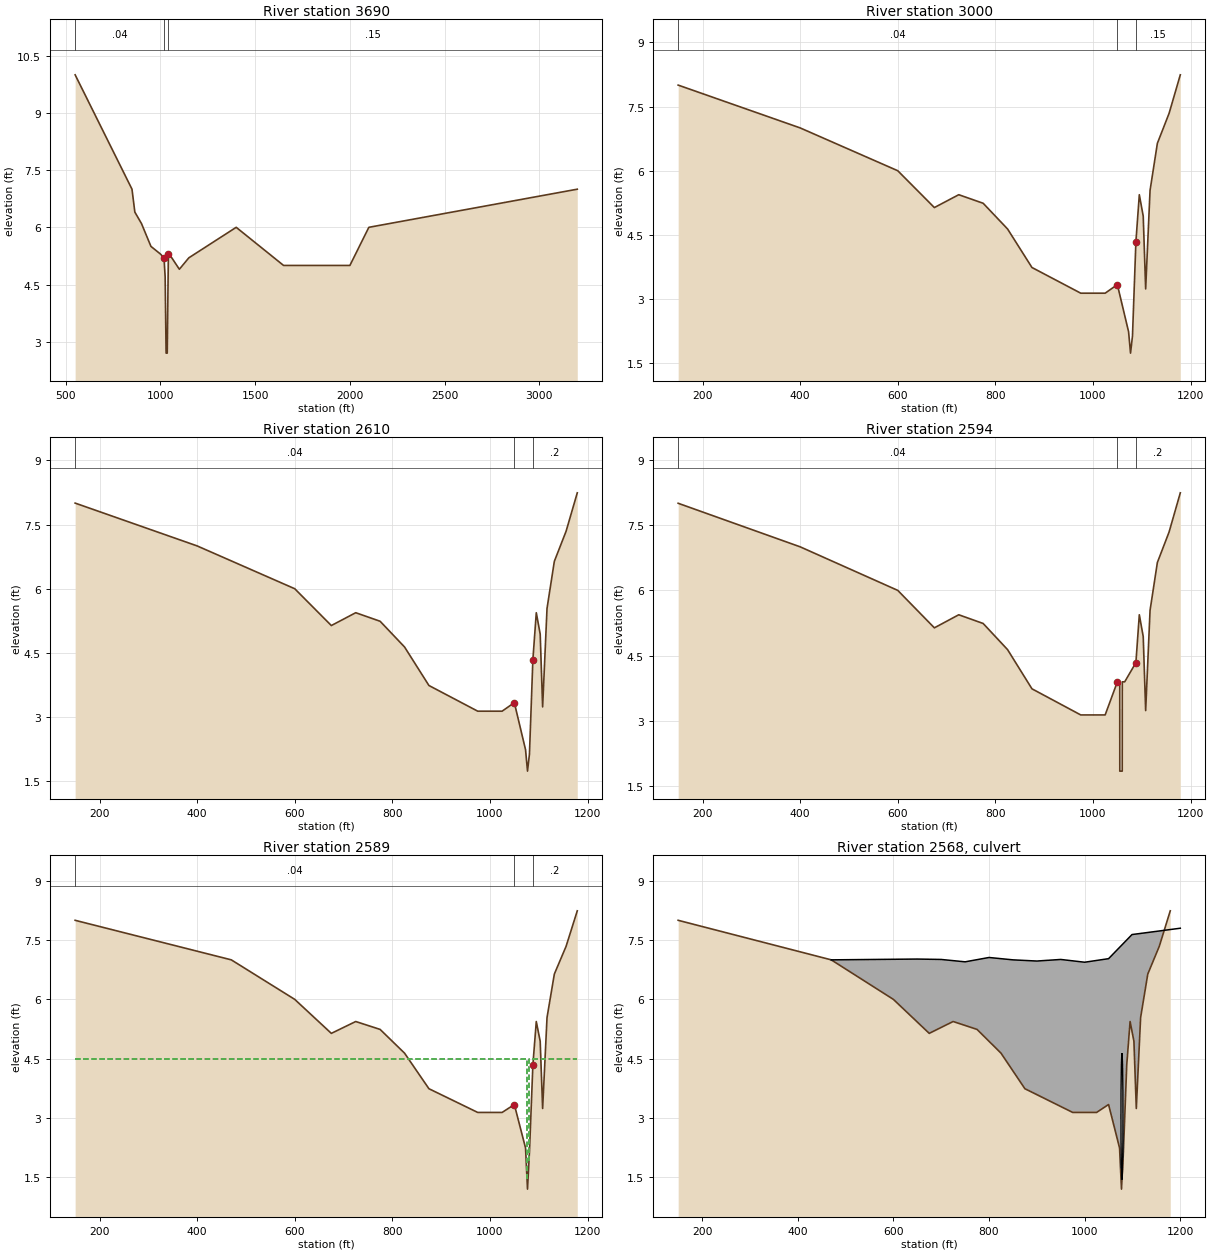
Type RM Length L Ch R =1,3690    ,690,690,690,0,0,0
#Sta/Elev= 19
     550      10     850       7     865     6.4     900     6.1     950     5.5
    1000     5.3    1019     5.2    1025     4.7    1030     2.7    1036     2.7
    1042     5.3    1060     5.2    1100     4.9    1150     5.2    1400       6
    1650       5    2000       5    2100       6    3200       7
#Mann=3,0
     550     .04       0    1019     .07       0    1042     .15       0
Bank Sta=1019,1042
Exp/Cntr=0.3,0.1

Type RM Length L Ch R =1,3000    ,390,390,390,0,0,0
Node Desc=XC 2610
#Sta/Elev= 24
     150       8     400       7     600       6     675    5.14     725    5.44
     775    5.24     825    4.64     875    3.74     925    3.44     975    3.14
    1000    3.14    1025    3.14    1050    3.34    1073    2.24    1077    1.74
    1081    2.14    1088    4.34    1095    5.44    1103    4.94    1108    3.24
    1117    5.54    1132    6.64    1156    7.34    1179    8.24
#Mann=3,0
     150     .04       0    1050     .07       0    1088     .15       0
Bank Sta=1050,1088
Exp/Cntr=0.3,0.1

Type RM Length L Ch R =1,2610    ,16,16,16,0,0,0
#Sta/Elev= 24
     150       8     400       7     600       6     675    5.14     725    5.44
     775    5.24     825    4.64     875    3.74     925    3.44     975    3.14
    1000    3.14    1025    3.14    1050    3.34    1073    2.24    1077    1.74
    1081    2.14    1088    4.34    1095    5.44    1103    4.94    1108    3.24
    1117    5.54    1132    6.64    1156    7.34    1179    8.24
#Mann=3,0
     150     .04       0    1050     .07       0    1088      .2       0
Bank Sta=1050,1088
Exp/Cntr=0.3,0.1

Type RM Length L Ch R =1,2594    ,5,5,5,0,0,0
Node Desc=WEIR
#Sta/Elev= 26
     150       8     400       7     600       6     675    5.14     725    5.44
     775    5.24     825    4.64     875    3.74     925    3.44     975    3.14
    1000    3.14    1025    3.14    1050     3.9  1054.9     3.9    1055    1.85
    1060    1.85  1060.1     3.9    1065     3.9    1088    4.34    1095    5.44
    1103    4.94    1108    3.24    1117    5.54    1132    6.64    1156    7.34
    1179    8.24
#Mann=3,0
     150     .04       0    1050     .07       0    1088      .2       0
Bank Sta=1050,1088
Exp/Cntr=0.3,0.1

Type RM Length L Ch R =1,2589    ,49,49,49,0,0,0
Node Desc=XC 2610
#Sta/Elev= 24
     150       8     470       7     600       6     675    5.14     725    5.44
     775    5.24     825    4.64     875    3.74     925    3.44     975    3.14
    1000    3.14    1025    3.14    1050    3.34    1073    2.24    1077     1.2
    1081    2.14    1088    4.34    1095    5.44    1103    4.94    1108    3.24
    1117    5.54    1132    6.64    1156    7.34    1179    8.24
#Mann=3,0
     150     .04       0    1050     .07       0    1088      .2       0
#XS Ineff= 2 , 0
            1076     4.5    1080             4.5
Bank Sta=1050,1088
Exp/Cntr=0.3,0.1

Type RM Length L Ch R =2,2568    ,,,,0,0,0
Node Desc=38" x 48" RCP
Bridge Culvert--1,0,-1,-1
Deck Dist Width WeirC Skew NumUp NumDn MinLoCord MaxHiCord MaxSubmerge Is_Ogee
5,25,2.6,,12,12,,,0.95,0
     470     650     700     750     800     850     900     950    1000    1050
    1099    1200
       7    7.02    7.01    6.95    7.06       7    6.97    7.01    6.94    7.03
    7.64     7.8
      -4      -4      -4      -4      -4      -4      -4      -4      -4      -4
      -4      -4
     650     700     750     800     850     900     950    1000    1050    1099
    1200    1850
    7.02    7.01    6.95    7.06       7    6.97    7.01    6.94    7.03    7.64
     7.8       7
      -4      -4      -4      -4      -4      -4      -4      -4      -4      -4
      -4      -4
Culvert=4,3.2,4,49,0.024,0.5,0.5,29,3,1.44,1078,1.3,1078,Culvert #1  , 0

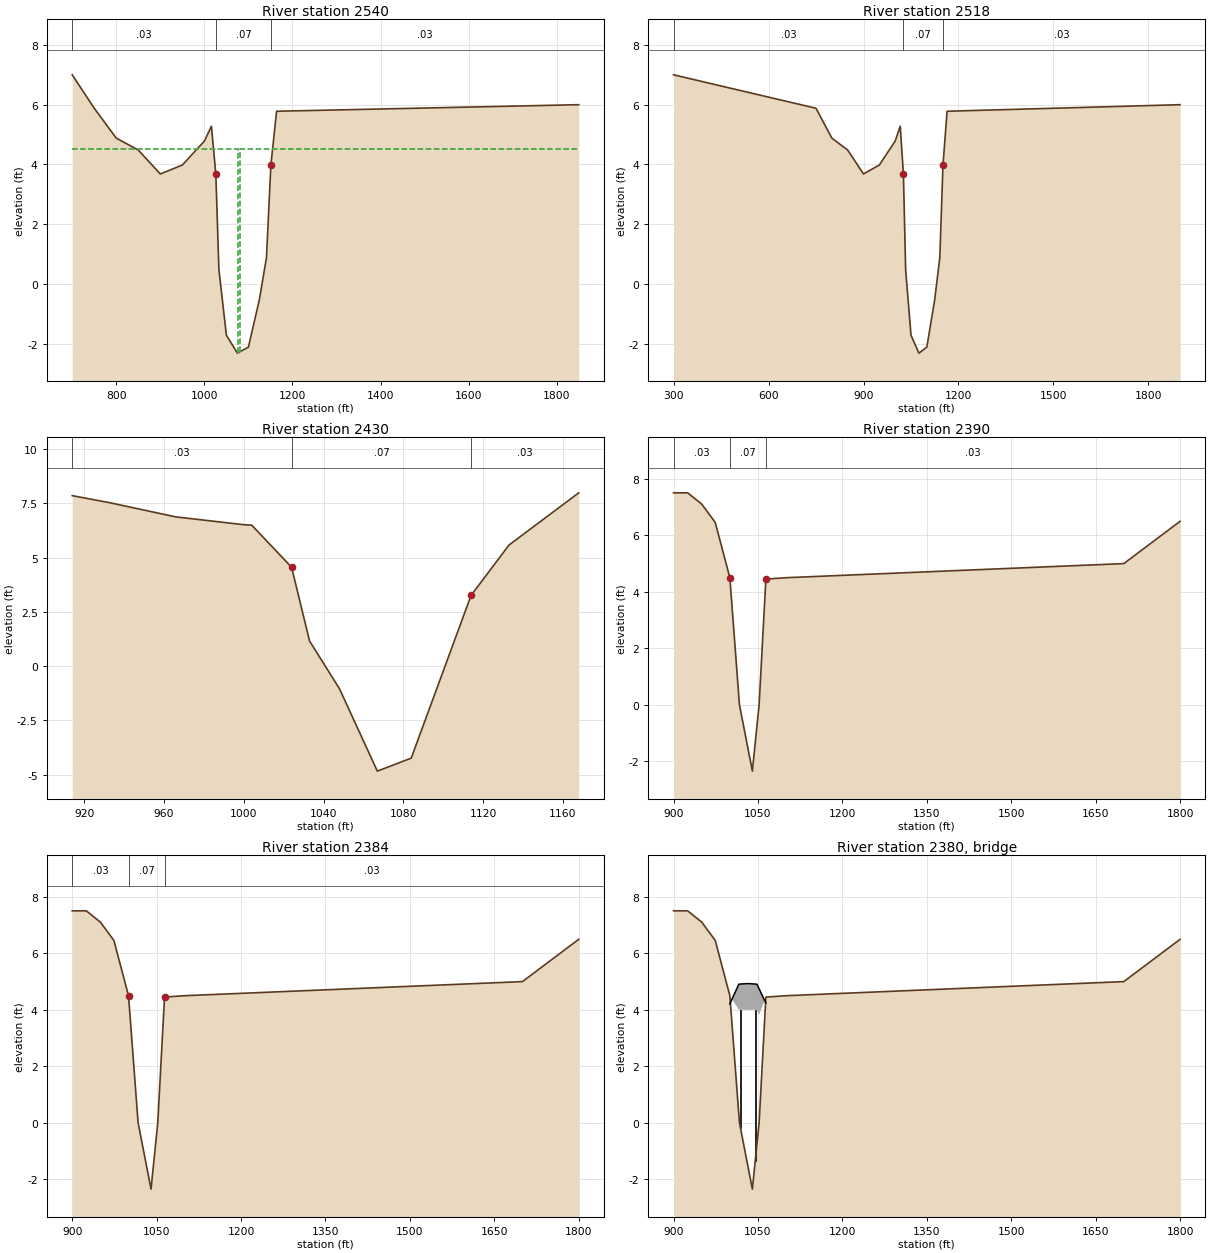
Type RM Length L Ch R =1,2540    ,22,22,22,0,0,0
Node Desc=XC 2518
#Sta/Elev= 18
     700       7     750    5.88     800    4.88     850    4.48     900    3.68
     950    3.98    1000    4.78    1016    5.28    1026    3.68    1033     .48
    1050   -1.72    1075   -2.32    1100   -2.12    1125    -.52    1141     .88
    1151    3.98    1164    5.78    1850       6
#Mann=3,0
     700     .03       0    1026     .07       0    1151     .03       0
#XS Ineff= 2 , 0
            1076     4.5    1080             4.5
Bank Sta=1026,1151
Exp/Cntr=0.3,0.1

Type RM Length L Ch R =1,2518    ,88,88,88,0,0,0
#Sta/Elev= 18
     300       7     750    5.88     800    4.88     850    4.48     900    3.68
     950    3.98    1000    4.78    1016    5.28    1026    3.68    1033     .48
    1050   -1.72    1075   -2.32    1100   -2.12    1125    -.52    1141     .88
    1151    3.98    1164    5.78    1900       6
#Mann=3,0
     300     .03       0    1026     .07       0    1151     .03       0
Bank Sta=1026,1151
Exp/Cntr=0.3,0.1

Type RM Length L Ch R =1,2430    ,40,40,40,0,0,0
#Sta/Elev= 14
     914    7.86     933    7.53     966    6.88    1000    6.52    1004     6.5
    1024    4.56    1033    1.16    1048   -1.04    1067   -4.84    1084   -4.24
    1104     .76    1114    3.26    1133    5.58    1168    7.99
#Mann=3,0
     914     .03       0    1024     .07       0    1114     .03       0
Bank Sta=1024,1114
Exp/Cntr=0.3,0.1

Type RM Length L Ch R =1,2390    ,6,6,6,0,0,0
Node Desc=XC 2370
#Sta/Elev= 12
     900    7.51     925    7.51     950    7.11     974    6.46    1000     4.5
    1017       0    1040   -2.36    1052       0    1064    4.45    1100     4.5
    1700       5    1800     6.5
#Mann=3,0
     900     .03       0    1000     .07       0    1064     .03       0
Bank Sta=1000,1064
Exp/Cntr=0.3,0.1

Type RM Length L Ch R =1,2384    ,9,9,9,0,0,0
#Sta/Elev= 12
     900    7.51     925    7.51     950    7.11     974    6.46    1000     4.5
    1017       0    1040   -2.36    1052       0    1064    4.45    1100     4.5
    1700       5    1800     6.5
#Mann=3,0
     900     .03       0    1000     .07       0    1064     .03       0
Bank Sta=1000,1064
Exp/Cntr=0.3,0.1

Type RM Length L Ch R =3,2380    ,,,,0,0,0
Node Desc=WOODEN BRIDGE
Bridge Culvert--1,0,-1,-1
Deck Dist Width WeirC Skew NumUp NumDn MinLoCord MaxHiCord MaxSubmerge Is_Ogee
0,8.5,2.6,,5,5,,,0.95,0
    1000    1016    1032    1048    1064
    4.21    4.91    4.93    4.91    4.24
     3.3       4       4       4     3.3
    1000    1016    1032    1048    1064
    4.21    4.91    4.93    4.91    4.24
     3.3       4       4       4     3.3
Pier Skew, UpSta & Num, DnSta & Num=,1019, 2,1019, 2, 0, 0
    1.25    1.25
      -2       4
    1.25    1.25
      -2       4
Pier Skew, UpSta & Num, DnSta & Num=,1045, 2,1045, 2, 0, 0
    1.25    1.25
      -2       4
    1.25    1.25
      -2       4
BR Coef= 0, 0,-1,1.05, 0,,,0.8,0,0,2,

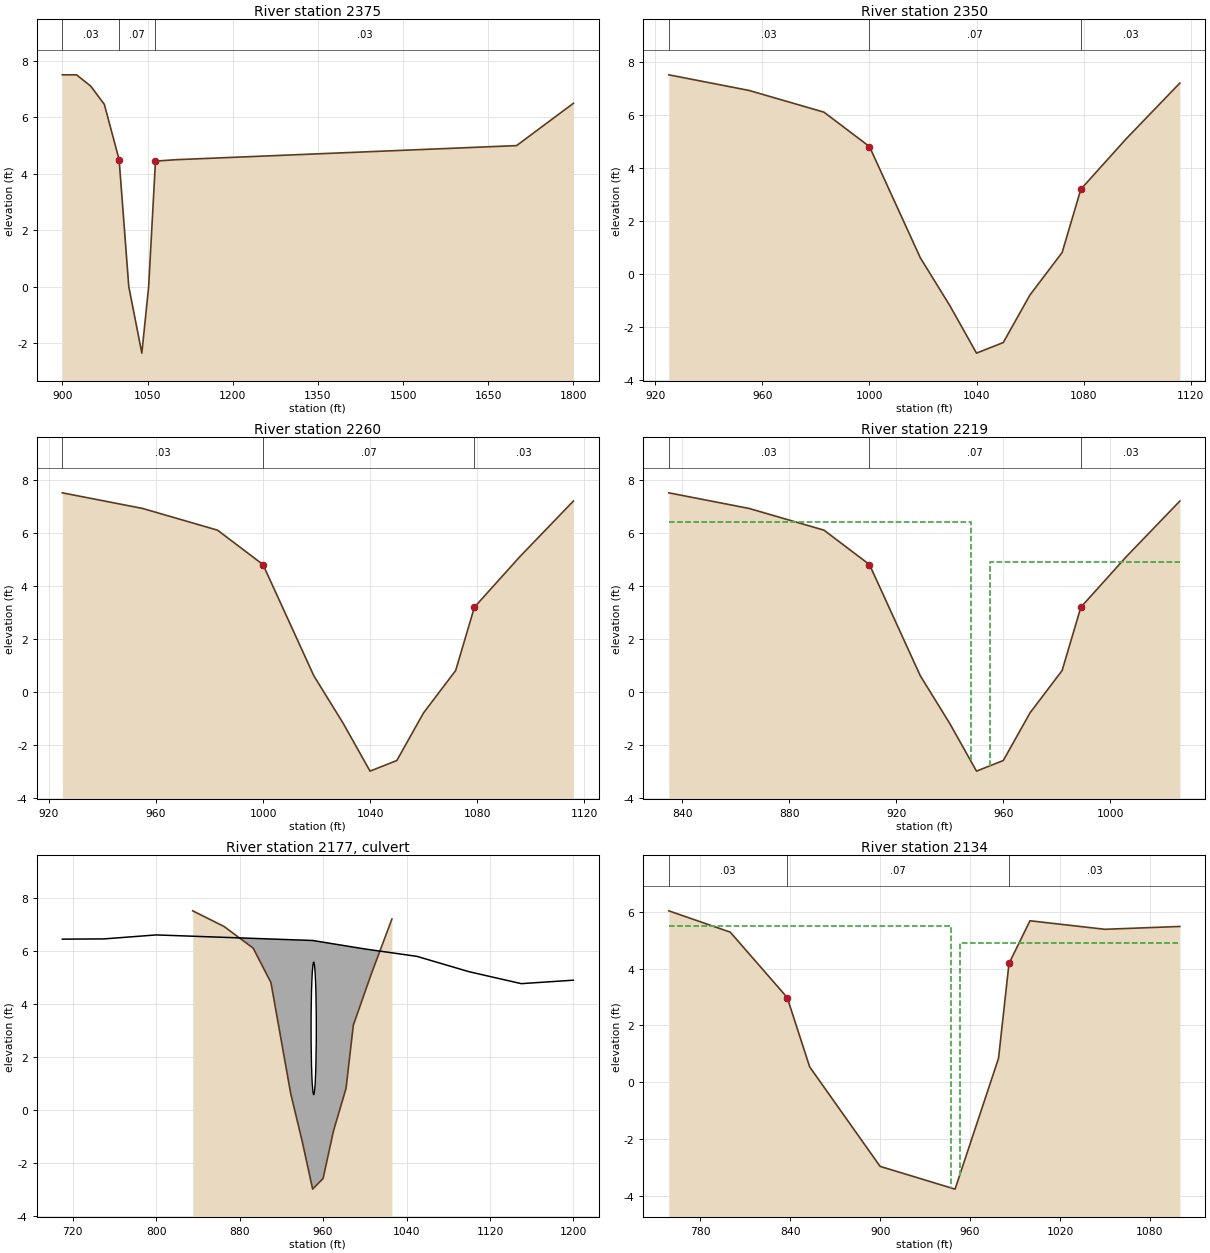
Type RM Length L Ch R =1,2375    ,25,25,25,0,0,0
#Sta/Elev= 12
     900    7.51     925    7.51     950    7.11     974    6.46    1000     4.5
    1017       0    1040   -2.36    1052       0    1064    4.45    1100     4.5
    1700       5    1800     6.5
#Mann=3,0
     900     .03       0    1000     .07       0    1064     .03       0
Bank Sta=1000,1064
Exp/Cntr=0.3,0.1

Type RM Length L Ch R =1,2350    ,90,90,90,0,0,0
#Sta/Elev= 13
     925    7.52     955    6.93     983    6.11    1000    4.81    1019     .61
    1030   -1.19    1040   -2.99    1050   -2.59    1060    -.79    1072     .81
    1079     3.2    1096    5.11    1116    7.21
#Mann=3,0
     925     .03       0    1000     .07       0    1079     .03       0
Bank Sta=1000,1079
Exp/Cntr=0.3,0.1

Type RM Length L Ch R =1,2260    ,41,41,41,0,0,0
Node Desc=XC 2350
#Sta/Elev= 13
     925    7.52     955    6.93     983    6.11    1000    4.81    1019     .61
    1030   -1.19    1040   -2.99    1050   -2.59    1060    -.79    1072     .81
    1079     3.2    1096    5.11    1116    7.21
#Mann=3,0
     925     .03       0    1000     .07       0    1079     .03       0
Bank Sta=1000,1079
Exp/Cntr=0.3,0.1

Type RM Length L Ch R =1,2219    ,85,85,85,0,0,0
Node Desc=XC 2330
#Sta/Elev= 13
     835    7.52     865    6.93     893    6.11     910    4.81     929     .61
     940   -1.19     950   -2.99     960   -2.59     970    -.79     982     .81
     989     3.2    1006    5.11    1026    7.21
#Mann=3,0
     835     .03       0     910     .07       0     989     .03       0
#XS Ineff= 2 , 0
             948     6.4     955             4.9
Bank Sta=910,989
Exp/Cntr=0.3,0.1

Type RM Length L Ch R =2,2177    ,,,,0,0,0
Bridge Culvert--1,0,-1,-1
Deck Dist Width WeirC Skew NumUp NumDn MinLoCord MaxHiCord MaxSubmerge Is_Ogee
0,85,2.6,,9,9,,,0.95,0
     710     750     800     950    1000    1050    1100    1150    1200
    6.45    6.46    6.61     6.4    6.08     5.8    5.22    4.77     4.9
      -4      -4      -4      -4      -4      -4      -4      -4      -4
     710     750     800     950    1000    1050    1100    1150    1200
    6.45    6.46    6.61     6.4    6.08     5.8    5.22    4.77     4.9
      -4      -4      -4      -4      -4      -4      -4      -4      -4
Culvert=1,5,,85,0.024,0.5,0.5,2,3,0.58,951,0.58,950,Culvert #1  , 0

Type RM Length L Ch R =1,2134    ,284,284,284,0,0,0
#Sta/Elev= 11
     759    6.03     800    5.28     838    2.98     853     .54     900   -2.96
     950   -3.76     979     .84     986    4.18    1000    5.68    1050    5.38
    1100    5.48
#Mann=3,0
     759     .03       0     838     .07       0     986     .03       0
#XS Ineff= 2 , 0
             947     5.5     953             4.9
Bank Sta=838,986
Exp/Cntr=0.3,0.1

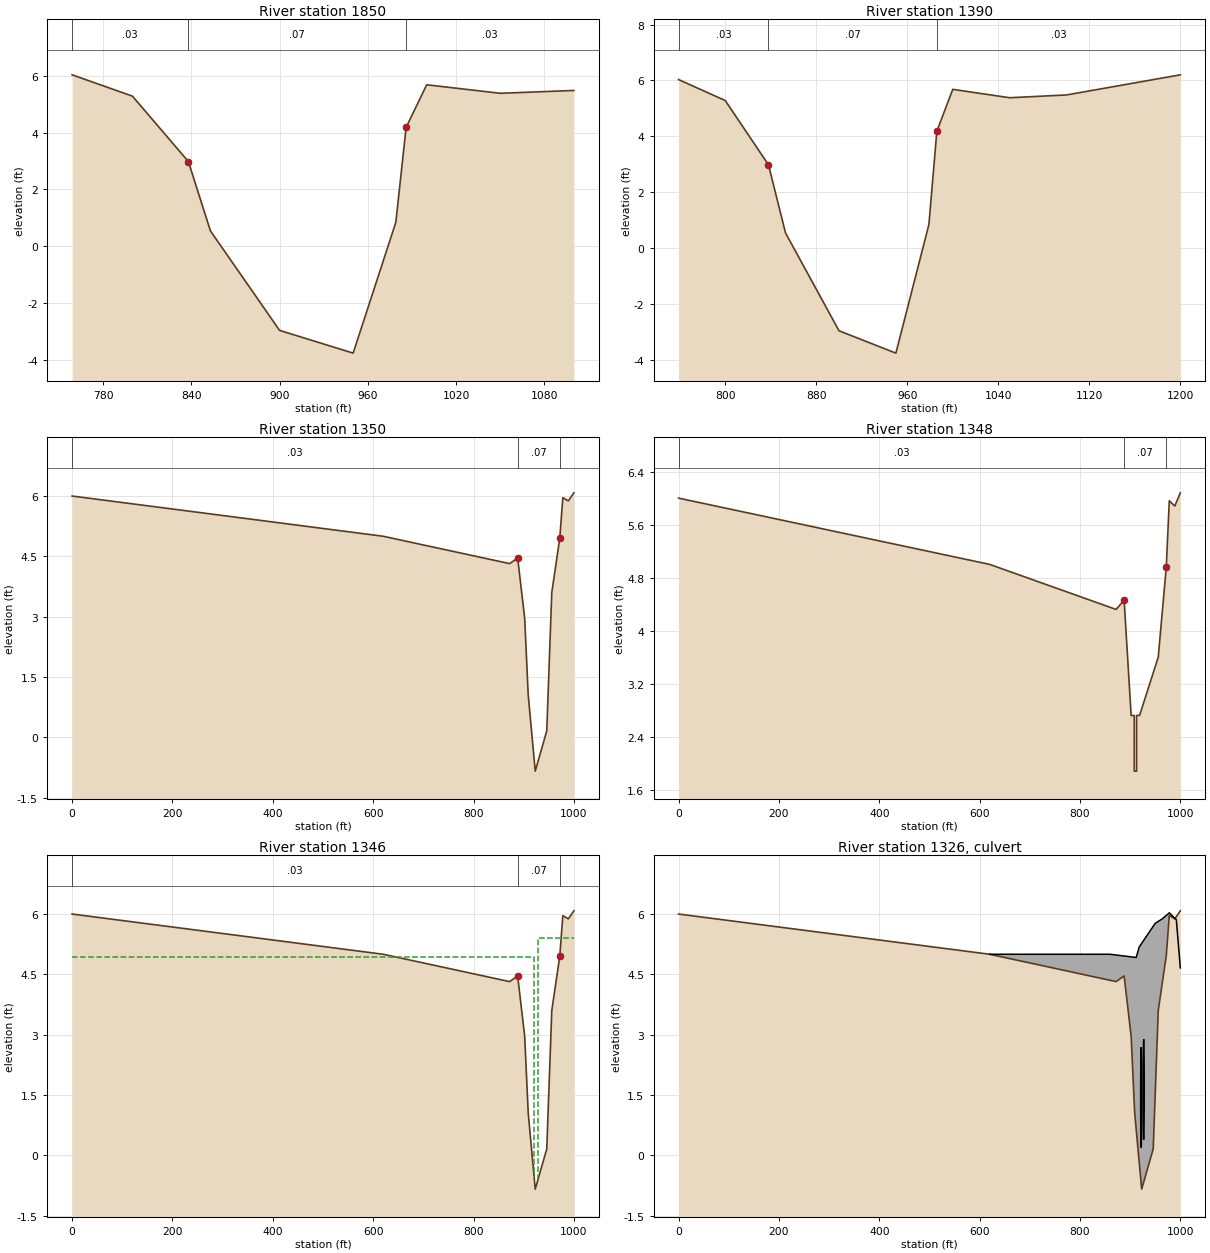
Type RM Length L Ch R =1,1850    ,460,460,460,0,0,0
Node Desc=XC 2134
#Sta/Elev= 11
     759    6.03     800    5.28     838    2.98     853     .54     900   -2.96
     950   -3.76     979     .84     986    4.18    1000    5.68    1050    5.38
    1100    5.48
#Mann=3,0
     759     .03       0     838     .07       0     986     .03       0
Bank Sta=838,986
Exp/Cntr=0.3,0.1

Type RM Length L Ch R =1,1390    ,40,40,40,0,0,0
Node Desc=XC 2134
#Sta/Elev= 12
     759    6.03     800    5.28     838    2.98     853     .54     900   -2.96
     950   -3.76     979     .84     986    4.18    1000    5.68    1050    5.38
    1100    5.48    1200     6.2
#Mann=3,0
     759     .03       0     838     .07       0     986     .03       0
Bank Sta=838,986
Exp/Cntr=0.3,0.1

Type RM Length L Ch R =1,1350    ,2,2,2,0,0,0
Node Desc=XC 1280
#Sta/Elev= 13
       0       6     620       5     872    4.32     888    4.46     902    2.96
     909    1.06     923    -.84     946     .16     956     3.6     972    4.96
     978    5.96     989    5.88    1000    6.08
#Mann=3,0
       0     .03       0     888     .07       0     972     .03       0
Bank Sta=888,972
Exp/Cntr=0.3,0.1

Type RM Length L Ch R =1,1348    ,2,2,2,0,0,0
Node Desc=WEIR
#Sta/Elev= 15
       0       6     620       5     872    4.32     888    4.46     902    2.72
   908.2    2.72  908.21    1.88   912.8    1.88  912.81    2.72   918.8    2.72
     956     3.6     972    4.96     978    5.96     989    5.88    1000    6.08
#Mann=3,0
       0     .03       0     888     .07       0     972     .03       0
Bank Sta=888,972
Exp/Cntr=0.3,0.1

Type RM Length L Ch R =1,1346    ,41,41,41,0,0,0
Node Desc=XC 1280
#Sta/Elev= 13
       0       6     620       5     872    4.32     888    4.46     902    2.96
     909    1.06     923    -.84     946     .16     956     3.6     972    4.96
     978    5.96     989    5.88    1000    6.08
#Mann=3,0
       0     .03       0     888     .07       0     972     .03       0
#XS Ineff= 2 , 0
             921    4.92     928             5.4
Bank Sta=888,972
Exp/Cntr=0.3,0.1

Type RM Length L Ch R =2,1326    ,,,,0,0,0
Node Desc=CULVERTS @ S. END LAKE 2
Bridge Culvert--1,0,-1,-1
Deck Dist Width WeirC Skew NumUp NumDn MinLoCord MaxHiCord MaxSubmerge Is_Ogee
0,41,2.6,,9,9,,,0.95,0
     620     860     912     918     950     964     978     992    1000
       5       5    4.92    5.18    5.77    5.88    6.03    5.86    4.66
      -1      -1      -1      -1      -1      -1      -1      -1      -1
     620     860     912     918     950     964     978     992    1000
       5       5    4.92    5.18    5.77    5.88    6.03    5.86    4.66
      -1      -1      -1      -1      -1      -1      -1      -1      -1
Culvert=1,2.5,,41,0.024,0.5,0.5,2,3,0.19,922,0.5,922,Culvert #2  , 0
Culvert=1,2.5,,41,0.024,0.5,0.8,2,3,0.39,927,0.51,927,Culvert #1  , 0

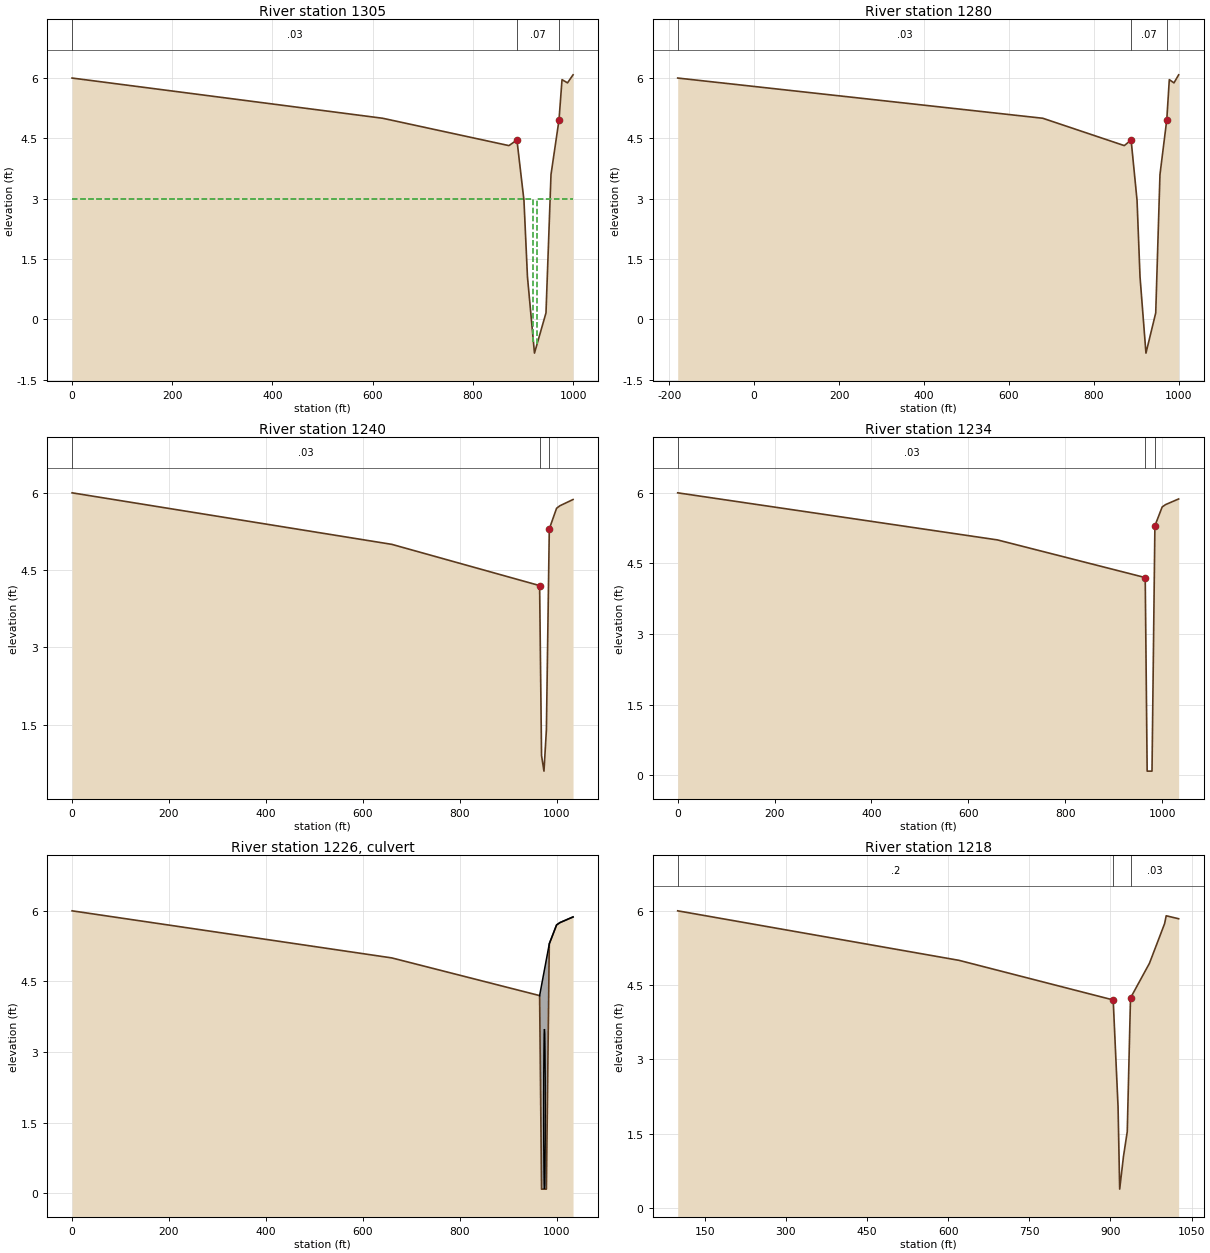
Type RM Length L Ch R =1,1305    ,25,25,25,0,0,0
Node Desc=XC 1280
#Sta/Elev= 13
       0       6     620       5     872    4.32     888    4.46     902    2.96
     909    1.06     923    -.84     946     .16     956     3.6     972    4.96
     978    5.96     989    5.88    1000    6.08
#Mann=3,0
       0     .03       0     888     .07       0     972     .03       0
#XS Ineff= 2 , 0
             921       3     928               3
Bank Sta=888,972
Exp/Cntr=0.3,0.1

Type RM Length L Ch R =1,1280    ,40,40,40,0,0,0
#Sta/Elev= 13
    -180       6     680       5     872    4.32     888    4.46     902    2.96
     909    1.06     923    -.84     946     .16     956     3.6     972    4.96
     978    5.96     989    5.88    1000    6.08
#Mann=3,0
    -180     .03       0     888     .07       0     972     .03       0
Bank Sta=888,972
Exp/Cntr=0.3,0.1

Type RM Length L Ch R =1,1240    ,6,6,6,0,0,0
#Sta/Elev= 10
       0       6     660       5     965     4.2     969      .9     974      .6
     979     1.4     985     5.3    1000     5.7    1007    5.75    1034    5.87
#Mann=3,0
       0     .03       0     965     .07       0     985     .03       0
Bank Sta=965,985
Exp/Cntr=0.3,0.1

Type RM Length L Ch R =1,1234    ,16,16,16,0,0,0
#Sta/Elev= 10
       0       6     660       5     965     4.2     969     .09     974     .09
     979     .09     985     5.3    1000     5.7    1007    5.75    1034    5.87
#Mann=3,0
       0     .03       0     965     .07       0     985     .03       0
Bank Sta=965,985
Exp/Cntr=0.3,0.1

Type RM Length L Ch R =2,1226    ,,,,0,0,0
Node Desc=CULVERT @ S. END LAKE 1
Bridge Culvert--1,0,-1,-1
Deck Dist Width WeirC Skew NumUp NumDn MinLoCord MaxHiCord MaxSubmerge Is_Ogee
0,16,2.6,,5,4,,,0.95,0
     965     985    1000    1007    1034
     4.2     5.3     5.7    5.75    5.87
       0       0       0       0       0
     905    1000    1003    1026
     4.2    5.74     5.9    5.84
       0       0       0       0
Culvert=3,3.4,,16,0.024,0.5,0.5,34,3,0.09,975,0.38,918,Culvert #1  , 0

Type RM Length L Ch R =1,1218    ,48,48,48,0,0,0
#Sta/Elev= 12
     100       6     620       5     905     4.2     914    2.04     917     .38
     924    1.04     931    1.54     937    4.24     972    4.94    1000    5.74
    1003     5.9    1026    5.84
#Mann=3,0
     100      .2       0     905     .07       0     937     .03       0
Bank Sta=905,937
Exp/Cntr=0.3,0.1

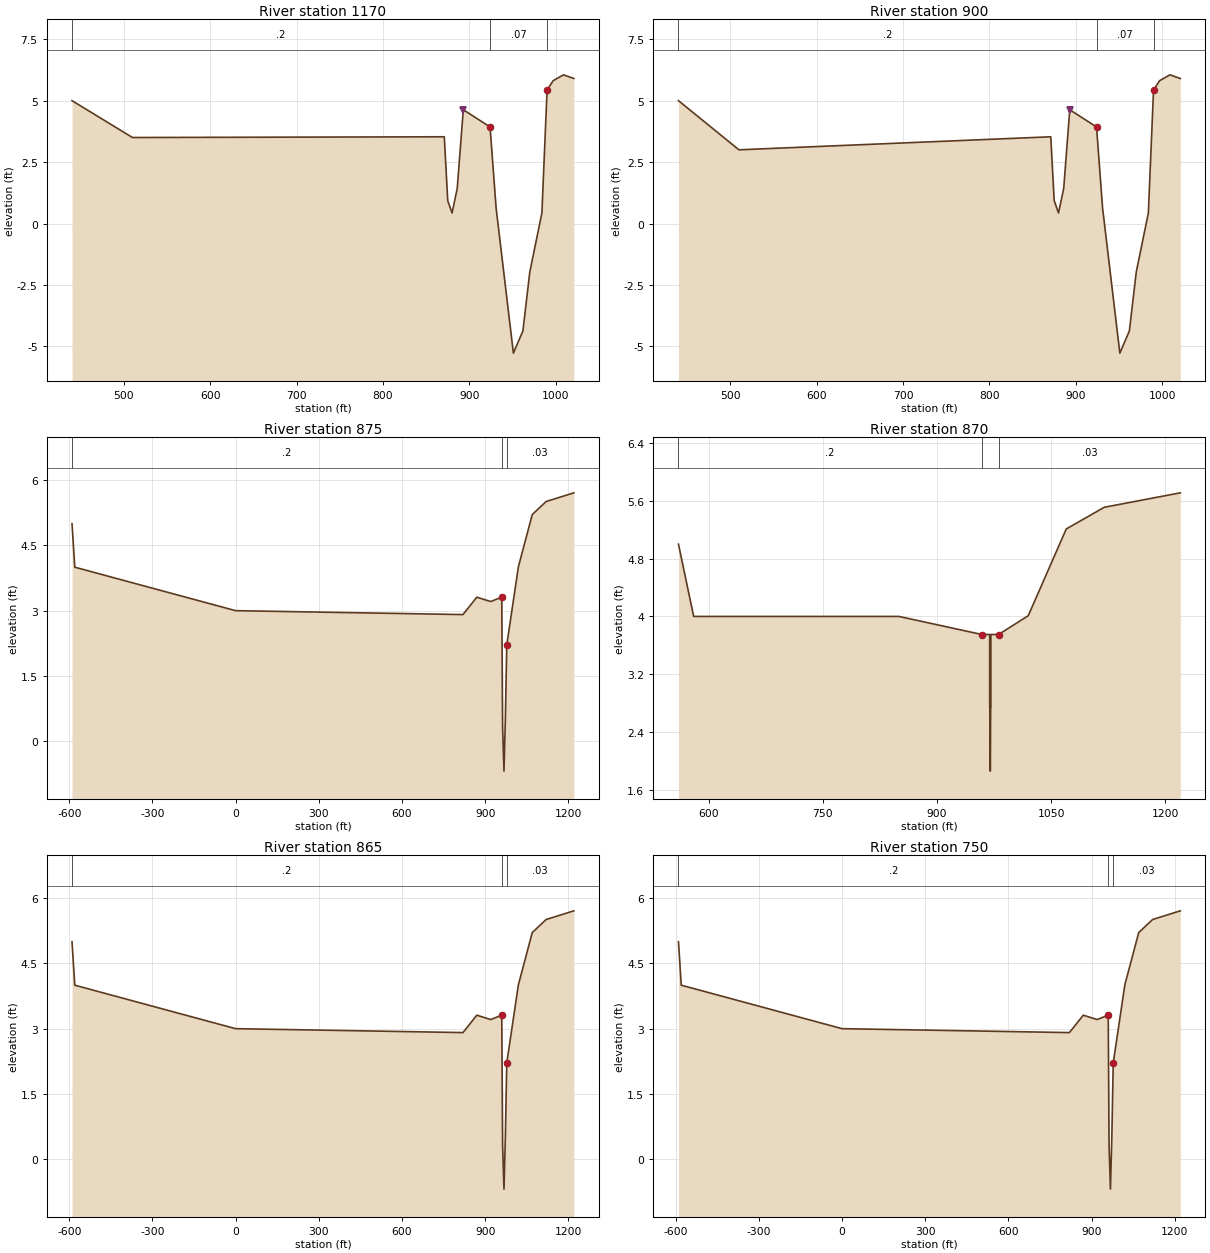
Type RM Length L Ch R =1,1170    ,270,270,270,0,0,0
Node Desc=JEI XSEC
#Sta/Elev= 18
     440       5     510     3.5     871    3.53     875     .93     880     .43
     886    1.43     893    4.63     924    3.93     931     .63     951   -5.27
     962   -4.37     970   -1.97     984     .43     990    5.43     997    5.81
    1000    5.87    1009    6.05    1021     5.9
#Mann=3,0
     440      .2       0     924     .07       0     990     .03       0
Levee=-1,893,4.63,0,,
Bank Sta=924,990
Exp/Cntr=0.3,0.1

Type RM Length L Ch R =1,900     ,25,25,25,0,0,0
Node Desc=JEI XSEC
#Sta/Elev= 18
     440       5     510       3     871    3.53     875     .93     880     .43
     886    1.43     893    4.63     924    3.93     931     .63     951   -5.27
     962   -4.37     970   -1.97     984     .43     990    5.43     997    5.81
    1000    5.87    1009    6.05    1021     5.9
#Mann=3,0
     440      .2       0     924     .07       0     990     .03       0
Levee=-1,893,4.63,0,,
Bank Sta=924,990
Exp/Cntr=0.3,0.1

Type RM Length L Ch R =1,875     ,5,5,5,0,0,0
Node Desc=XC 750
#Sta/Elev= 16
    -590       5    -580       4       0       3     820    2.91     870    3.31
     920    3.21     960    3.31     963     .31     968    -.69     973     .51
     978    2.21    1020    4.01    1070    5.21    1120    5.51    1170    5.61
    1220    5.71
#Mann=3,0
    -590      .2       0     960     .07       0     978     .03       0
Bank Sta=960,978
Exp/Cntr=0.3,0.1

Type RM Length L Ch R =1,870     ,5,5,5,0,0,0
Node Desc=WEIR
#Sta/Elev= 18
     560       5     580       4     850       4     959    3.75   969.3    3.75
  969.31    2.74  969.61    2.74     970    1.86  970.15    1.86  970.54    2.74
  970.84    2.74  970.85    3.75     981    3.75    1020    4.01    1070    5.21
    1120    5.51    1170    5.61    1220    5.71
#Mann=3,0
     560      .2       0     959     .03       0     981     .03       0
Bank Sta=959,981
Exp/Cntr=0.3,0.1

Type RM Length L Ch R =1,865     ,115,115,115,0,0,0
Node Desc=XC 750
#Sta/Elev= 16
    -590       5    -580       4       0       3     820    2.91     870    3.31
     920    3.21     960    3.31     963     .31     968    -.69     973     .51
     978    2.21    1020    4.01    1070    5.21    1120    5.51    1170    5.61
    1220    5.71
#Mann=3,0
    -590      .2       0     960     .03       0     978     .03       0
Bank Sta=960,978
Exp/Cntr=0.3,0.1

Type RM Length L Ch R =1,750     ,33,33,33,0,0,0
Node Desc=JEI XSEC
#Sta/Elev= 16
    -590       5    -580       4       0       3     820    2.91     870    3.31
     920    3.21     960    3.31     963     .31     968    -.69     973     .51
     978    2.21    1020    4.01    1070    5.21    1120    5.51    1170    5.61
    1220    5.71
#Mann=3,0
    -590      .2       0     960     .03       0     978     .03       0
Bank Sta=960,978
Exp/Cntr=0.3,0.1

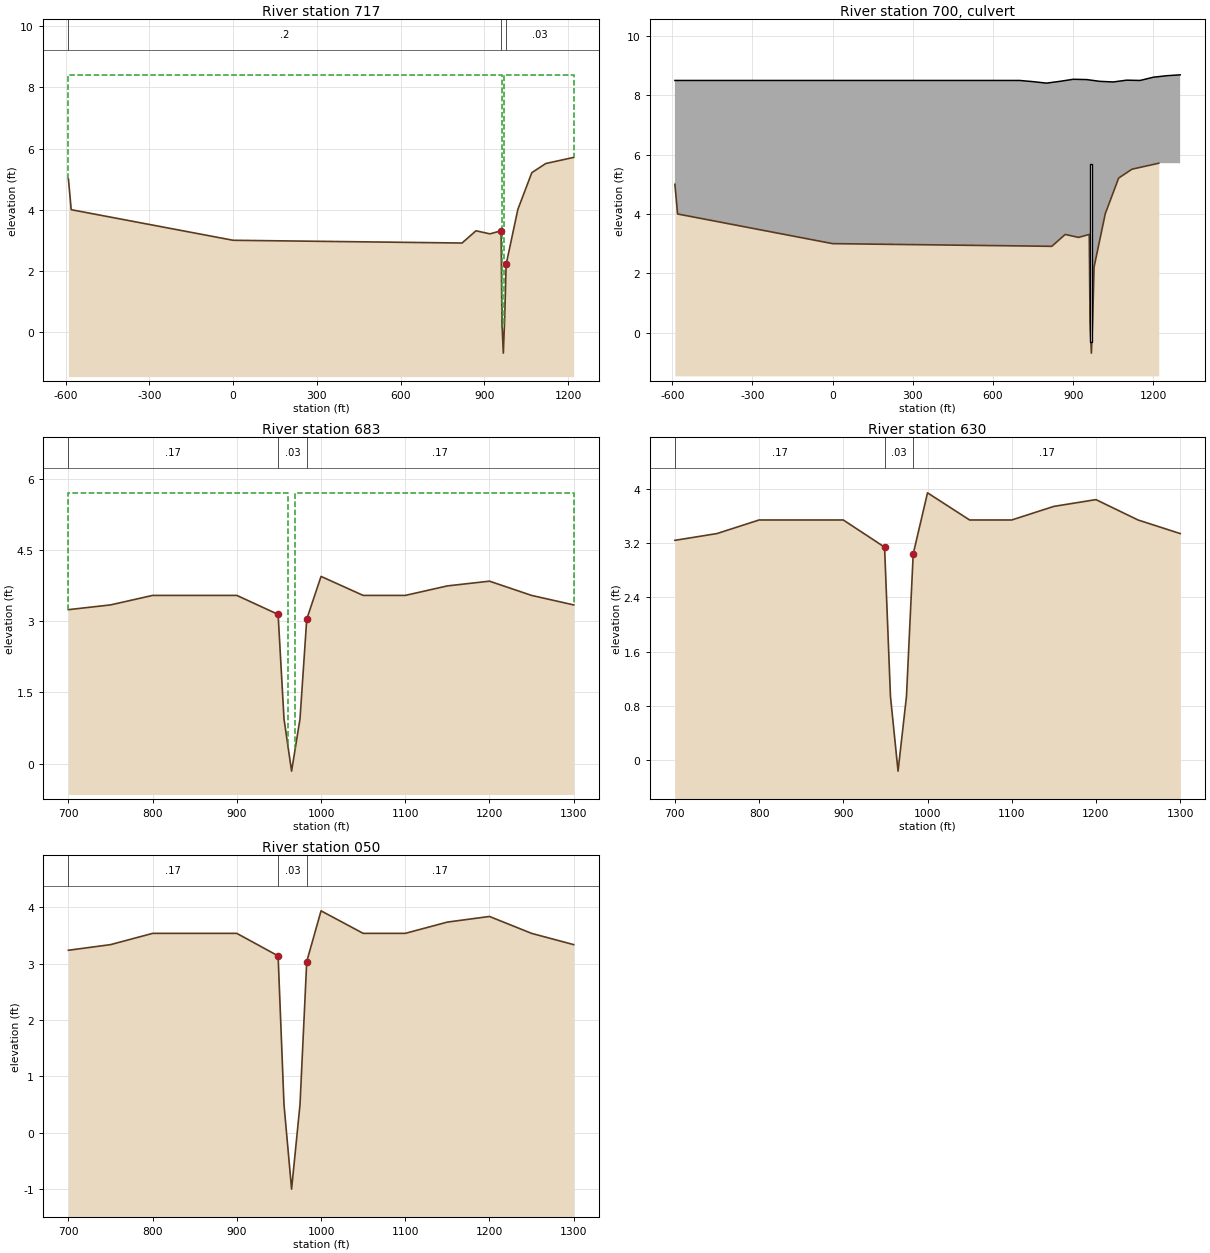
Type RM Length L Ch R =1,717     ,34,34,34,0,0,0
Node Desc=JEI XSEC
#Sta/Elev= 16
    -590       5    -580       4       0       3     820    2.91     870    3.31
     920    3.21     960    3.31     963     .31     968    -.69     973     .51
     978    2.21    1020    4.01    1070    5.21    1120    5.51    1170    5.61
    1220    5.71
#Mann=3,0
    -590      .2       0     960     .03       0     978     .03       0
#XS Ineff= 2 , 0
             964    8.41     972            8.41
Bank Sta=960,978
Exp/Cntr=0.3,0.1

Type RM Length L Ch R =2,700     ,,,,0,0,0
Node Desc=C.R. 78
Bridge Culvert--1,0,-1,-1
Deck Dist Width WeirC Skew NumUp NumDn MinLoCord MaxHiCord MaxSubmerge Is_Ogee
0,34,2.6,,14,14,,,0.95,0
    -590     700     750     800     850     900     950    1000    1050    1100
    1150    1200    1250    1300
     8.5     8.5    8.46    8.41    8.47    8.54    8.53    8.47    8.45    8.51
     8.5    8.61    8.66    8.69
      -1      -1      -1      -1      -1      -1      -1      -1      -1      -1
      -1      -1      -1      -1
    -590     700     750     800     850     900     950    1000    1050    1100
    1150    1200    1250    1300
     8.5     8.5    8.46    8.41    8.47    8.54    8.53    8.47    8.45    8.51
     8.5    8.61    8.66    8.69
      -1      -1      -1      -1      -1      -1      -1      -1      -1      -1
      -1      -1      -1      -1
BR Coef= 0, 0, 0,1.05, 0,,,0.8,0,0,0,
Culvert=2,6,8,34,0.012,0.2,0.2,11,2,-0.31,968,-0.28,965,Culvert #1  , 0

Type RM Length L Ch R =1,683     ,53,53,53,0,0,0
Node Desc=JEI XSEC
#Sta/Elev= 17
     700    3.24     750    3.34     800    3.54     850    3.54     900    3.54
     949    3.14     956     .94     965    -.16     975     .94     983    3.04
    1000    3.94    1050    3.54    1100    3.54    1150    3.74    1200    3.84
    1250    3.54    1300    3.34
#Mann=3,0
     700     .17       0     949     .03       0     983     .17       0
#XS Ineff= 2 , 0
             961     5.7     969             5.7
Bank Sta=949,983
Exp/Cntr=0.3,0.1

Type RM Length L Ch R =1,630     ,580,580,580,0,0,0
Node Desc=JEI XSEC
#Sta/Elev= 17
     700    3.24     750    3.34     800    3.54     850    3.54     900    3.54
     949    3.14     956     .94     965    -.16     975     .94     983    3.04
    1000    3.94    1050    3.54    1100    3.54    1150    3.74    1200    3.84
    1250    3.54    1300    3.34
#Mann=3,0
     700     .17       0     949     .03       0     983     .17       0
Bank Sta=949,983
Exp/Cntr=0.3,0.1

Type RM Length L Ch R =1,050     ,50,50,50,0,0,0
#Sta/Elev= 17
     700    3.24     750    3.34     800    3.54     850    3.54     900    3.54
     949    3.14     956      .5     965      -1     975      .5     983    3.04
    1000    3.94    1050    3.54    1100    3.54    1150    3.74    1200    3.84
    1250    3.54    1300    3.34
#Mann=3,0
     700     .17       0     949     .03       0     983     .17       0
Bank Sta=949,983
Exp/Cntr=0.3,0.1