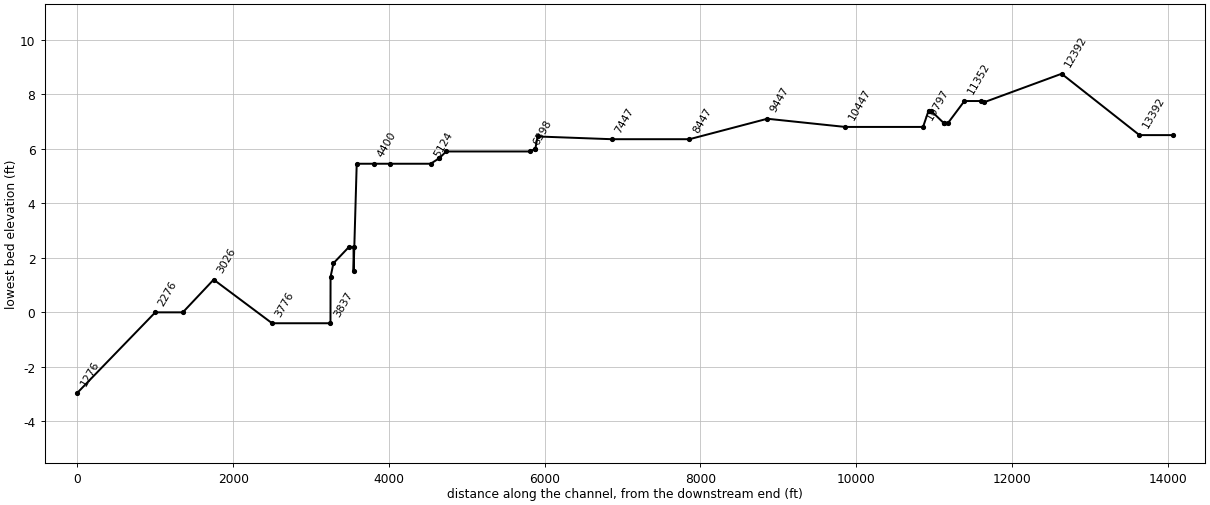
--- leitnrpr.prj (project) ---

Proj Title=PROPOSED LEITNER CREEK
Current Plan=p02
Default Exp/Contr=0.3,0.1
English Units
Geom File=g02
Geom File=g01
Flow File=f02
Flow File=f01
Plan File=p02
Plan File=p01

--- leitnrpr.p02 (plan) ---

Plan Title=Imported Plan 02
Short Identifier=Imported Pla
Geom File=g02
Flow File=f02
Multiple Comp Mode
Subcritical Flow
K Sum by GR= 0
Std Step Tol= .01
Critical Tol= .01
Num of Std Step Trials= 20
Max Error Tol= .3
Flow Tol Ratio= .001
Log Output Level= 0
Friction Slope Method= 1
Calc Critical at every XS
Parabolic Critical Depth

--- leitnrpr.f02 (steady flow) ---

Flow Title=Imported Flow 02
Number of Flows and Profiles and Boundary= 6, 4, 1
Rch & RM=1           ,13717
      10      30      50      70
Rch & RM=1           ,6497
      10      30      50      70
Rch & RM=1           ,5323
      20      50      85     115
Rch & RM=1           ,2630
      20      50      90     125
Rch & RM=1           ,376
      35      75     135     180
Rch & RM=1           ,0
      50     110     185     250
Boundary for Rch & Prof#=1           , 1
Up Type= 2
Up Value=0
Dn Type= 1
Dn Value=4.15
Boundary for Rch & Prof#=1           , 2
Up Type= 2
Up Value=0
Dn Type= 1
Dn Value=6.29
Boundary for Rch & Prof#=1           , 3
Up Type= 2
Up Value=0
Dn Type= 1
Dn Value=7.95
Boundary for Rch & Prof#=1           , 4
Up Type= 2
Up Value=0
Dn Type= 1
Dn Value=9.07

--- leitnrpr.g02 (geometry) ---

Geom Title=Imported Geom 02
ViewRect= 0, 1, 1, 0
Reach=1
Rch X Y Up & X Y Dn=0.5,0.9,0.5,0.1
Rch Arrow X Y Up & X Y Dn=0,0,0,0
Rch Type=0

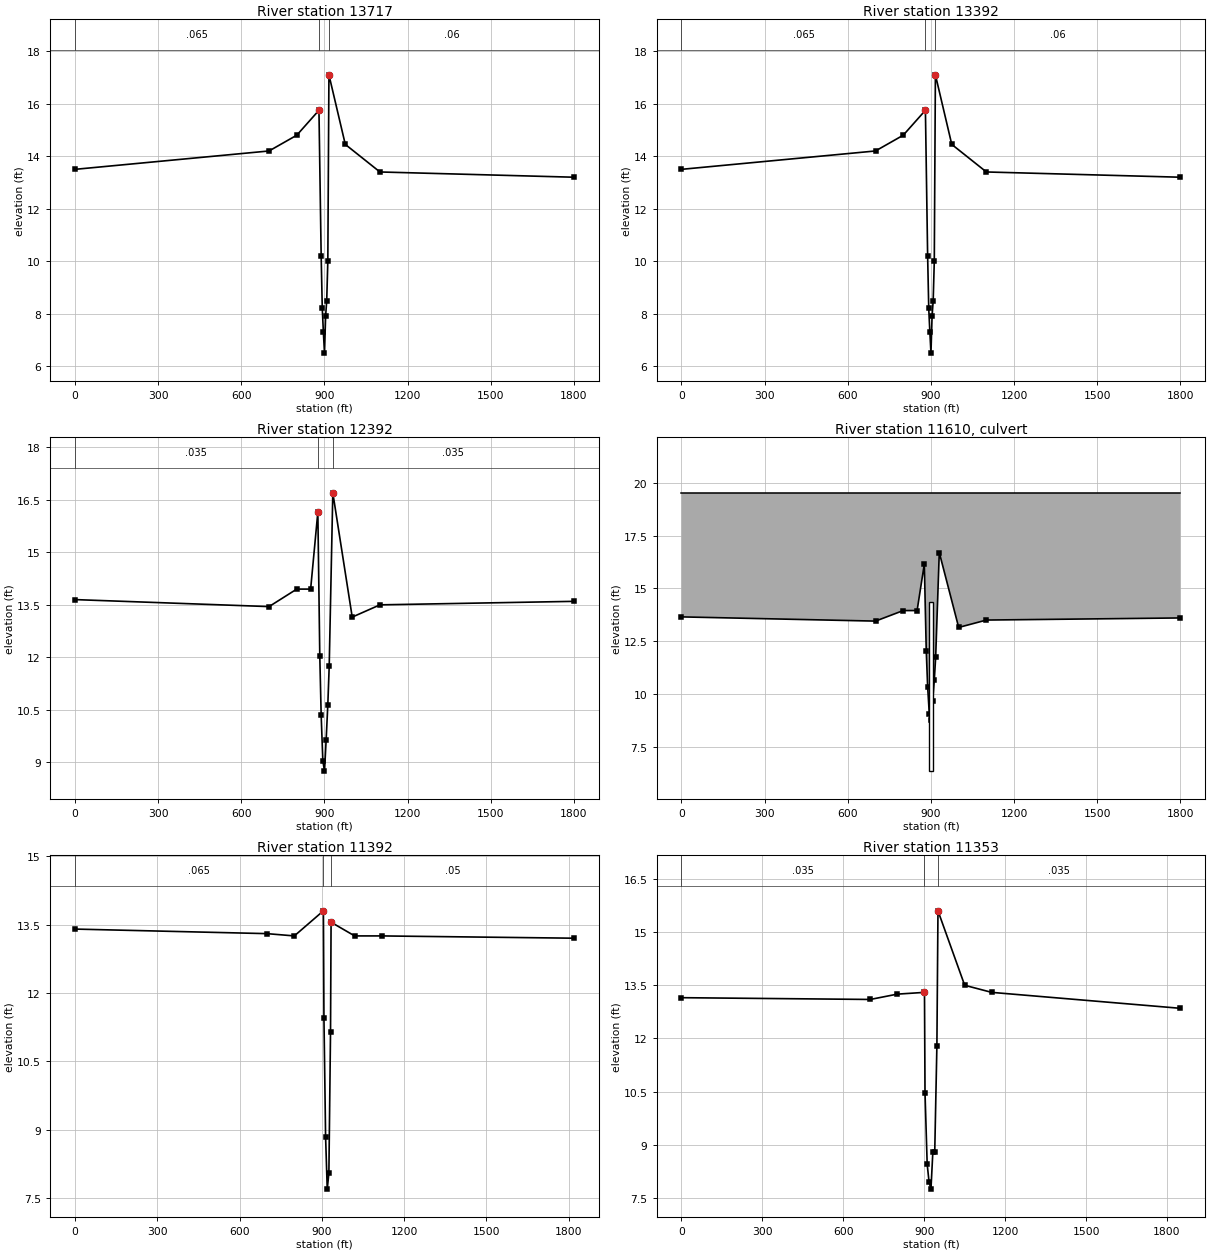
Type RM Length L Ch R =1,13717   ,425,425,425,0,0,0
Node Desc=13717
#Sta/Elev= 15
       0    13.5     700    14.2     800    14.8     880   15.75     888    10.2
     892     8.2     896     7.3     900     6.5     904     7.9     908     8.5
     912      10     916    17.1     975   14.45    1100    13.4    1800    13.2
#Mann=3,0
       0    .065       0     880     .07       0     916     .06       0
Bank Sta=880,916
Exp/Cntr=0.3,0.1

Type RM Length L Ch R =1,13392   ,1000,1000,1000,0,0,0
Node Desc=13392
#Sta/Elev= 15
       0    13.5     700    14.2     800    14.8     880   15.75     888    10.2
     892     8.2     896     7.3     900     6.5     904     7.9     908     8.5
     912      10     916    17.1     975   14.45    1100    13.4    1800    13.2
#Mann=3,0
       0    .065       0     880     .07       0     916     .06       0
Bank Sta=880,916
Exp/Cntr=0.3,0.1

Type RM Length L Ch R =1,12392   ,1000,1000,1000,0,0,0
Node Desc=12392
#Sta/Elev= 16
       0   13.65     700   13.45     800   13.95     850   13.95     876   16.15
     883   12.05     888   10.35     894    9.05     900    8.75     906    9.65
     912   10.65     917   11.75     930    16.7    1000   13.15    1100    13.5
    1800    13.6
#Mann=3,0
       0    .035       0     876     .07       0     930    .035       0
Bank Sta=876,930
Exp/Cntr=0.3,0.3

Type RM Length L Ch R =2,11610   ,,,,0,0,0
Node Desc=NORTH BOUND I-75
Bridge Culvert--1,0,-1,-1
Deck Dist Width WeirC Skew NumUp NumDn MinLoCord MaxHiCord MaxSubmerge Is_Ogee
747,90,2.6,,3,3,,,0.95,0
       0     900    1800
   19.53   19.53   19.53
                        
       0     900    1820
   19.53   19.53   19.53
                        
BR Coef= 1, 0, 0,, 0,,,,-1,0,1,
Culvert=2,8,12,126,0.013,0.5,0.5,10,1,6.34,900,6.34,920,Culvert #1  , 0

Type RM Length L Ch R =1,11392   ,39,39,39,0,0,0
Node Desc=11392
#Sta/Elev= 13
       0    13.4     700    13.3     800   13.25     906    13.8     908   11.45
     914    8.85     920     7.7     926    8.05     932   11.15     934   13.55
    1020   13.25    1120   13.25    1820    13.2
#Mann=3,0
       0    .065       0     906      .2       0     934     .05       0
Bank Sta=906,934
Exp/Cntr=0.3,0.5

Type RM Length L Ch R =1,11353   ,209,209,209,0,0,0
Node Desc=11353
#Sta/Elev= 15
       0   13.15     700    13.1     800   13.25     901    13.3     903   10.45
     911    8.45     918    7.95     925    7.75     932     8.8     939     8.8
     947    11.8     951    15.6    1050    13.5    1150    13.3    1850   12.85
#Mann=3,0
       0    .035       0     901     .05       0     951    .035       0
Bank Sta=901,951
Exp/Cntr=0.3,0.1

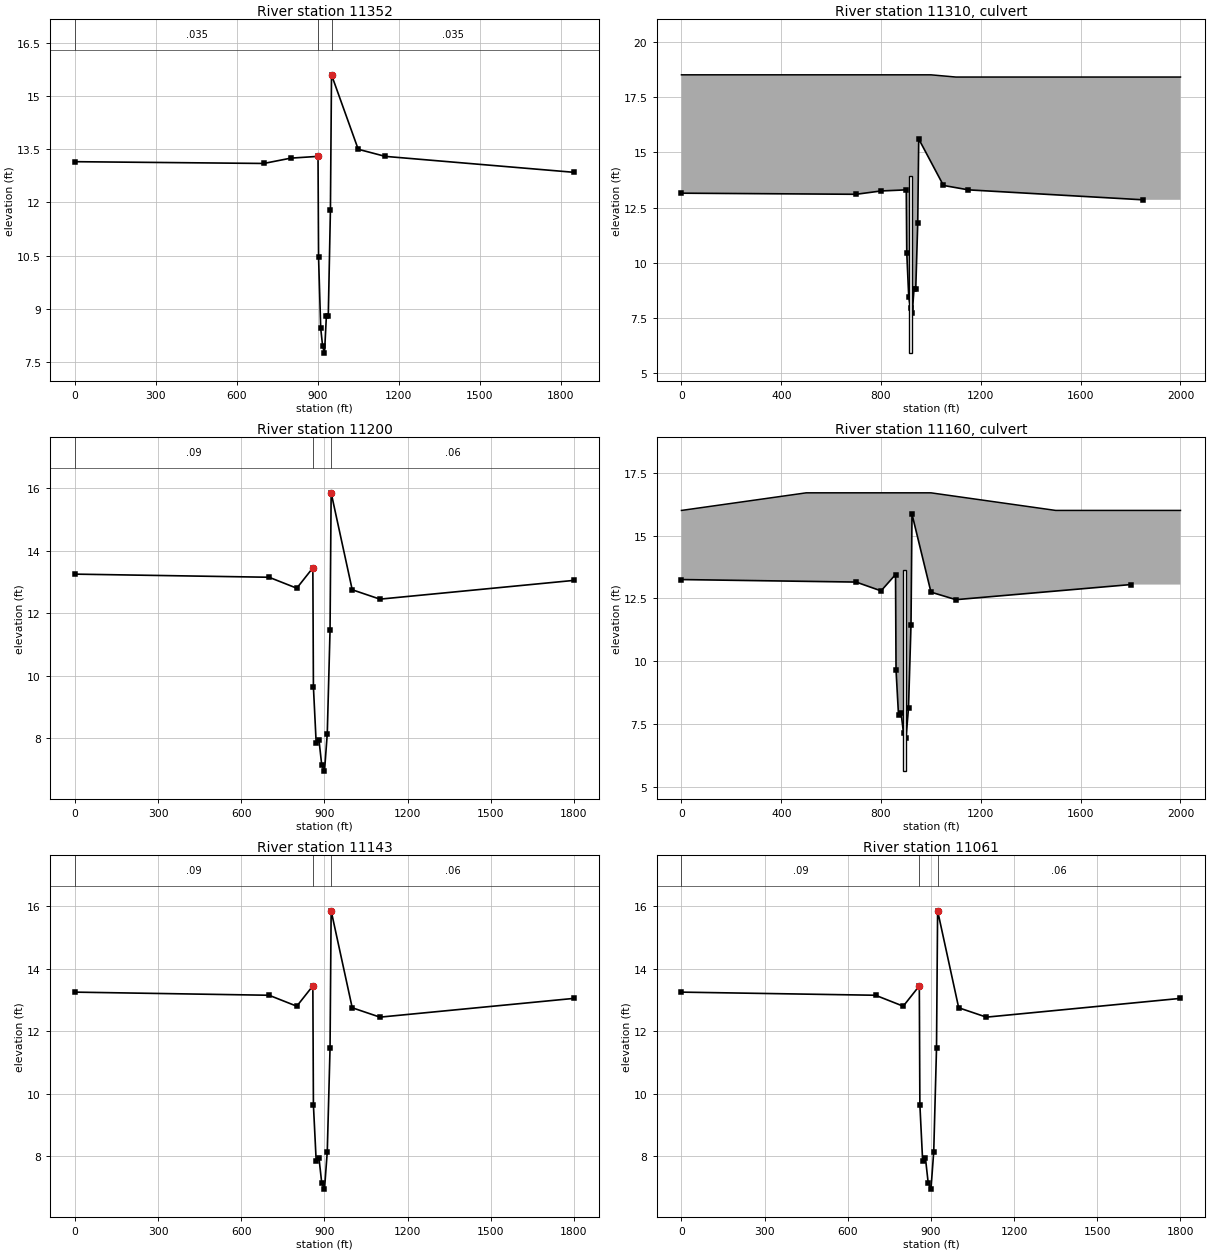
Type RM Length L Ch R =1,11352   ,209,209,209,0,0,0
Node Desc=11352
#Sta/Elev= 15
       0   13.15     700    13.1     800   13.25     901    13.3     903   10.45
     911    8.45     918    7.95     925    7.75     932     8.8     939     8.8
     947    11.8     951    15.6    1050    13.5    1150    13.3    1850   12.85
#Mann=3,0
       0    .035       0     901     .05       0     951    .035       0
Bank Sta=901,951
Exp/Cntr=0.3,0.1

Type RM Length L Ch R =2,11310   ,,,,0,0,0
Node Desc=SOUTH BOUND I-75
Bridge Culvert--1,0,-1,-1
Deck Dist Width WeirC Skew NumUp NumDn MinLoCord MaxHiCord MaxSubmerge Is_Ogee
0,90,2.6,,6,6,,,0.95,0
       0     700     900    1000    1100    2000
    18.5    18.5    18.5    18.5    18.4    18.4
                                                
       0     700     900    1000    1100    2000
    18.5    18.5    18.5    18.5    18.4    18.4
                                                
BR Coef= 1, 0, 0,, 0,,,,-1,0,1,
Culvert=2,8,12,124,0.013,0.5,0.5,10,1,5.92,918,5.92,918,STRUCTURE 8 , 0

Type RM Length L Ch R =1,11200   ,57,57,57,0,0,0
Node Desc=11200
#Sta/Elev= 15
       0   13.25     700   13.15     800    12.8     858   13.45     860    9.65
     870    7.85     880    7.95     890    7.15     900    6.95     910    8.15
     920   11.45     924   15.85    1000   12.75    1100   12.45    1800   13.05
#Mann=3,0
       0     .09       0     858     .05       0     924     .06       0
Bank Sta=858,924
Exp/Cntr=0.3,0.1

Type RM Length L Ch R =2,11160   ,,,,0,0,0
Node Desc=SOUTHERN PINES DRIVE
Bridge Culvert--1,0,-1,-1
Deck Dist Width WeirC Skew NumUp NumDn MinLoCord MaxHiCord MaxSubmerge Is_Ogee
1,45,2.7,,5,5,19.28,,0.95,0
       0     500    1000    1500    2000
      16    16.7    16.7      16      16
                                        
       0     500    1000    1500    2000
      16    16.7    16.7      16      16
                                        
BR Coef= 1, 0, 0,0, 0,,,,-1,2,1,13.62
Culvert=2,8,12,40,0.013,0.5,0.5,10,1,5.63,894,5.63,894,STURCTURE 7 , 0

Type RM Length L Ch R =1,11143   ,1,1,1,0,0,0
Node Desc=11143
#Sta/Elev= 15
       0   13.25     700   13.15     800    12.8     858   13.45     860    9.65
     870    7.85     880    7.95     890    7.15     900    6.95     910    8.15
     920   11.45     924   15.85    1000   12.75    1100   12.45    1800   13.05
#Mann=3,0
       0     .09       0     858     .05       0     924     .06       0
Bank Sta=858,924
Exp/Cntr=0.3,0.1

Type RM Length L Ch R =1,11061   ,1,1,1,0,0,0
Node Desc=11061
#Sta/Elev= 15
       0   13.25     700   13.15     800    12.8     858   13.45     860    9.65
     870    7.85     880    7.95     890    7.15     900    6.95     910    8.15
     920   11.45     924   15.85    1000   12.75    1100   12.45    1800   13.05
#Mann=3,0
       0     .09       0     858     .05       0     924     .06       0
Bank Sta=858,924
Exp/Cntr=0.3,0.1

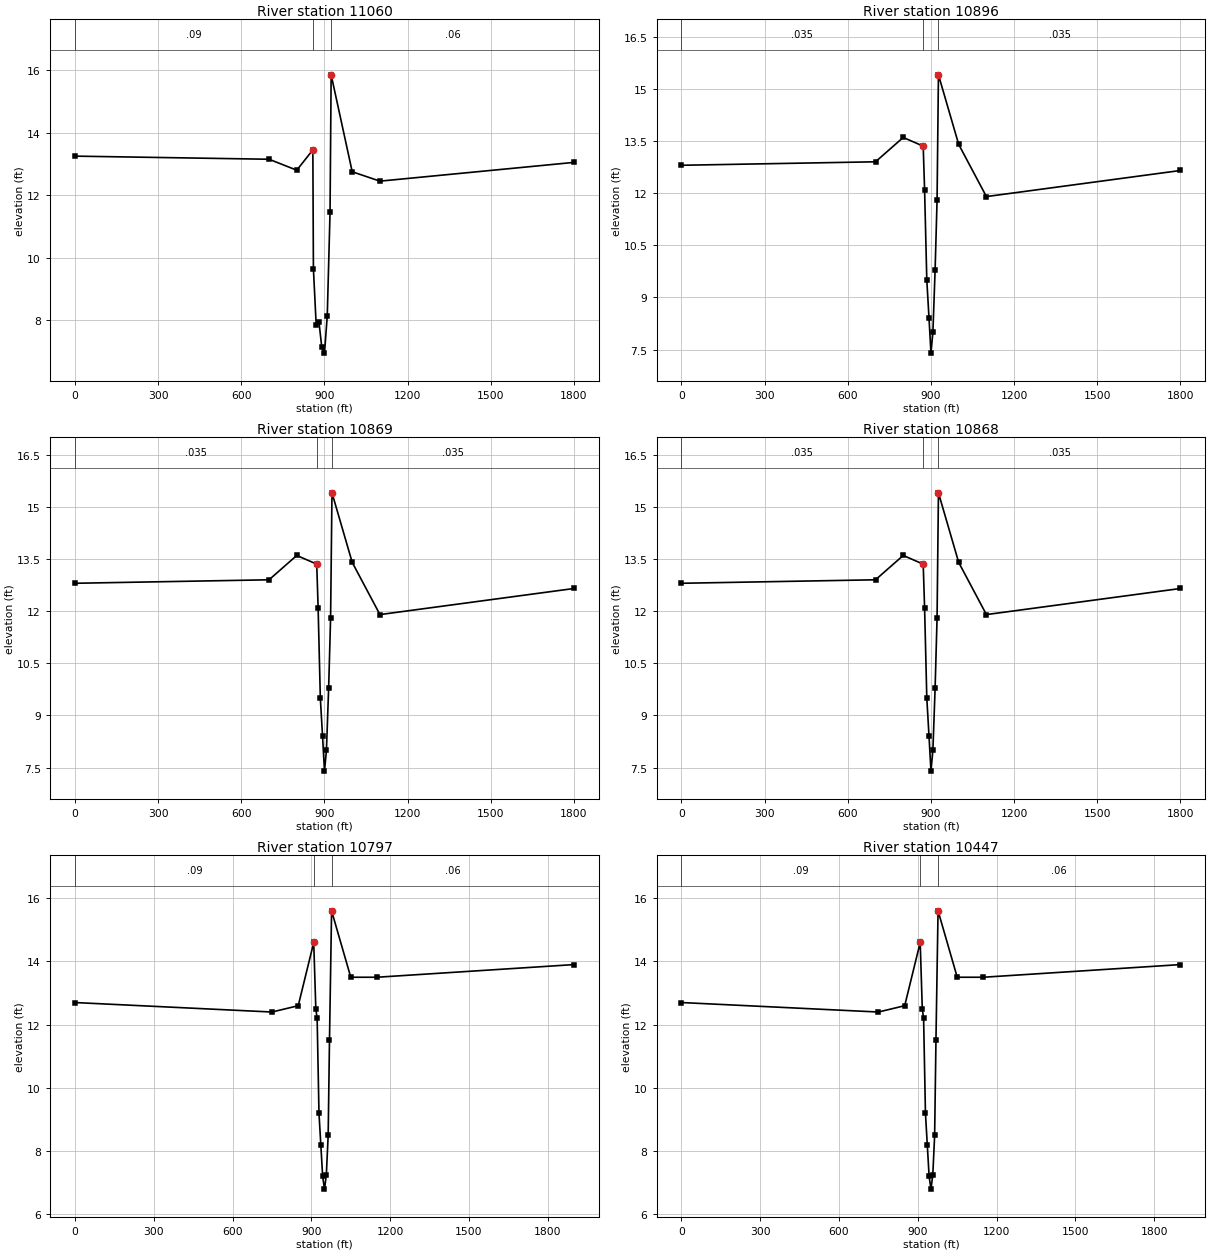
Type RM Length L Ch R =1,11060   ,164,164,164,0,0,0
Node Desc=11060
#Sta/Elev= 15
       0   13.25     700   13.15     800    12.8     858   13.45     860    9.65
     870    7.85     880    7.95     890    7.15     900    6.95     910    8.15
     920   11.45     924   15.85    1000   12.75    1100   12.45    1800   13.05
#Mann=3,0
       0     .09       0     858     .05       0     924     .06       0
Bank Sta=858,924
Exp/Cntr=0.3,0.1

Type RM Length L Ch R =1,10896   ,27,27,27,0,0,0
Node Desc=10896
#Sta/Elev= 15
       0    12.8     700    12.9     800    13.6     872   13.35     877    12.1
     885     9.5     893     8.4     900     7.4     907       8     915     9.8
     922    11.8     927    15.4    1000    13.4    1100    11.9    1800   12.65
#Mann=3,0
       0    .035       0     872      .1       0     927    .035       0
Bank Sta=872,927
Exp/Cntr=0.3,0.1

Type RM Length L Ch R =1,10869   ,1,1,1,0,0,0
Node Desc=10869
#Sta/Elev= 15
       0    12.8     700    12.9     800    13.6     872   13.35     877    12.1
     885     9.5     893     8.4     900     7.4     907       8     915     9.8
     922    11.8     927    15.4    1000    13.4    1100    11.9    1800   12.65
#Mann=3,0
       0    .035       0     872      .1       0     927    .035       0
Bank Sta=872,927
Exp/Cntr=0.3,0.1

Type RM Length L Ch R =1,10868   ,71,71,71,0,0,0
Node Desc=10868
#Sta/Elev= 15
       0    12.8     700    12.9     800    13.6     872   13.35     877    12.1
     885     9.5     893     8.4     900     7.4     907       8     915     9.8
     922    11.8     927    15.4    1000    13.4    1100    11.9    1800   12.65
#Mann=3,0
       0    .035       0     872      .1       0     927    .035       0
Bank Sta=872,927
Exp/Cntr=0.3,0.1

Type RM Length L Ch R =1,10797   ,1000,1000,1000,0,0,0
Node Desc=10797
#Sta/Elev= 17
       0    12.7     750    12.4     850    12.6     909    14.6     917    12.5
     922    12.2     929     9.2     936     8.2     943     7.2     950     6.8
     957    7.25     964     8.5     969    11.5     977    15.6    1050    13.5
    1150    13.5    1900    13.9
#Mann=3,0
       0     .09       0     909     .05       0     977     .06       0
Bank Sta=909,977
Exp/Cntr=0.3,0.1

Type RM Length L Ch R =1,10447   ,1000,1000,1000,0,0,0
Node Desc=10447
#Sta/Elev= 17
       0    12.7     750    12.4     850    12.6     909    14.6     917    12.5
     922    12.2     929     9.2     936     8.2     943     7.2     950     6.8
     957    7.25     964     8.5     969    11.5     977    15.6    1050    13.5
    1150    13.5    1900    13.9
#Mann=3,0
       0     .09       0     909     .05       0     977     .06       0
Bank Sta=909,977
Exp/Cntr=0.3,0.1

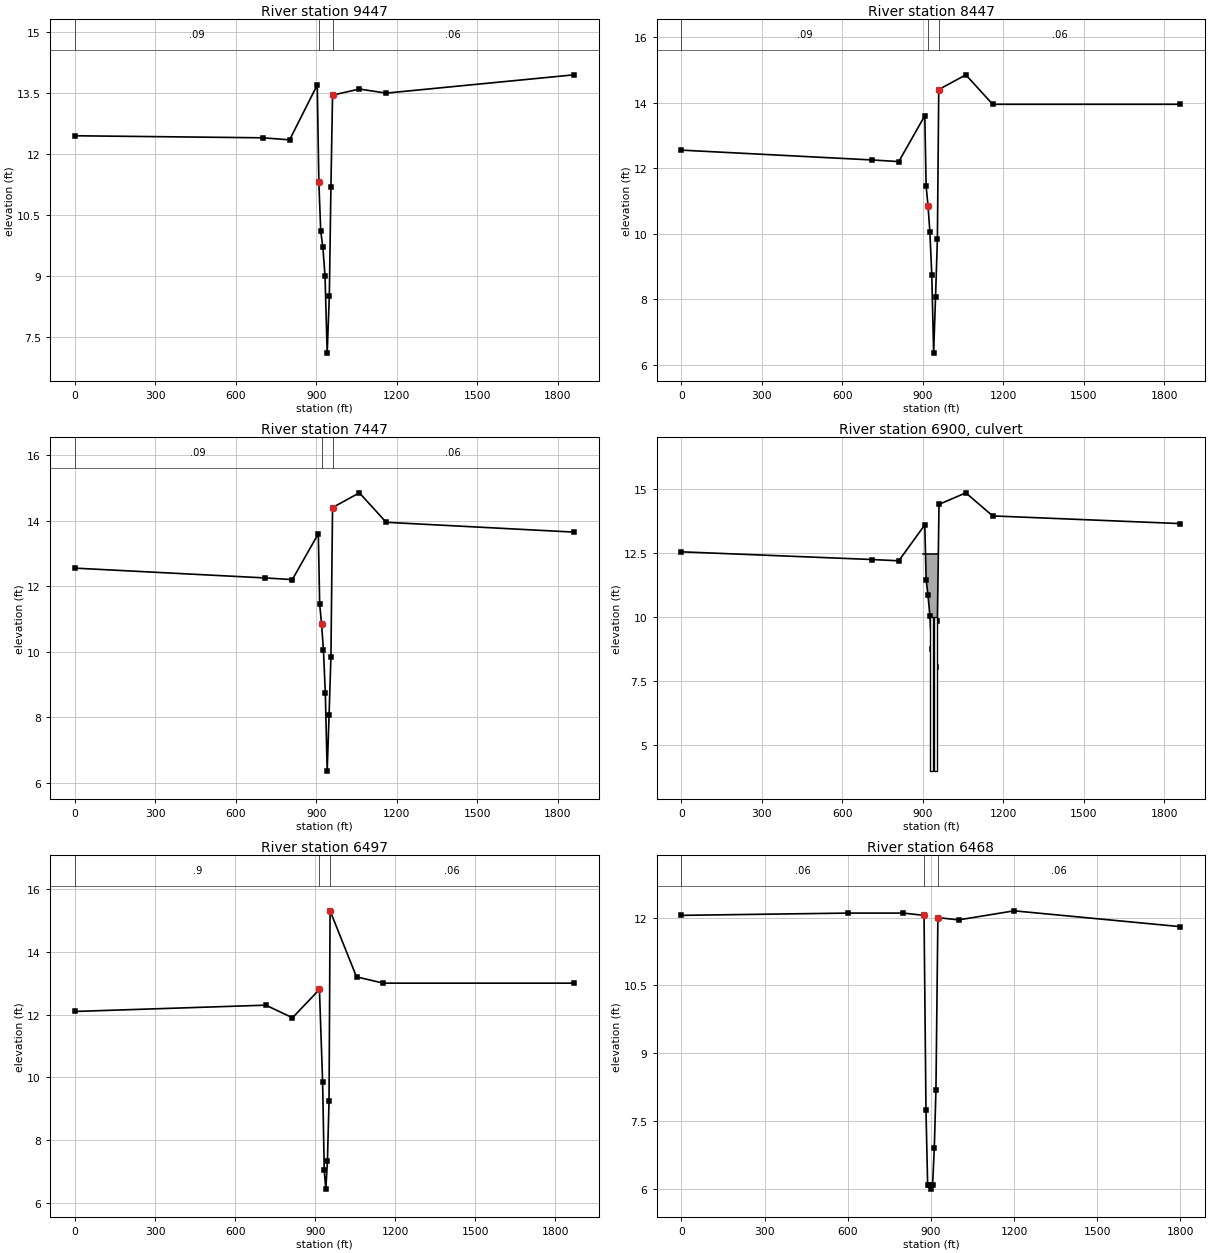
Type RM Length L Ch R =1,9447    ,1000,1000,1000,0,0,0
Node Desc=9447
#Sta/Elev= 15
       0   12.45     700    12.4     800   12.35     903    13.7     909    11.3
     916    10.1     924     9.7     932       9     940     7.1     948     8.5
     954    11.2     960   13.45    1060    13.6    1160    13.5    1860   13.95
#Mann=3,0
       0     .09       0     909     .05       0     960     .06       0
Bank Sta=909,960
Exp/Cntr=0.3,0.1

Type RM Length L Ch R =1,8447    ,1000,1000,1000,0,0,0
Node Desc=8447
#Sta/Elev= 15
       0   12.55     710   12.25     810    12.2     907    13.6     912   11.45
     919   10.85     926   10.05     933    8.75     940    6.35     947    8.05
     954    9.85     959    14.4    1060   14.85    1160   13.95    1860   13.95
#Mann=3,0
       0     .09       0     919     .05       0     959     .06       0
Bank Sta=919,959
Exp/Cntr=0.3,0.1

Type RM Length L Ch R =1,7447    ,950,950,950,0,0,0
Node Desc=7447
#Sta/Elev= 15
       0   12.55     710   12.25     810    12.2     907    13.6     912   11.45
     919   10.85     926   10.05     933    8.75     940    6.35     947    8.05
     954    9.85     960    14.4    1060   14.85    1160   13.95    1860   13.65
#Mann=3,0
       0     .09       0     919     .05       0     960     .06       0
Bank Sta=919,960
Exp/Cntr=0.3,0.1

Type RM Length L Ch R =2,6900    ,,,,0,0,0
Node Desc=WAGON TRAIL
Bridge Culvert--1,0,-1,-1
Deck Dist Width WeirC Skew NumUp NumDn MinLoCord MaxHiCord MaxSubmerge Is_Ogee
497,50,2.7,,2,2,19.28,,0.95,0
     900     955
   12.48   12.48
                
     915     952
   12.48   12.48
                
BR Coef= 1, 0, 0,0, 0,,,,-1,2,1,
Multiple Barrel Culv=2,6,12,49,0.013,0.5,0.5,8,1,4,4, 2,WAGON TRAIL , 0
     932     932     948     948

Type RM Length L Ch R =1,6497    ,29,29,29,0,0,0
Node Desc=6497
#Sta/Elev= 13
       0    12.1     715    12.3     815    11.9     916    12.8     928    9.85
     934    7.05     940    6.45     946    7.35     952    9.25     956    15.3
    1055    13.2    1155      13    1870      13
#Mann=3,0
       0      .9       0     916    .012       0     956     .06       0
Bank Sta=916,956
Exp/Cntr=0.5,0.3

Type RM Length L Ch R =1,6468    ,1,1,1,0,0,0
Node Desc=6468
#Sta/Elev= 15
       0   12.05     600    12.1     800    12.1     875   12.05     882    7.75
     888     6.1     894     6.1     900       6     906     6.1     912     6.9
     918     8.2     925      12    1000   11.95    1200   12.15    1800    11.8
#Mann=3,0
       0     .06       0     875     .05       0     925     .06       0
Bank Sta=875,925
Exp/Cntr=0.3,0.1

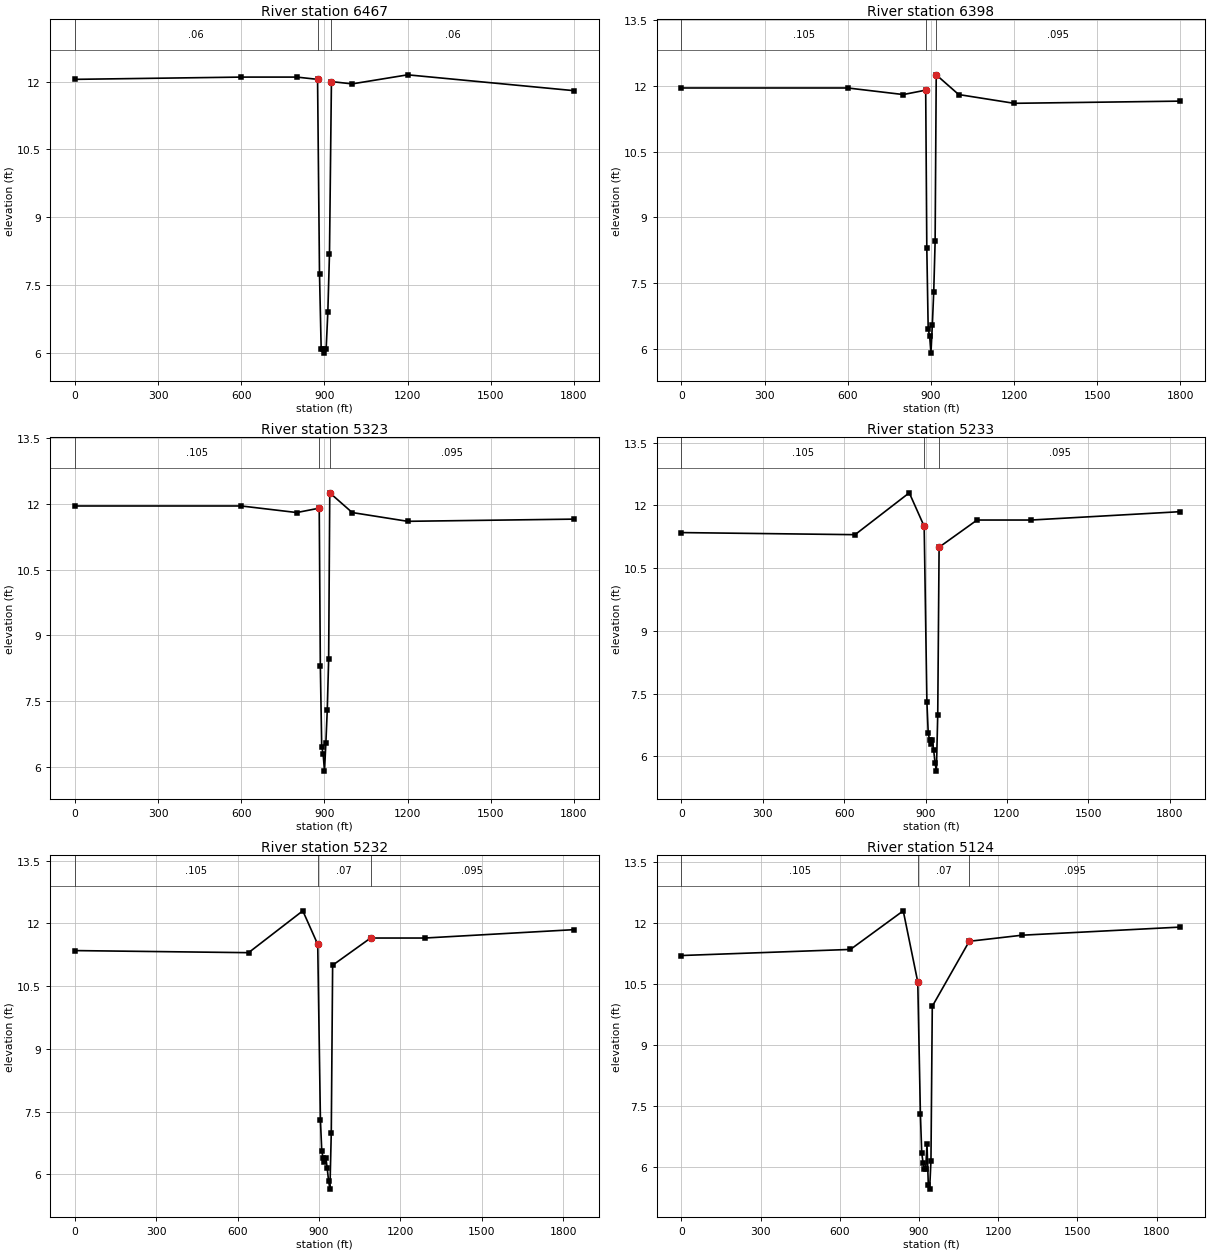
Type RM Length L Ch R =1,6467    ,69,69,69,0,0,0
Node Desc=6467
#Sta/Elev= 15
       0   12.05     600    12.1     800    12.1     875   12.05     882    7.75
     888     6.1     894     6.1     900       6     906     6.1     912     6.9
     918     8.2     925      12    1000   11.95    1200   12.15    1800    11.8
#Mann=3,0
       0     .06       0     875     .05       0     925     .06       0
Bank Sta=875,925
Exp/Cntr=0.3,0.1

Type RM Length L Ch R =1,6398    ,1075,1075,1075,0,0,0
Node Desc=5323
#Sta/Elev= 15
       0   11.95     600   11.95     800    11.8     881    11.9     885     8.3
     890    6.45     895     6.3     900     5.9     905    6.55     910     7.3
     915    8.45     919   12.25    1000    11.8    1200    11.6    1800   11.65
#Mann=3,0
       0    .105       0     881    .012       0     919    .095       0
Bank Sta=881,919
Exp/Cntr=0.5,0.3

Type RM Length L Ch R =1,5323    ,90,90,90,0,0,0
Node Desc=5323
#Sta/Elev= 15
       0   11.95     600   11.95     800    11.8     881    11.9     885     8.3
     890    6.45     895     6.3     900     5.9     905    6.55     910     7.3
     915    8.45     919   12.25    1000    11.8    1200    11.6    1800   11.65
#Mann=3,0
       0    .105       0     881    .012       0     919    .095       0
Bank Sta=881,919
Exp/Cntr=0.5,0.3

Type RM Length L Ch R =1,5233    ,1,1,1,0,0,0
Node Desc=5232
#Sta/Elev= 17
       0   11.35     640    11.3     840    12.3     895    11.5     905     7.3
     910    6.55     915     6.4     920     6.3     925     6.4     930    6.15
     935    5.85     940    5.65     945       7     950      11    1090   11.65
    1290   11.65    1840   11.85
#Mann=3,0
       0    .105       0     895     .07       0     950    .095       0
Bank Sta=895,950
Exp/Cntr=0.3,0.1

Type RM Length L Ch R =1,5232    ,108,108,108,0,0,0
Node Desc=5232
#Sta/Elev= 17
       0   11.35     640    11.3     840    12.3     895    11.5     905     7.3
     910    6.55     915     6.4     920     6.3     925     6.4     930    6.15
     935    5.85     940    5.65     945       7     950      11    1090   11.65
    1290   11.65    1840   11.85
#Mann=3,0
       0    .105       0     895     .07       0    1090    .095       0
Bank Sta=895,1090
Exp/Cntr=0.3,0.1

Type RM Length L Ch R =1,5124    ,524,524,524,0,0,0
Node Desc=5124
#Sta/Elev= 17
       0    11.2     640   11.35     840    12.3     895   10.55     905     7.3
     910    6.35     915     6.1     920    5.95     925    5.95     930    6.55
     935    5.55     940    5.45     945    6.15     950    9.95    1090   11.55
    1290    11.7    1890    11.9
#Mann=3,0
       0    .105       0     895     .07       0    1090    .095       0
Bank Sta=895,1090
Exp/Cntr=0.3,0.1

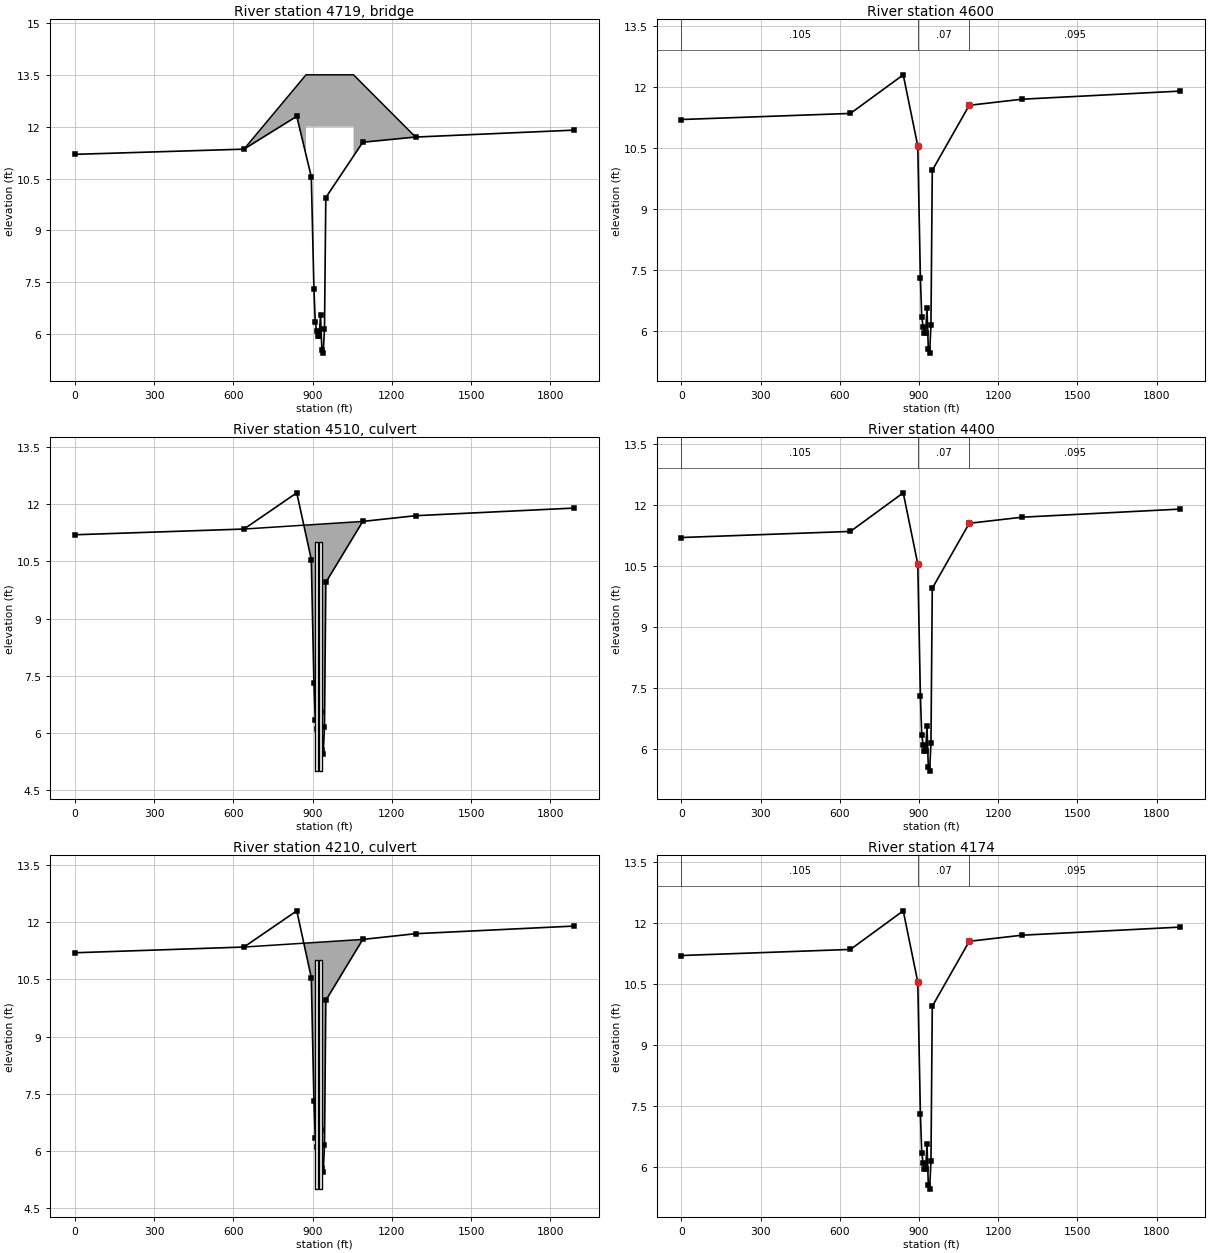
Type RM Length L Ch R =3,4719    ,,,,0,0,0
Node Desc=FOOT BRIDGE (SPANISH GARDENS)
Bridge Culvert--1,0,-1,-1
Deck Dist Width WeirC Skew NumUp NumDn MinLoCord MaxHiCord MaxSubmerge Is_Ogee
399,6,2.7,,4,4,16.62,,0.95,0
     640     875    1055    1290
   11.35    13.5    13.5    11.7
              12      12
     640     875    1055    1290
   11.35    13.5    13.5    11.7
              12      12
BR Coef= 1, 0, 0,0, 0,,,,-1,2,1,

Type RM Length L Ch R =1,4600    ,200,200,200,0,0,0
Node Desc=4600
#Sta/Elev= 17
       0    11.2     640   11.35     840    12.3     895   10.55     905     7.3
     910    6.35     915     6.1     920    5.95     925    5.95     930    6.55
     935    5.55     940    5.45     945    6.15     950    9.95    1090   11.55
    1290    11.7    1890    11.9
#Mann=3,0
       0    .105       0     895     .07       0    1090    .095       0
Bank Sta=895,1090
Exp/Cntr=0.3,0.1

Type RM Length L Ch R =2,4510    ,,,,0,0,0
Node Desc=TRAILER PARK BRIDGE (WOOD)
Bridge Culvert--1,0,-1,-1
Deck Dist Width WeirC Skew NumUp NumDn MinLoCord MaxHiCord MaxSubmerge Is_Ogee
69,21,2.7,,2,2,11.7,,0.95,0
     640    1090
   11.35   11.55
                
     640    1090
   11.35   11.55
                
BR Coef= 1, 0, 0,1.25, 0,,,,-1,2,1,
Multiple Barrel Culv=2,6,12,20,0.013,1,1,8,1,5,5, 2,Culvert #1  , 0
     915     915     930     930

Type RM Length L Ch R =1,4400    ,226,226,226,0,0,0
Node Desc=4400
#Sta/Elev= 17
       0    11.2     640   11.35     840    12.3     895   10.55     905     7.3
     910    6.35     915     6.1     920    5.95     925    5.95     930    6.55
     935    5.55     940    5.45     945    6.15     950    9.95    1090   11.55
    1290    11.7    1890    11.9
#Mann=3,0
       0    .105       0     895     .07       0    1090    .095       0
Bank Sta=895,1090
Exp/Cntr=0.3,0.1

Type RM Length L Ch R =2,4210    ,,,,0,0,0
Node Desc=TRAILER PARK BRIDGE (R.C.)
Bridge Culvert--1,0,-1,-1
Deck Dist Width WeirC Skew NumUp NumDn MinLoCord MaxHiCord MaxSubmerge Is_Ogee
179,21,2.7,,2,2,10.75,,0.95,0
     640    1090
   11.35   11.55
                
     640    1090
   11.35   11.55
                
BR Coef= 1, 0, 0,1.25, 0,,,,-1,2,1,
Multiple Barrel Culv=2,6,12,10,0.013,1,1,8,1,5,5, 2,Culvert #1  , 0
     914     914     930     930

Type RM Length L Ch R =1,4174    ,40,40,40,0,0,0
Node Desc=4174
#Sta/Elev= 17
       0    11.2     640   11.35     840    12.3     895   10.55     905     7.3
     910    6.35     915     6.1     920    5.95     925    5.95     930    6.55
     935    5.55     940    5.45     945    6.15     950    9.95    1090   11.55
    1290    11.7    1890    11.9
#Mann=3,0
       0    .105       0     895     .07       0    1090    .095       0
Bank Sta=895,1090
Exp/Cntr=0.3,0.1

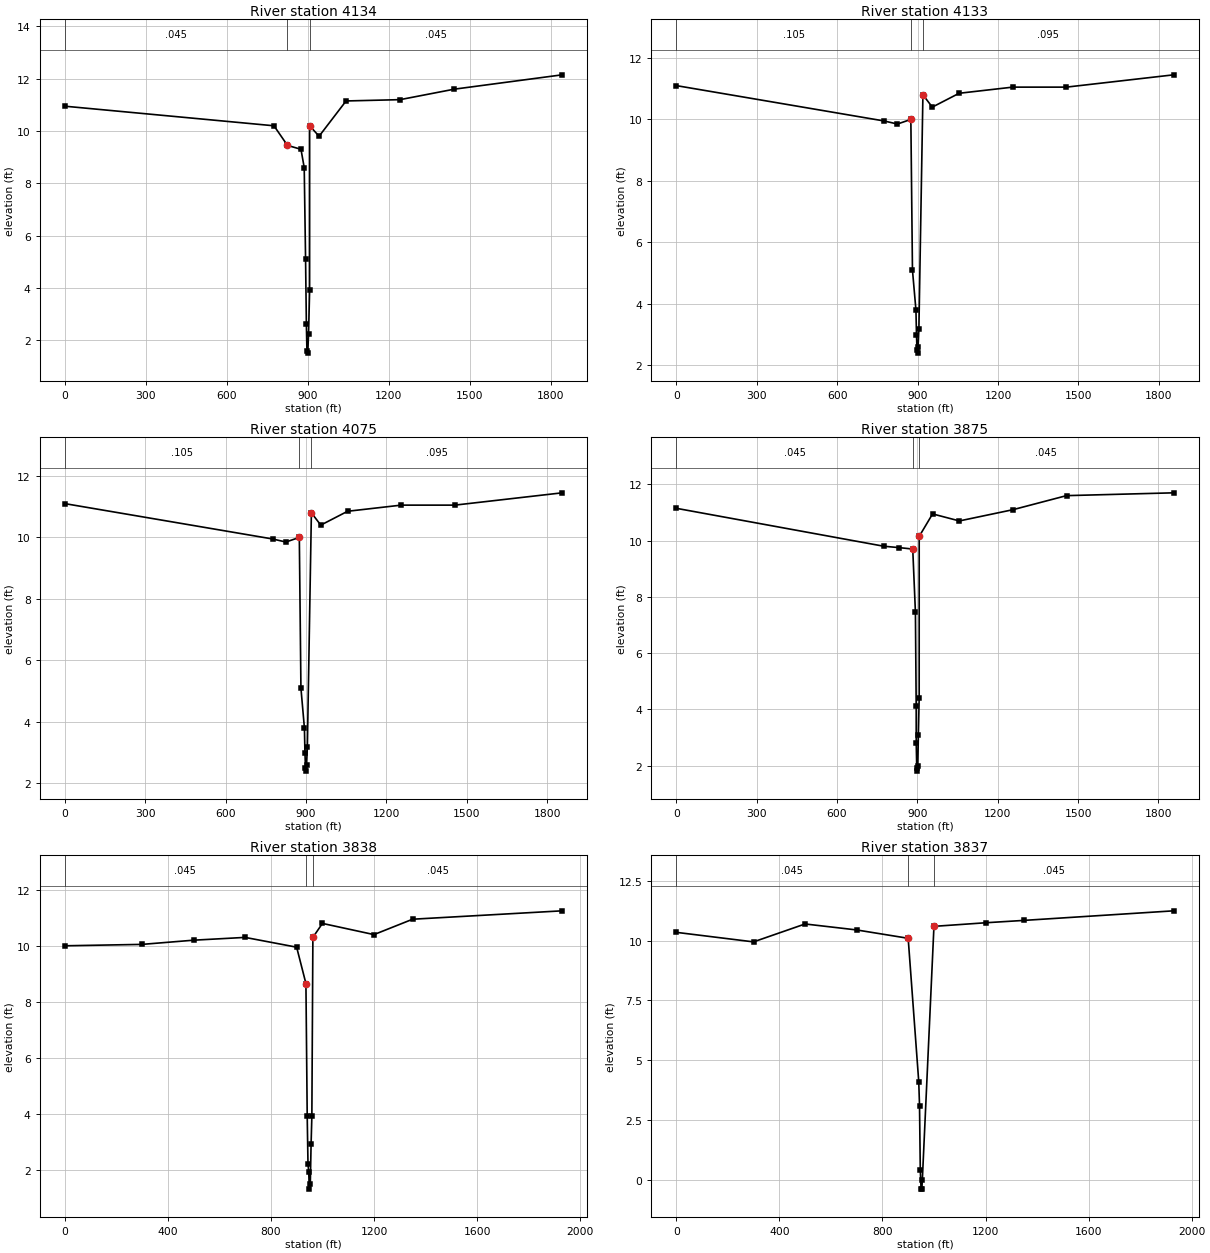
Type RM Length L Ch R =1,4134    ,1,1,1,0,0,0
Node Desc=4134
#Sta/Elev= 17
       0   10.95     775    10.2     825    9.45     875     9.3     887     8.6
     892     5.1     895     2.6     897     1.6     900     1.5     903    2.22
     907     3.9   907.1    10.2     942     9.8    1042   11.15    1242    11.2
    1442    11.6    1842   12.15
#Mann=3,0
       0    .045       0     825     .07       0   907.1    .045       0
Bank Sta=825,907.1
Exp/Cntr=0.3,0.1

Type RM Length L Ch R =1,4133    ,58,58,58,0,0,0
Node Desc=4133
#Sta/Elev= 17
       0    11.1     775    9.95     825    9.85     875      10     881     5.1
     894     3.8     896       3     898     2.5     900     2.4     902     2.6
     905     3.2     920    10.8     955    10.4    1055   10.85    1255   11.05
    1455   11.05    1855   11.45
#Mann=3,0
       0    .105       0     875     .07       0     920    .095       0
Bank Sta=875,920
Exp/Cntr=0.3,0.1

Type RM Length L Ch R =1,4075    ,200,200,200,0,0,0
Node Desc=4075
#Sta/Elev= 17
       0    11.1     775    9.95     825    9.85     875      10     881     5.1
     894     3.8     896       3     898     2.5     900     2.4     902     2.6
     905     3.2     920    10.8     955    10.4    1055   10.85    1255   11.05
    1455   11.05    1855   11.45
#Mann=3,0
       0    .105       0     875     .07       0     920    .095       0
Bank Sta=875,920
Exp/Cntr=0.3,0.1

Type RM Length L Ch R =1,3875    ,37,37,37,0,0,0
Node Desc=3875
#Sta/Elev= 18
       0   11.15     775     9.8     833    9.75     883     9.7     893    7.45
   895.9     4.1     896     2.8     898     1.9     900     1.8     902       2
     904     3.1     907     4.4   907.1   10.15     957   10.95    1057    10.7
    1257    11.1    1457    11.6    1857    11.7
#Mann=3,0
       0    .045       0     883     .07       0   907.1    .045       0
Bank Sta=883,907.1
Exp/Cntr=0.3,0.1

Type RM Length L Ch R =1,3838    ,1,1,1,0,0,0
Node Desc=3838
#Sta/Elev= 18
       0      10     300   10.05     500    10.2     700    10.3     900    9.95
     936    8.65     941     3.9     944     2.2     947     1.9     949     1.3
     953     1.5     956     2.9     959     3.9     963    10.3    1000    10.8
    1200    10.4    1350   10.95    1930   11.25
#Mann=3,0
       0    .045       0     936     .07       0     963    .045       0
Bank Sta=936,963
Exp/Cntr=0.1,0.3

Type RM Length L Ch R =1,3837    ,750,750,750,0,0,0
Node Desc=3837
#Sta/Elev= 15
       0   10.35     300    9.95     500    10.7     700   10.45     900    10.1
     941     4.1     944     3.1     947      .4     950     -.4     953     -.4
     955       0    1000    10.6    1200   10.75    1350   10.85    1930   11.25
#Mann=3,0
       0    .045       0     900     .07       0    1000    .045       0
Bank Sta=900,1000
Exp/Cntr=0.3,0.1

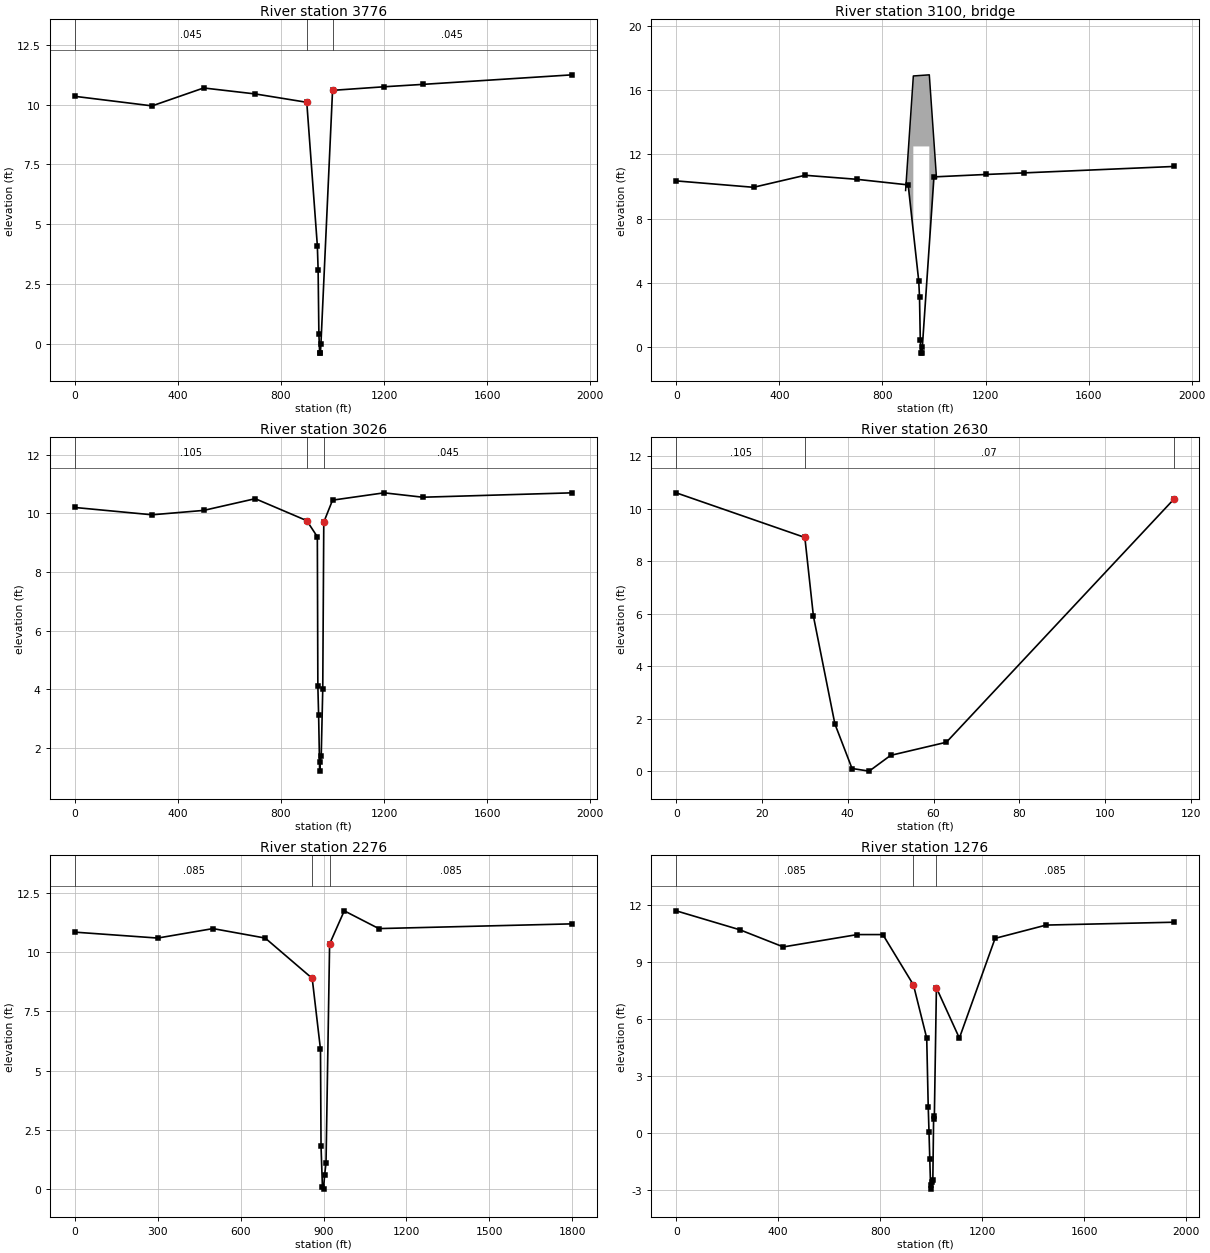
Type RM Length L Ch R =1,3776    ,750,750,750,0,0,0
Node Desc=3776
#Sta/Elev= 15
       0   10.35     300    9.95     500    10.7     700   10.45     900    10.1
     941     4.1     944     3.1     947      .4     950     -.4     953     -.4
     955       0    1000    10.6    1200   10.75    1350   10.85    1930   11.25
#Mann=3,0
       0    .045       0     900     .07       0    1000    .045       0
Bank Sta=900,1000
Exp/Cntr=0.3,0.1

Type RM Length L Ch R =3,3100    ,,,,0,0,0
Node Desc=EAST TERRY ST. BRIDGE
Bridge Culvert--1,0,-1,-1
Deck Dist Width WeirC Skew NumUp NumDn MinLoCord MaxHiCord MaxSubmerge Is_Ogee
620,35,2.7,,4,4,10.77,,0.95,0
     890     920     982    1010
    9.75    16.9   16.97    10.5
            12.5    12.5
     893     920     982    1010
    10.6    16.9   16.97   10.35
            12.5    12.5
BR Coef= 1, 0, 0,0, 0,,,,-1,2,1,

Type RM Length L Ch R =1,3026    ,396,396,396,0,0,0
Node Desc=3026
#Sta/Elev= 17
       0    10.2     300    9.95     500    10.1     700    10.5     900    9.75
     941     9.2     943     4.1     946     3.1     950     1.2     952     1.5
     956     1.7     962       4     966     9.7    1000   10.45    1200    10.7
    1350   10.55    1930    10.7
#Mann=3,0
       0    .105       0     900     .07       0     966    .045       0
Bank Sta=900,966
Exp/Cntr=0.3,0.1

Type RM Length L Ch R =1,2630    ,354,354,354,0,0,0
Node Desc= 2630
#Sta/Elev= 9
       0    10.6      30     8.9      32     5.9      37     1.8      41      .1
      45       0      50      .6      63     1.1     116   10.35
#Mann=3,0
       0    .105       0      30     .07       0     116    .085       0
Bank Sta=30,116
Exp/Cntr=0.3,0.1

Type RM Length L Ch R =1,2276    ,1000,1000,1000,0,0,0
Node Desc=2276
#Sta/Elev= 15
       0   10.85     300    10.6     500      11     689    10.6     859     8.9
     889     5.9     891     1.8     896      .1     900       0     904      .6
     909     1.1     922   10.35     975   11.75    1100      11    1800    11.2
#Mann=3,0
       0    .085       0     859    .065       0     922    .085       0
Bank Sta=859,922
Exp/Cntr=0.3,0.1

Type RM Length L Ch R =1,1276    ,900,900,900,0,0,0
Node Desc=1276
#Sta/Elev= 21
       0    11.7     250    10.7     420     9.8     710   10.45     810   10.45
     930     7.8     982       5     988    1.35     991     .05     994   -1.35
     997   -2.75    1000   -2.95    1003   -2.55    1006   -2.45    1009     .75
    1012      .9    1020    7.65    1110       5    1250   10.25    1450   10.95
    1950    11.1
#Mann=3,0
       0    .085       0     930    .065       0    1020    .085       0
Bank Sta=930,1020
Exp/Cntr=0.3,0.1