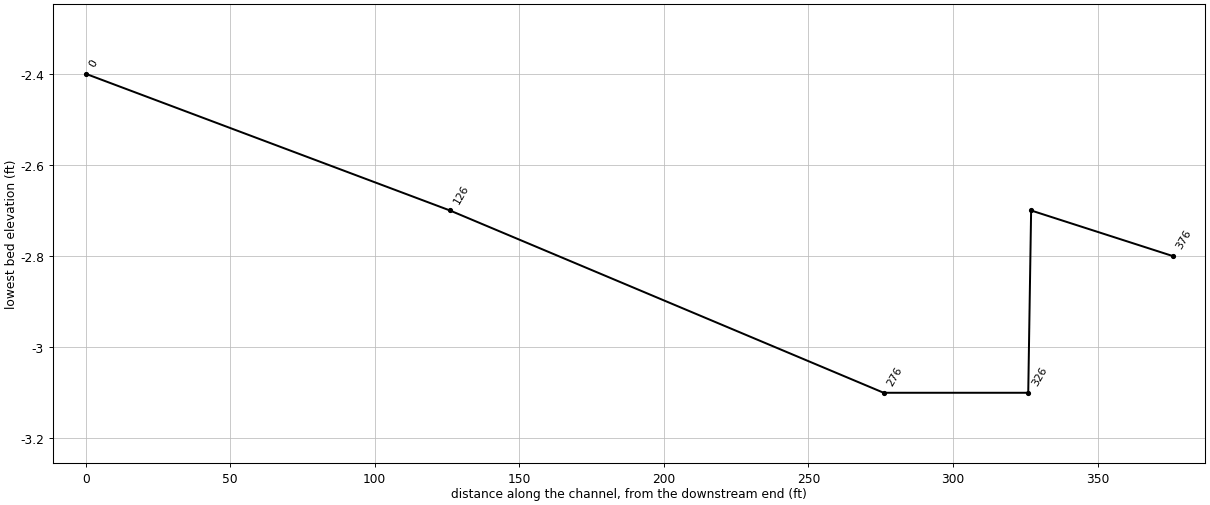
HEC-RAS study leitnrpr.prj: PROPOSED LEITNER CREEK

--- leitnrpr.g02 (geometry) --- (continued)

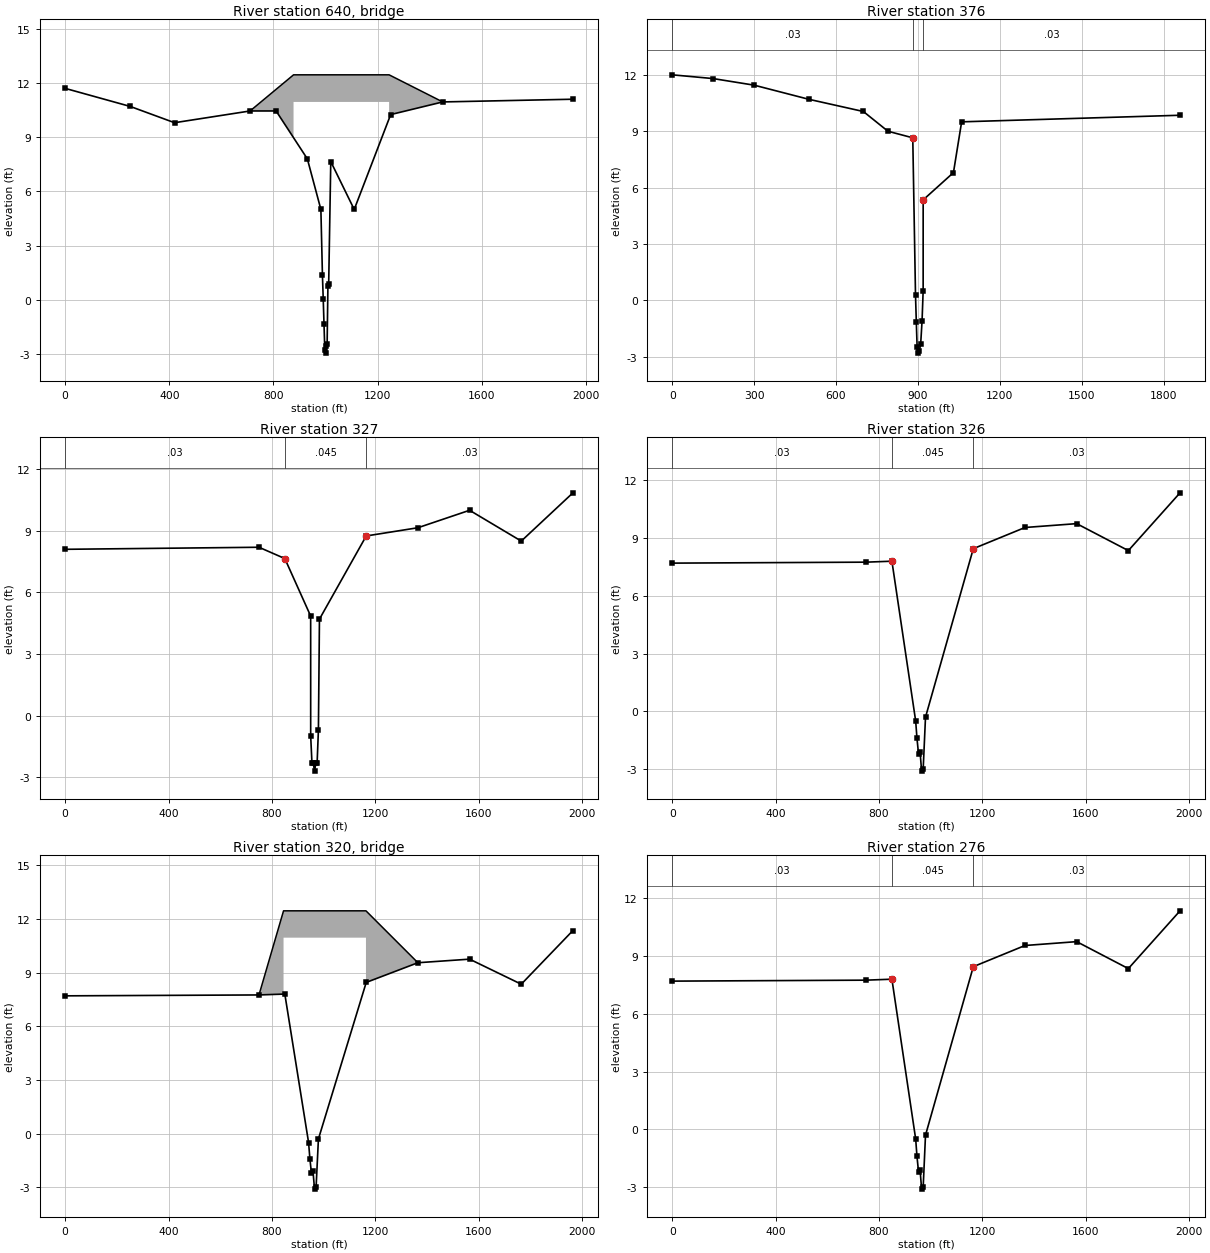
Type RM Length L Ch R =3,640     ,,,,0,0,0
Node Desc=PRIVATE DRIVE BRIDGE
Bridge Culvert--1,0,-1,-1
Deck Dist Width WeirC Skew NumUp NumDn MinLoCord MaxHiCord MaxSubmerge Is_Ogee
626,10,2.7,,4,4,8.3,,0.95,0
     710     877    1244    1450
   10.45   12.45   12.45   10.95
           10.95   10.95
     710     850    1054    1450
   10.45   12.45   12.45     9.8
           10.95   10.95
BR Coef= 1, 0, 0,, 0,,,,-1,0,1,

Type RM Length L Ch R =1,376     ,49,49,49,0,0,0
Node Desc=376
#Sta/Elev= 19
       0      12     150    11.8     300   11.45     500    10.7     700   10.05
     790       9     881    8.65     891      .3     894   -1.16     897    -2.5
     900    -2.8     905    -2.7     910    -2.3     915    -1.1     919      .5
   919.1    5.35    1030     6.8    1060     9.5    1860    9.85
#Mann=3,0
       0     .03       0     881    .045       0   919.1     .03       0
Bank Sta=881,919.1
Exp/Cntr=0.3,0.1

Type RM Length L Ch R =1,327     ,1,1,1,0,0,0
Node Desc=327
#Sta/Elev= 17
       0     8.1     750     8.2     850    7.65     950    4.85   950.1      -1
     955    -2.3     960    -2.3     965    -2.7     970    -2.3     975    -2.3
     980     -.7     984     4.7    1165    8.75    1365    9.15    1565      10
    1765     8.5    1965   10.85
#Mann=3,0
       0     .03       0     850    .045       0    1165     .03       0
Bank Sta=850,1165
Exp/Cntr=0.5,0.3

Type RM Length L Ch R =1,326     ,50,50,50,0,0,0
Node Desc=326
#Sta/Elev= 15
       0     7.7     750    7.75     850     7.8     942     -.5     947    -1.4
     953    -2.2     959    -2.1     965    -3.1     971      -3     980     -.3
    1165    8.45    1365    9.55    1565    9.75    1765    8.35    1965   11.35
#Mann=3,0
       0     .03       0     850    .045       0    1165     .03       0
Bank Sta=850,1165
Exp/Cntr=0.5,0.3

Type RM Length L Ch R =3,320     ,,,,0,0,0
Node Desc=GOODWIN ST. BRIDGE
Bridge Culvert--1,0,-1,-1
Deck Dist Width WeirC Skew NumUp NumDn MinLoCord MaxHiCord MaxSubmerge Is_Ogee
0,38,2.7,,4,4,8.3,,0.95,0
     750     845    1164    1365
    7.75   12.45   12.45    9.55
           10.95   10.95
     750     845    1164    1365
    7.75   12.45   12.45    9.55
           10.95   10.95
BR Coef= 1, 0, 0,0, 0,,,,-1,2,1,

Type RM Length L Ch R =1,276     ,150,150,150,0,0,0
Node Desc=276
#Sta/Elev= 15
       0     7.7     750    7.75     850     7.8     942     -.5     947    -1.4
     953    -2.2     959    -2.1     965    -3.1     971      -3     980     -.3
    1165    8.45    1365    9.55    1565    9.75    1765    8.35    1965   11.35
#Mann=3,0
       0     .03       0     850    .045       0    1165     .03       0
Bank Sta=850,1165
Exp/Cntr=0.5,0.3

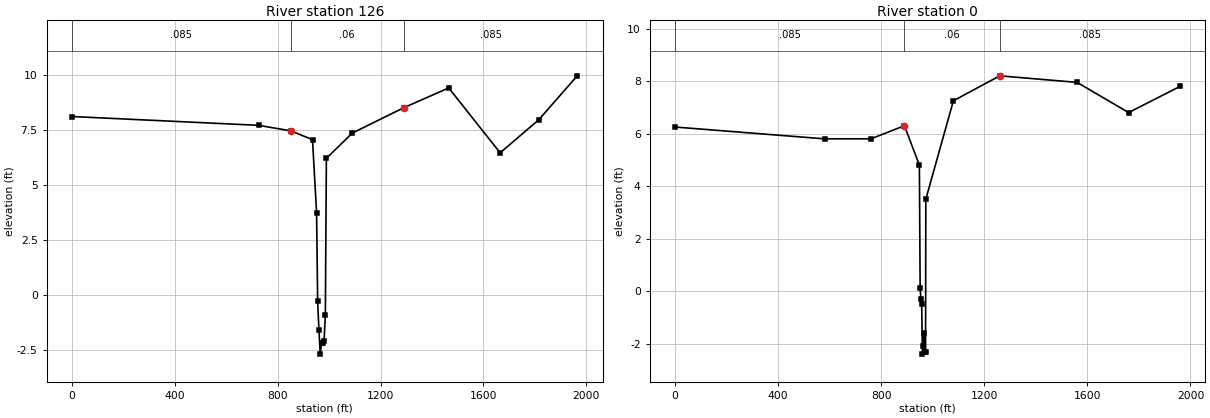
Type RM Length L Ch R =1,126     ,126,126,126,0,0,0
Node Desc=126
#Sta/Elev= 19
       0     8.1     725     7.7     850    7.45     935    7.05     951     3.7
     955     -.3     960    -1.6     965    -2.7     970    -2.2     975    -2.2
     980    -2.1     985     -.9     989     6.2    1090    7.35    1290     8.5
    1465     9.4    1665    6.45    1815    7.95    1965    9.95
#Mann=3,0
       0    .085       0     850     .06       0    1290    .085       0
Bank Sta=850,1290
Exp/Cntr=0.3,0.1

Type RM Length L Ch R =1,0       ,0,0,0,0,0,0
Node Desc= 0
#Sta/Elev= 19
       0    6.25     580     5.8     760     5.8     890     6.3     948     4.8
     951      .1     954     -.3     957     -.5     960    -2.4     963    -2.1
     966    -1.6     969    -2.3     972    -2.3     973     3.5    1080    7.25
    1260     8.2    1560    7.95    1760     6.8    1960     7.8
#Mann=3,0
       0    .085       0     890     .06       0    1260    .085       0
Bank Sta=890,1260
Exp/Cntr=0.3,0.1