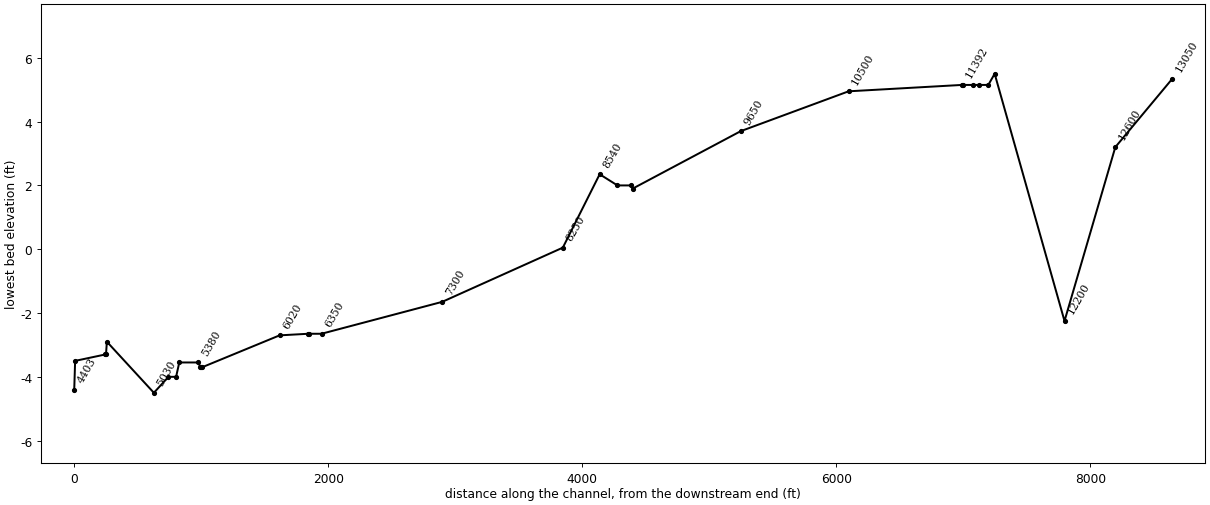
--- oakexscs.prj (project) ---

Proj Title=Oak Creek SCS HEC-2 Import
Current Plan=p01
Default Exp/Contr=0.3,0.1
English Units
Geom File=g01
Flow File=f01
Plan File=p01

--- oakexscs.p01 (plan) ---

Plan Title=Oak Creek Existing 1996
Short Identifier=Oak Ex 96
Geom File=g01
Flow File=f01
Multiple Comp Mode
Subcritical Flow
K Sum by GR=-1
Std Step Tol= .01
Critical Tol= .01
Num of Std Step Trials= 20
Max Error Tol= .3
Flow Tol Ratio= .001
Log Output Level= 0
Friction Slope Method= 0
Multiple Critical Depth

--- oakexscs.f01 (steady flow) ---

Flow Title=Oak Ex. 1996
Number of Flows and Profiles and Boundary= 8, 4, 1
Rch & RM=1           ,13050
       9      24      42      60
Rch & RM=1           ,11600
       9      24      42      60
Rch & RM=1           ,11525
      27      70     124     178
Rch & RM=1           ,8790
      27      70     124     178
Rch & RM=1           ,8680
      32      85     149     214
Rch & RM=1           ,5205
      32      85     149     214
Rch & RM=1           ,5145
      41     106     187     269
Rch & RM=1           ,0
      41     106     187     269
Boundary for Rch & Prof#=1           , 1
Up Type= 32767
Up Value=0
Dn Type= 1
Dn Value=3
Boundary for Rch & Prof#=1           , 2
Up Type= 32767
Up Value=0
Dn Type= 1
Dn Value=3.6
Boundary for Rch & Prof#=1           , 3
Up Type= 32767
Up Value=0
Dn Type= 1
Dn Value=5.1
Boundary for Rch & Prof#=1           , 4
Up Type= 32767
Up Value=0
Dn Type= 1
Dn Value=6.1

--- oakexscs.g01 (geometry) ---

Geom Title=Oak Ex 96  SCS/JEI
ViewRect= 0, 1, 1, 0
Reach=1
Rch X Y Up & X Y Dn=0.5,0.9,0.5,0.1
Rch Arrow X Y Up & X Y Dn=0,0,0,0
Rch Type=0

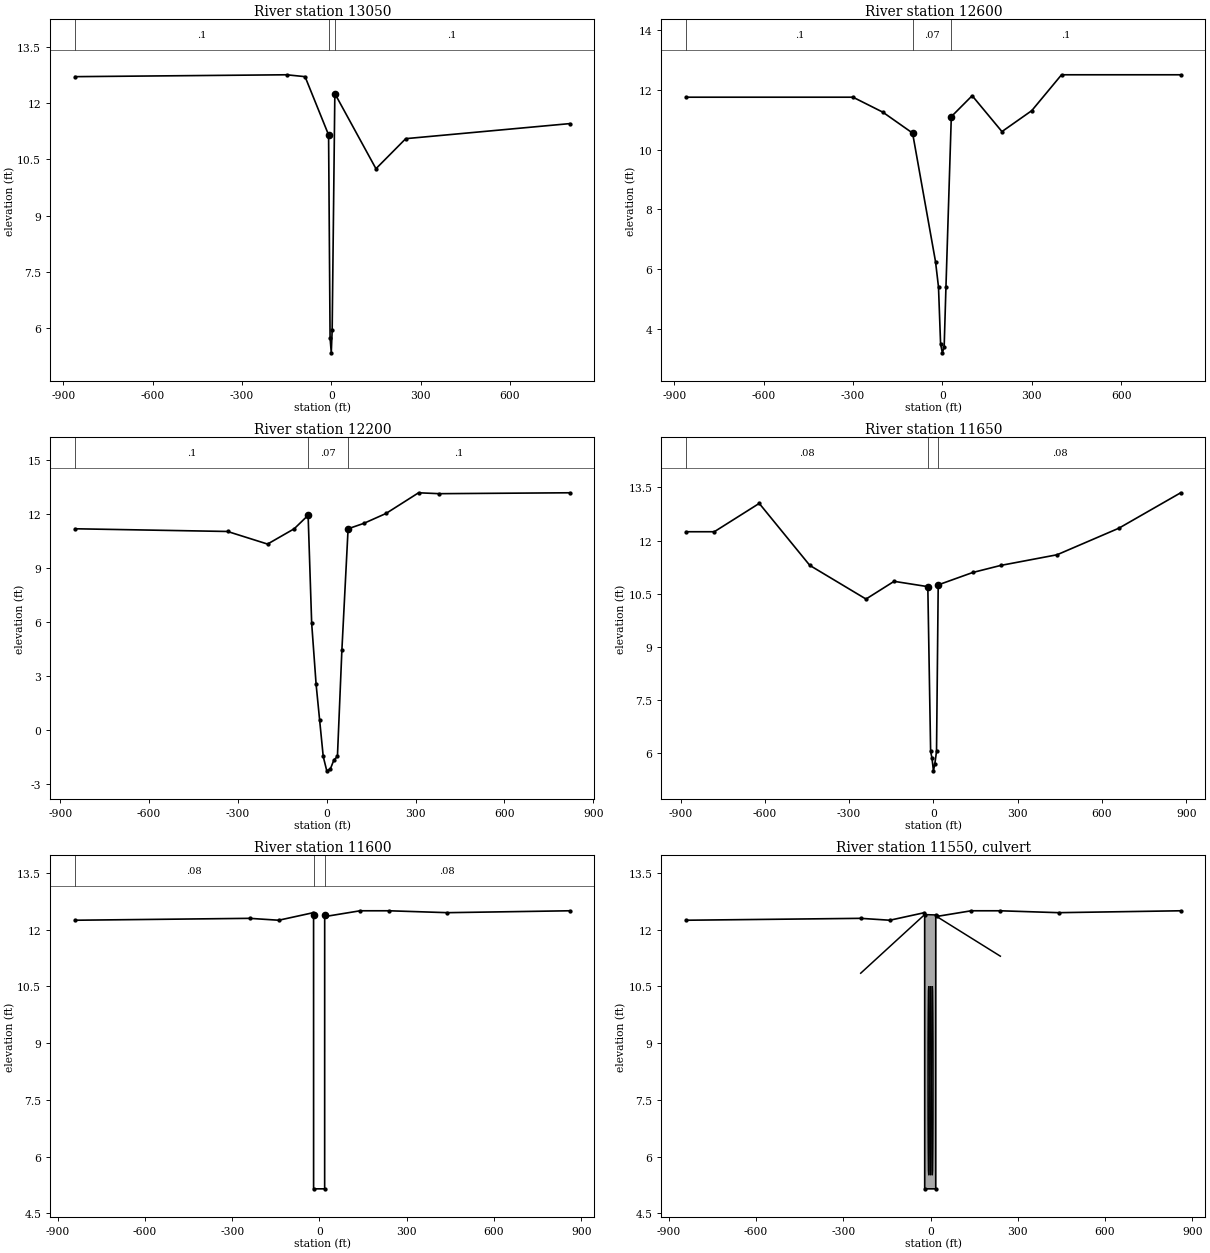
Type RM Length L Ch R =1,13050   ,450,450,450,0,0,0
Node Desc=SCS 314
#Sta/Elev= 11
    -860    12.7    -150   12.75     -88    12.7      -9   11.15      -4    5.75
       0    5.35       3    5.95      12   12.25     150   10.25     250   11.05
     800   11.45
#Mann=3,0
    -860      .1       0      -9     .07       0      12      .1       0
Bank Sta=-9,12
Exp/Cntr=0.3,0.14

Type RM Length L Ch R =1,12600   ,400,400,400,0,0,0
Node Desc=SCS 312
#Sta/Elev= 16
    -860   11.75    -300   11.75    -200   11.25    -100   10.55     -23    6.25
     -13     5.4      -6     3.5       0     3.2       6     3.4      12     5.4
      30    11.1     100    11.8     200    10.6     300    11.3     400    12.5
     800    12.5
#Mann=3,0
    -860      .1       0    -100     .07       0      30      .1       0
Bank Sta=-100,30
Exp/Cntr=0.3,0.14

Type RM Length L Ch R =1,12200   ,550,550,550,0,0,0
Node Desc=SCS 310
#Sta/Elev= 20
    -850    11.2    -335   11.05    -200   10.35    -110    11.2     -63   11.95
     -51    5.95     -36    2.55     -24     .55     -12   -1.45       0   -2.25
      12   -2.15      24   -1.65      36   -1.45      51    4.45      72    11.2
     125    11.5     200   12.05     310    13.2     380   13.15     820    13.2
#Mann=3,0
    -850      .1       0     -63     .07       0      72      .1       0
Bank Sta=-63,72
Exp/Cntr=0.3,0.14

Type RM Length L Ch R =1,11650   ,50,50,50,0,0,0
Node Desc=SCS 306
#Sta/Elev= 18
    -880   12.25    -780   12.25    -620   13.05    -440    11.3    -240   10.35
    -140   10.85     -20    10.7     -10    6.05      -5    5.85       0     5.5
       5     5.7      11    6.05      17   10.75     140    11.1     240    11.3
     440    11.6     660   12.35     880   13.35
#Mann=3,0
    -880     .08       0     -20     .07       0      17     .08       0
Bank Sta=-20,17
Exp/Cntr=0.3,0.14

Type RM Length L Ch R =1,11600   ,75,75,75,0,0,0
Node Desc=SCS 304
#Sta/Elev= 13
    -840   12.25    -240    12.3    -140   12.25     -21   12.45   -20.1   12.39
     -20    5.15      18    5.15    18.1   12.39      21   12.35     140    12.5
     240    12.5     440   12.45     860    12.5
#Mann=3,0
    -840     .08       0   -20.1     .07       0    18.1     .08       0
Bank Sta=-20.1,18.1
Exp/Cntr=0.5,0.3

Type RM Length L Ch R =2,11550   ,,,,0,0,0
Node Desc=Bridge #10  SCS STA 303
Bridge Culvert--1,0,-1,-1
Deck Dist Width WeirC Skew NumUp NumDn MinLoCord MaxHiCord MaxSubmerge Is_Ogee
29,42,2.6,,5,11,,,0.95,0
    -240   -20.1    18.1      21     240
   10.85    12.4   12.39   12.35    11.3
       0       0       0       0       0
    -660    -440    -240    -140   -20.1    18.1     140     240     440     660
     880
      13    12.4    12.4    12.4    12.4    12.4    12.4    12.4      12      12
   11.85
      13    11.3   10.75    10.5       0       0   10.55    10.7    10.7   11.65
   11.85
BR Coef= 1, 0, 0,, 0,,,0.8,0,,0,
Multiple Barrel Culv=1,5,,42,0.011,0.5,1,1,1,5.51,5.46, 3,Culvert #1  , 0
    -6.3    -6.3       0       0     6.3     6.3

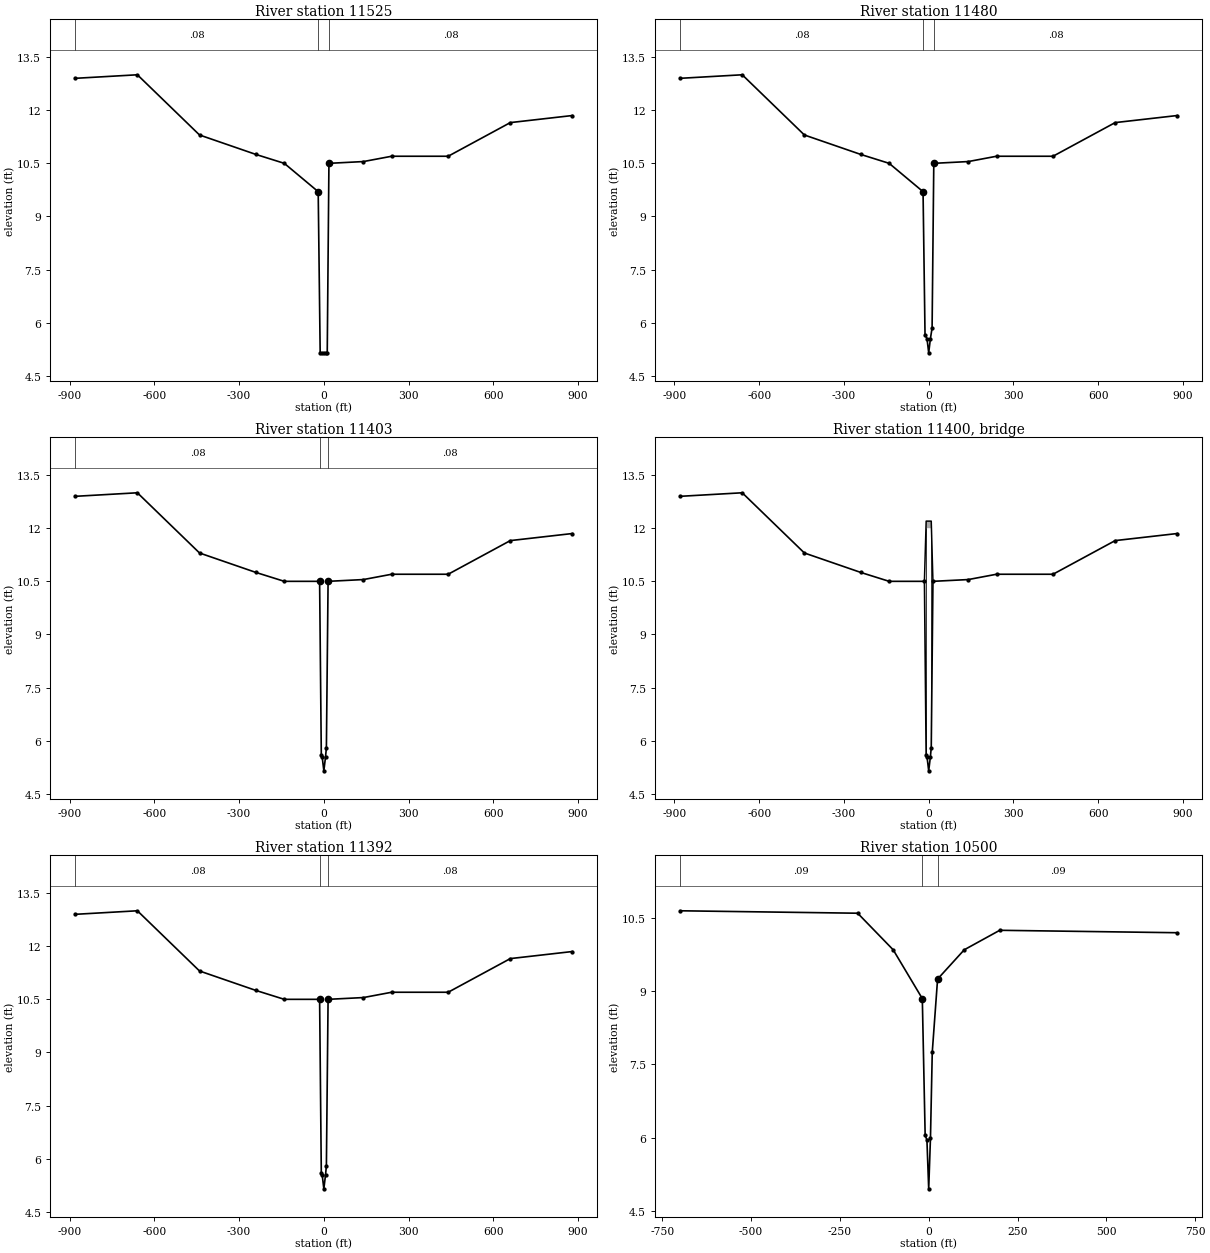
Type RM Length L Ch R =1,11525   ,45,45,45,0,0,0
Node Desc=SCS 302
#Sta/Elev= 17
    -880    12.9    -660      13    -440    11.3    -240   10.75    -140    10.5
     -20     9.7     -13    5.15      -6    5.15       0    5.15       6    5.15
      12    5.15      18    10.5     140   10.55     240    10.7     440    10.7
     660   11.65     880   11.85
#Mann=3,0
    -880     .08       0     -20     .07       0      18     .08       0
Bank Sta=-20,18
Exp/Cntr=0.3,0.11

Type RM Length L Ch R =1,11480   ,77,77,77,0,0,0
Node Desc=SCS 300
#Sta/Elev= 17
    -880    12.9    -660      13    -440    11.3    -240   10.75    -140    10.5
     -20     9.7     -13    5.65      -6    5.55       0    5.15       6    5.55
      12    5.85      18    10.5     140   10.55     240    10.7     440    10.7
     660   11.65     880   11.85
#Mann=3,0
    -880     .08       0     -20     .07       0      18     .08       0
Bank Sta=-20,18
Exp/Cntr=0.3,0.11

Type RM Length L Ch R =1,11403   ,11,11,11,0,0,0
Node Desc=SCS 300
#Sta/Elev= 17
    -880    12.9    -660      13    -440    11.3    -240   10.75    -140    10.5
     -15    10.5      -9     5.6      -6    5.55       0    5.15       6    5.55
       9     5.8      15    10.5     140   10.55     240    10.7     440    10.7
     660   11.65     880   11.85
#Mann=3,0
    -880     .08       0     -15     .07       0      15     .08       0
Bank Sta=-15,15
Exp/Cntr=0.3,0.11

Type RM Length L Ch R =3,11400   ,,,,0,0,0
Bridge Culvert--1,0,-1,-1
Deck Dist Width WeirC Skew NumUp NumDn MinLoCord MaxHiCord MaxSubmerge Is_Ogee
5,6,2.6,,4,4,,,0.95,0
   -15.2      -9       9      15
    10.5    12.2    12.2    10.5
    10.4      12      12    10.4
   -15.2      -9       9      15
    10.5    12.2    12.2    10.5
    10.4      12      12    10.4
Pier Skew, UpSta & Num, DnSta & Num=,-9, 2,-9, 2, 0, 0
       1       1
       0    12.2
       1       1
       0    12.2
Pier Skew, UpSta & Num, DnSta & Num=,9, 2,9, 2, 0, 0
       1       1
       0    12.2
       1       1
       0    12.2
BR Coef= 0, 0,-1,1.05, 0,,,0.8,0,0,0,

Type RM Length L Ch R =1,11392   ,892,892,892,0,0,0
Node Desc=SCS 300
#Sta/Elev= 17
    -880    12.9    -660      13    -440    11.3    -240   10.75    -140    10.5
     -15    10.5      -9     5.6      -6    5.55       0    5.15       6    5.55
       9     5.8      15    10.5     140   10.55     240    10.7     440    10.7
     660   11.65     880   11.85
#Mann=3,0
    -880     .08       0     -15     .07       0      15     .08       0
Bank Sta=-15,15
Exp/Cntr=0.3,0.11

Type RM Length L Ch R =1,10500   ,850,850,850,0,0,0
Node Desc=SCS 298
#Sta/Elev= 13
    -700   10.65    -200    10.6    -100    9.85     -18    8.85     -10    6.05
      -5    5.95       0    4.95       5       6      10    7.75      25    9.25
     100    9.85     200   10.25     700    10.2
#Mann=3,0
    -700     .09       0     -18     .07       0      25     .09       0
Bank Sta=-18,25
Exp/Cntr=0.3,0.11

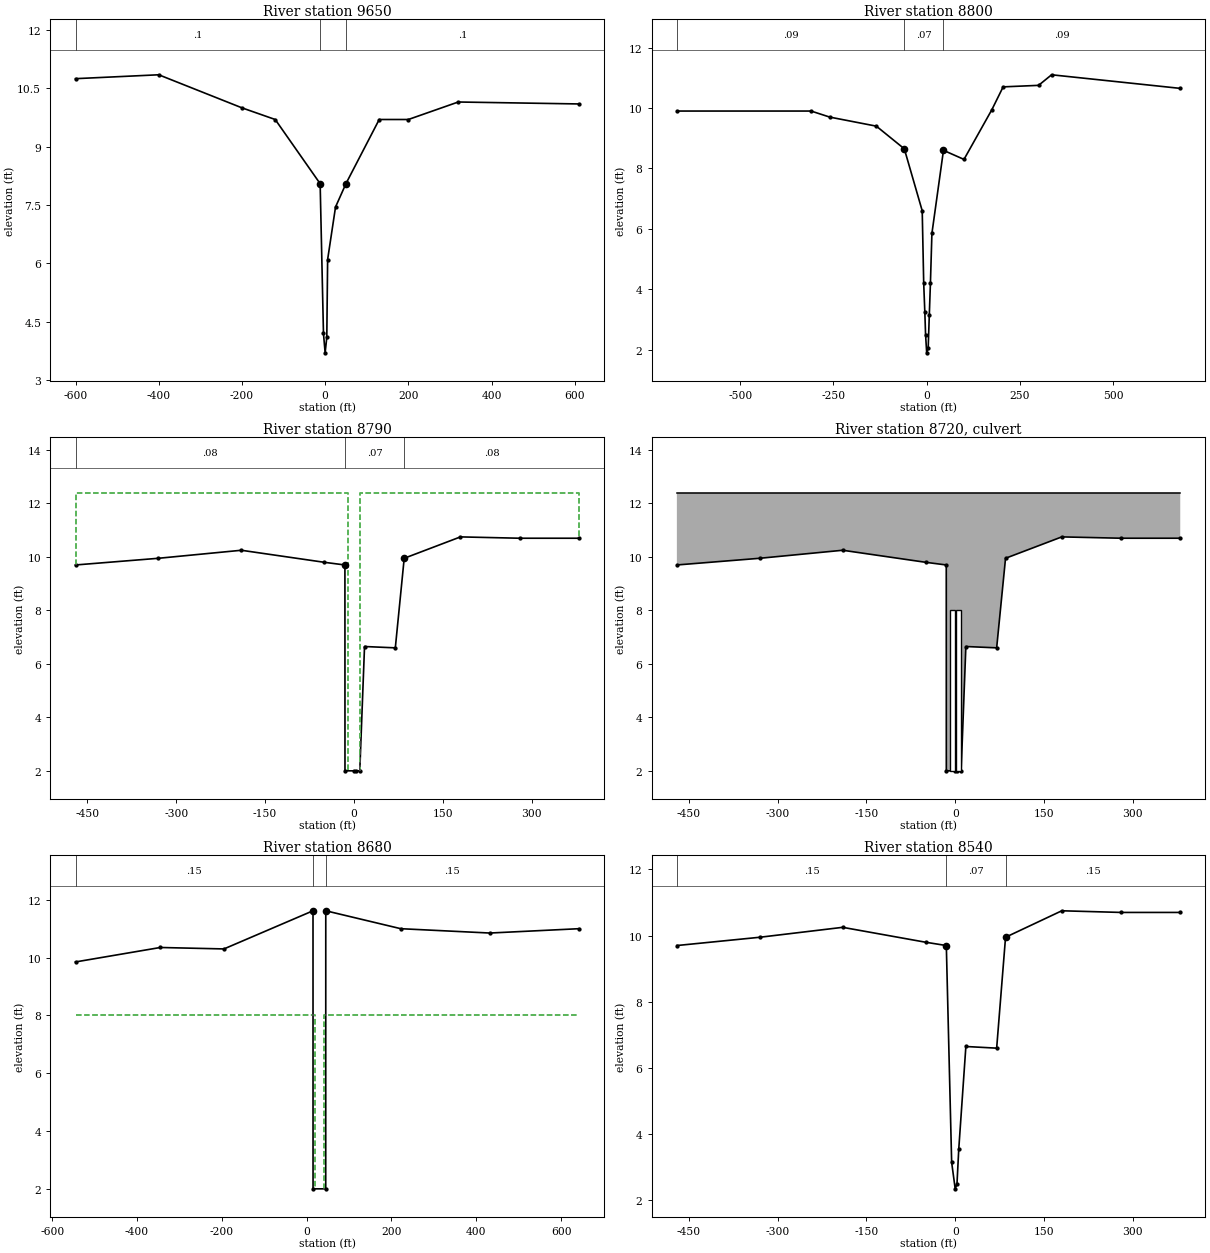
Type RM Length L Ch R =1,9650    ,850,850,850,0,0,0
Node Desc=SCS 296
#Sta/Elev= 15
    -600   10.75    -400   10.85    -200      10    -120     9.7     -12    8.05
      -4     4.2       0     3.7       4     4.1       6     6.1      25    7.45
      50    8.05     130     9.7     200     9.7     320   10.15     610    10.1
#Mann=3,0
    -600      .1       0     -12     .07       0      50      .1       0
Bank Sta=-12,50
Exp/Cntr=0.3,0.11

Type RM Length L Ch R =1,8800    ,10,10,10,0,0,0
Node Desc=SCS 292
#Sta/Elev= 21
    -670     9.9    -310     9.9    -260     9.7    -135     9.4     -60    8.65
     -12     6.6      -8     4.2      -5    3.25      -3     2.5       0     1.9
       4    2.05       7    3.15      10     4.2      14    5.85      45     8.6
     100     8.3     175    9.95     205    10.7     300   10.75     335    11.1
     680   10.65
#Mann=3,0
    -670     .09       0     -60     .07       0      45     .09       0
Bank Sta=-60,45
Exp/Cntr=0.3,0.11

Type RM Length L Ch R =1,8790    ,110,110,110,0,0,0
Node Desc=SCS 288
#Sta/Elev= 15
    -470     9.7    -330    9.95    -190   10.25     -50     9.8   -15.1     9.7
     -15       2       0       2       3       2      10       2      18    6.65
      70     6.6      85    9.95     180   10.75     280    10.7     380    10.7
#Mann=3,0
    -470     .08       0   -15.1     .07       0      85     .08       0
#XS Ineff= 2 , 0
             -10    12.4      10            12.4
Bank Sta=-15.1,85
Exp/Cntr=0.3,0.1

Type RM Length L Ch R =2,8720    ,,,,0,0,0
Node Desc=Bridge #9  SCS STA 290
Bridge Culvert--1,0,-1,-1
Deck Dist Width WeirC Skew NumUp NumDn MinLoCord MaxHiCord MaxSubmerge Is_Ogee
5,39,2.6,,2,2,,,0.95,0
    -470     380
    12.4    12.4
       0       0
    -545     642
    12.4    12.4
       0       0
BR Coef= 1, 0, 0,, 0,,,0.8,0,,0,
Culvert=2,6,8,100,0.011,0.5,1,10,1,2,-5,2,25,Culvert #1  , 0
Culvert=2,6,8,100,0.011,0.5,1,10,1,2,5,2,35,Culvert #2  , 0

Type RM Length L Ch R =1,8680    ,140,140,140,0,0,0
Node Desc=SCS 290
#Sta/Elev= 10
    -545    9.85    -345   10.35    -195    10.3      15   11.62    15.1       2
      45       2    45.1   11.62     222      11     432   10.85     642      11
#Mann=3,0
    -545     .15       0      15     .07       0    45.1     .15       0
#XS Ineff= 2 , 0
              20       8      40               8
Bank Sta=15,45.1
Exp/Cntr=0.5,0.3

Type RM Length L Ch R =1,8540    ,290,290,290,0,0,0
Node Desc=SCS 286
#Sta/Elev= 15
    -470     9.7    -330    9.95    -190   10.25     -50     9.8     -15     9.7
      -6    3.15       0    2.35       3     2.5       6    3.55      18    6.65
      70     6.6      85    9.95     180   10.75     280    10.7     380    10.7
#Mann=3,0
    -470     .15       0     -15     .07       0      85     .15       0
Bank Sta=-15,85
Exp/Cntr=0.3,0.1

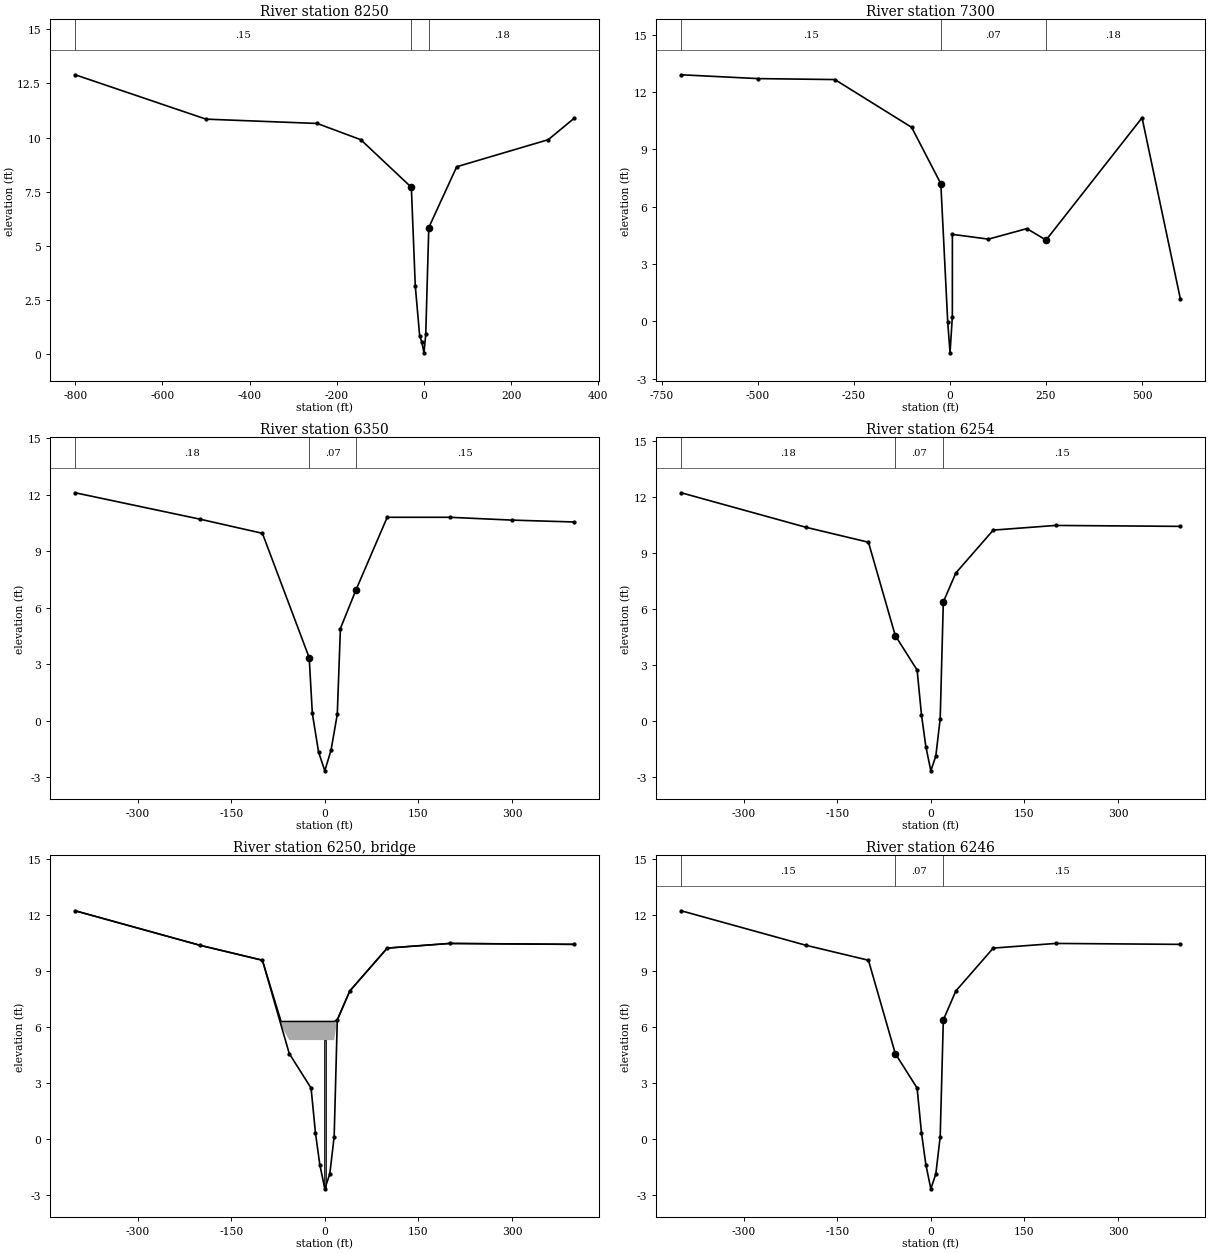
Type RM Length L Ch R =1,8250    ,950,950,950,0,0,0
Node Desc=SCS 284
#Sta/Elev= 14
    -800    12.9    -500   10.85    -245   10.65    -145     9.9     -29     7.7
     -20    3.15     -10     .85      -5     .55       0     .05       4      .9
      11    5.84      75    8.65     285     9.9     345    10.9
#Mann=3,0
    -800     .15       0     -29     .07       0      11     .18       0
Bank Sta=-29,11
Exp/Cntr=0.3,0.1

Type RM Length L Ch R =1,7300    ,950,950,950,0,0,0
Node Desc=SCS 282
#Sta/Elev= 14
    -700    12.9    -500    12.7    -300   12.65    -100   10.15     -24     7.2
      -6    -.05       0   -1.65       6     .25     6.1    4.55     100     4.3
     200    4.85     250    4.25     500   10.65     600    1.15
#Mann=3,0
    -700     .15       0     -24     .07       0     250     .18       0
Bank Sta=-24,250
Exp/Cntr=0.3,0.1

Type RM Length L Ch R =1,6350    ,96,96,96,0,0,0
Node Desc=SCS 280
#Sta/Elev= 15
    -400    12.1    -200    10.7    -100    9.95     -25    3.35     -20      .4
     -10   -1.65       0   -2.65      10   -1.55      20     .35      25     4.9
      50    6.95     100    10.8     200    10.8     300   10.65     400   10.55
#Mann=3,0
    -400     .18       0     -25     .07       0      50     .15       0
Bank Sta=-25,50
Exp/Cntr=0.3,0.1

Type RM Length L Ch R =1,6254    ,8,8,8,0,0,0
Node Desc=SCS 276
#Sta/Elev= 15
    -400   12.25    -200    10.4    -100     9.6     -57     4.6     -22    2.75
     -15     .35      -8   -1.35       0   -2.65       8   -1.85      15     .15
      20     6.4      40    7.95     100   10.25     200    10.5     400   10.45
#Mann=3,0
    -400     .18       0     -57     .07       0      20     .15       0
Bank Sta=-57,20
Exp/Cntr=0.5,0.3

Type RM Length L Ch R =3,6250    ,,,,0,0,0
Node Desc=Bridge # 8 SCS STA 275
Bridge Culvert--1,0,-1,-1
Deck Dist Width WeirC Skew NumUp NumDn MinLoCord MaxHiCord MaxSubmerge Is_Ogee
0,7.6,2.7,,16,16,6.32,,0.95,0
    -400    -200    -100     -70     -57     -22     -15      -8       0       8
      15      20      40     100     200     400
   12.25    10.4     9.6    6.32    6.32    6.32    6.32    6.32    6.32    6.32
    6.32     6.4    7.95   10.25    10.5   10.45
   12.25    10.4     9.6    5.32    5.32    5.32    5.32    5.32    5.32    5.32
    5.32    5.32    7.95   10.25    10.5   10.45
    -400    -200    -100     -70     -57     -22     -15      -8       0       8
      15      20      40     100     200     400
   12.25    10.4     9.6    6.32    6.32    6.32    6.32    6.32    6.32    6.32
    6.32    6.32    7.95   10.25    10.5   10.45
   12.25    10.4     9.6    5.32    5.32    5.32    5.32    5.32    5.32    5.32
    5.32    5.32    7.95   10.25    10.5   10.45
Pier Skew, UpSta & Num, DnSta & Num=,0, 2,0, 2, 0, 0
       3       3
   -2.65    5.32
       3       3
   -2.65    5.32
BR Coef= 0, 0,-1,1.25, 0,,,0.8006408,0,2,2,5.32

Type RM Length L Ch R =1,6246    ,226,226,226,0,0,0
Node Desc=SCS 274
#Sta/Elev= 15
    -400   12.25    -200    10.4    -100     9.6     -57     4.6     -22    2.75
     -15     .35      -8   -1.35       0   -2.65       8   -1.85      15     .15
      20     6.4      40    7.95     100   10.25     200    10.5     400   10.45
#Mann=3,0
    -400     .15       0     -57     .07       0      20     .15       0
Bank Sta=-57,20
Exp/Cntr=0.3,0.1

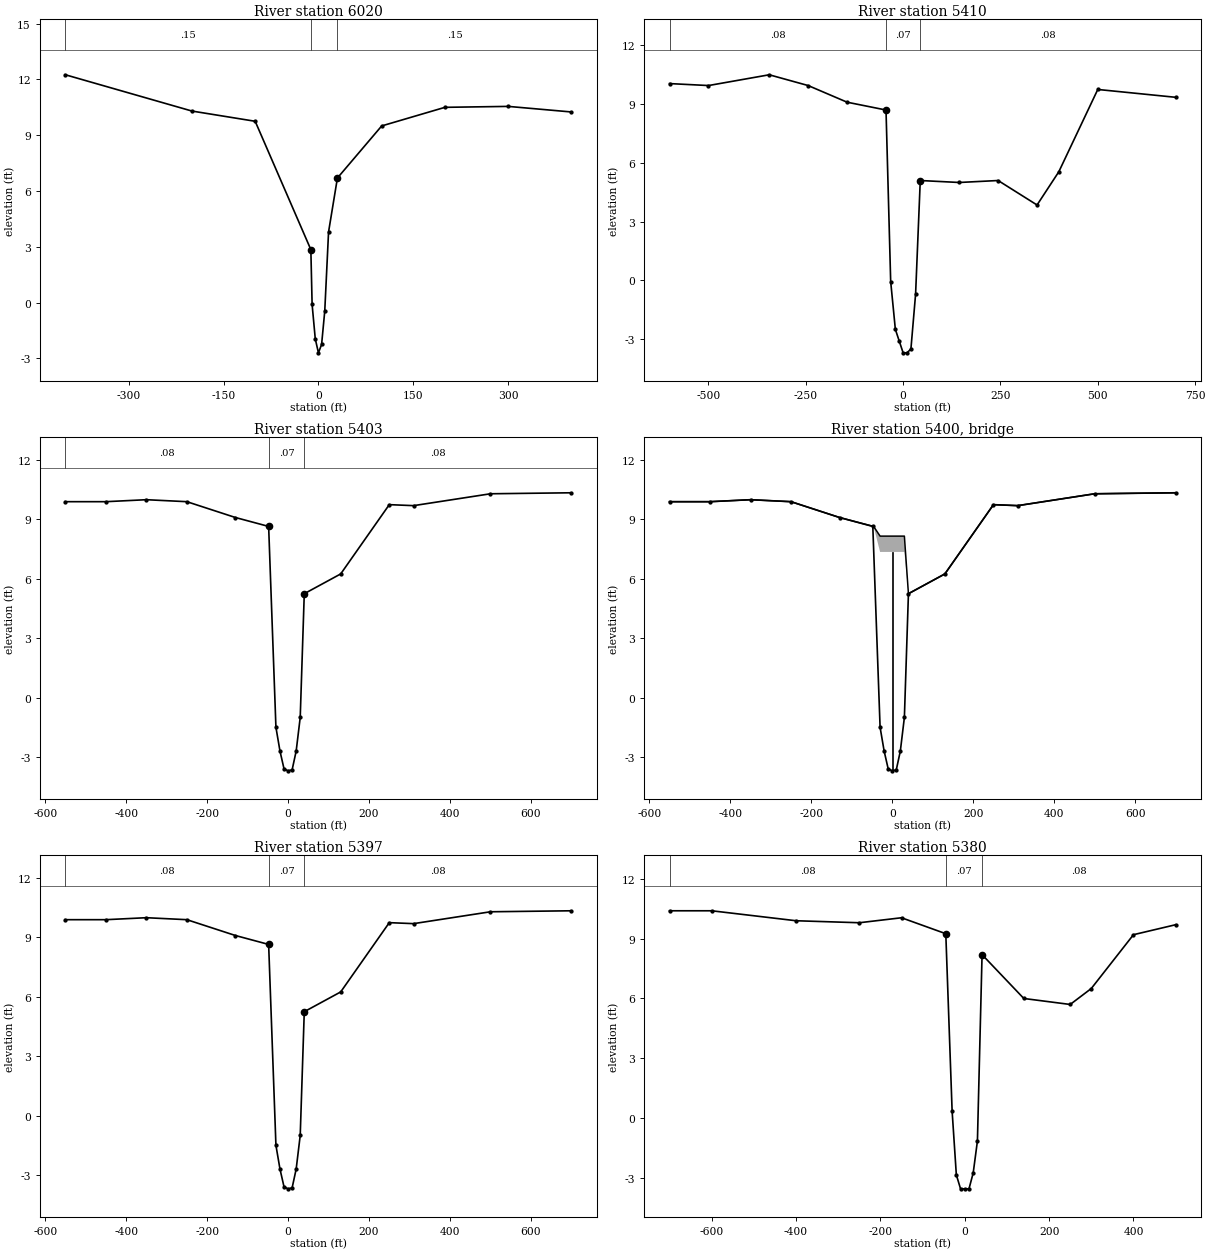
Type RM Length L Ch R =1,6020    ,610,610,610,0,0,0
Node Desc=SCS 272
#Sta/Elev= 15
    -400   12.25    -200    10.3    -100    9.75     -12    2.85     -10     -.1
      -5   -1.95       0    -2.7       5   -2.25      10    -.45      16     3.8
      30     6.7     100     9.5     200    10.5     300   10.55     400   10.25
#Mann=3,0
    -400     .15       0     -12     .07       0      30     .15       0
Bank Sta=-12,30
Exp/Cntr=0.3,0.1

Type RM Length L Ch R =1,5410    ,7,7,7,0,0,0
Node Desc=SCS 270
#Sta/Elev= 20
    -600   10.05    -500    9.95    -344    10.5    -244    9.95    -144     9.1
     -44     8.7     -32    -.06     -20    -2.5     -10    -3.1       0    -3.7
      10    -3.7      20    -3.5      32     -.7      44     5.1     144       5
     244     5.1     344    3.85     400    5.55     500    9.75     700    9.35
#Mann=3,0
    -600     .08       0     -44     .07       0      44     .08       0
Bank Sta=-44,44
Exp/Cntr=0.3,0.1

Type RM Length L Ch R =1,5403    ,6,6,6,0,0,0
Node Desc=SCS 266
#Sta/Elev= 19
    -550     9.9    -450     9.9    -350      10    -250     9.9    -130     9.1
     -48    8.65     -30    -1.5     -20    -2.7     -10    -3.6       0    -3.7
      10   -3.65      20    -2.7      30      -1      40    5.25     130    6.25
     250    9.75     310     9.7     500    10.3     700   10.35
#Mann=3,0
    -550     .08       0     -48     .07       0      40     .08       0
Bank Sta=-48,40
Exp/Cntr=0.5,0.3

Type RM Length L Ch R =3,5400    ,,,,0,0,0
Node Desc=Bridge # 7 SCS STA 265
Bridge Culvert--1,0,-1,-1
Deck Dist Width WeirC Skew NumUp NumDn MinLoCord MaxHiCord MaxSubmerge Is_Ogee
0,5.7,2.7,,19,19,8.16,,0.95,0
    -550    -450    -350    -250    -130     -46     -30     -20     -10       0
      10      20      30      40     130     250     310     500     700
     9.9     9.9      10     9.9     9.1    8.65    8.16    8.16    8.16    8.16
    8.16    8.16    8.16    5.25    6.25    9.75     9.7    10.3   10.35
     9.9     9.9      10     9.9     9.1    8.65    7.36    7.36    7.36    7.36
    7.36    7.36    7.36    5.25    6.25    9.75     9.7    10.3   10.35
    -550    -450    -350    -250    -130     -46     -30     -20     -10       0
      10      20      30      40     130     250     310     500     700
     9.9     9.9      10     9.9     9.1    8.65    8.16    8.16    8.16    8.16
    8.16    8.16    8.16    5.25    6.25    9.75     9.7    10.3   10.35
     9.9     9.9      10     9.9     9.1    8.65    7.36    7.36    7.36    7.36
    7.36    7.36    7.36    5.25    6.25    9.75     9.7    10.3   10.35
Pier Skew, UpSta & Num, DnSta & Num=,0, 2,0, 2, 0, 0
     3.3     3.3
    -3.7    7.36
     3.3     3.3
    -3.7    7.36
BR Coef= 0, 0,-1,1.05, 0,,,0.8006408,0,2,2,7.36

Type RM Length L Ch R =1,5397    ,17,17,17,0,0,0
Node Desc=SCS 264
#Sta/Elev= 19
    -550     9.9    -450     9.9    -350      10    -250     9.9    -130     9.1
     -48    8.65     -30    -1.5     -20    -2.7     -10    -3.6       0    -3.7
      10   -3.65      20    -2.7      30      -1      40    5.25     130    6.25
     250    9.75     310     9.7     500    10.3     700   10.35
#Mann=3,0
    -550     .08       0     -48     .07       0      40     .08       0
Bank Sta=-48,40
Exp/Cntr=0.3,0.1

Type RM Length L Ch R =1,5380    ,150,150,150,0,0,0
Node Desc=SCS 262
#Sta/Elev= 19
    -700    10.4    -600    10.4    -400     9.9    -250     9.8    -150   10.05
     -45    9.25     -30     .35     -20   -2.85     -10   -3.55       0   -3.55
      10   -3.55      20   -2.75      30   -1.15      41     8.2     140       6
     250     5.7     300     6.5     400     9.2     500     9.7
#Mann=3,0
    -700     .08       0     -45     .07       0      41     .08       0
#XS Ineff= 2 , 0
             -45    9.25      41             8.2
Bank Sta=-45,41
Exp/Cntr=0.3,0.1

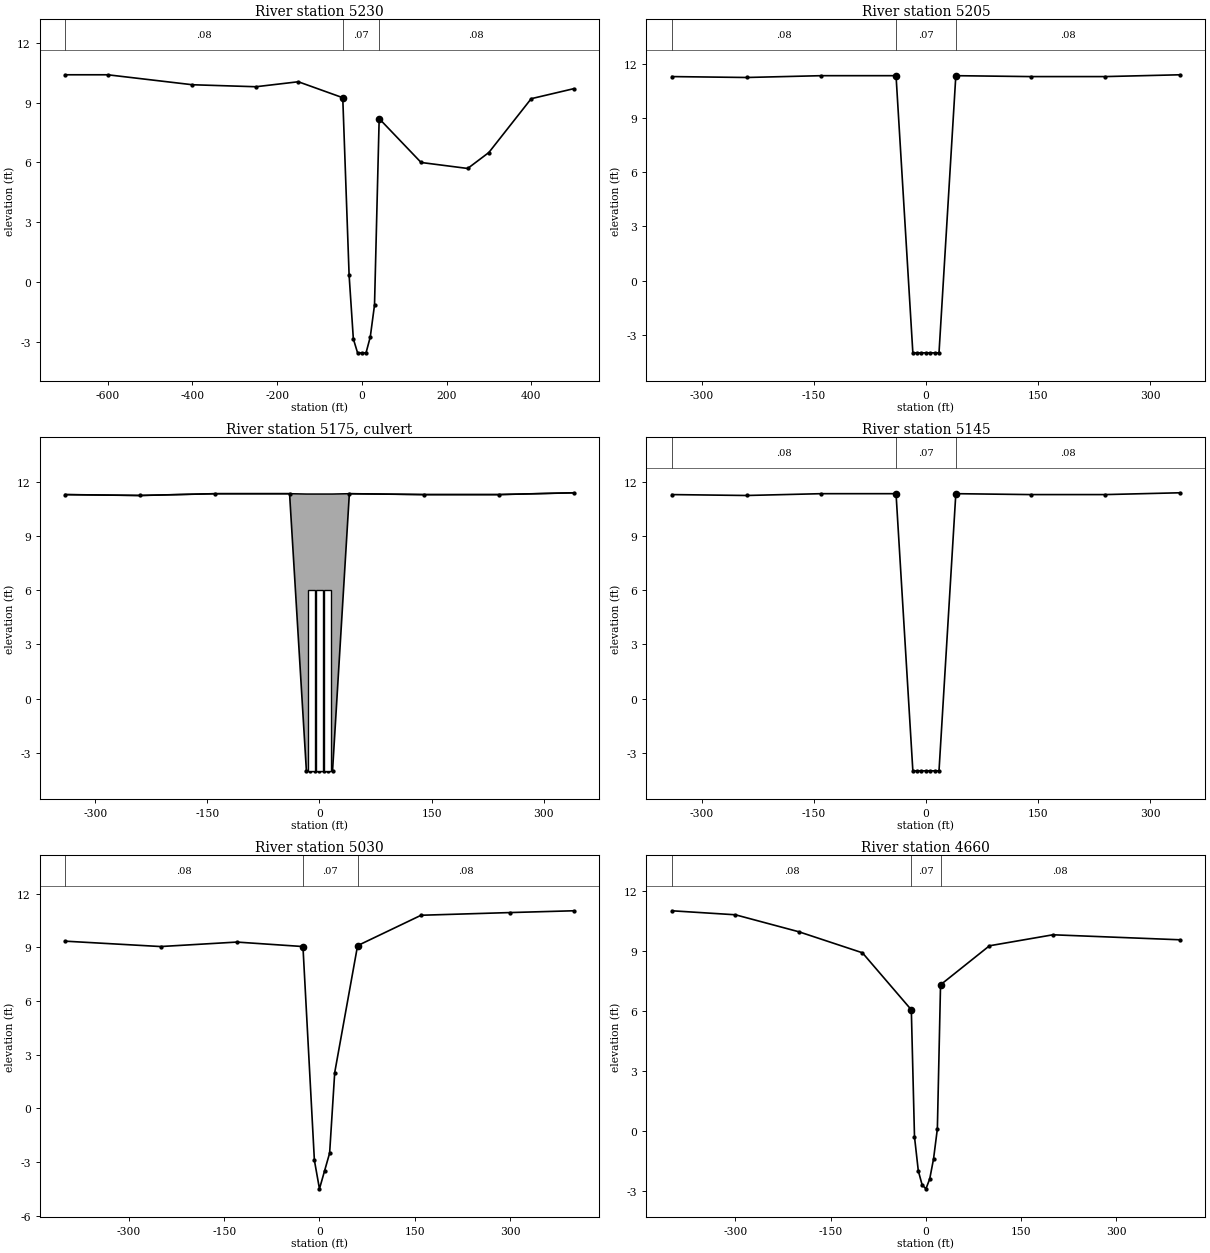
Type RM Length L Ch R =1,5230    ,25,25,25,0,0,0
Node Desc=SCS 262
#Sta/Elev= 19
    -700    10.4    -600    10.4    -400     9.9    -250     9.8    -150   10.05
     -45    9.25     -30     .35     -20   -2.85     -10   -3.55       0   -3.55
      10   -3.55      20   -2.75      30   -1.15      41     8.2     140       6
     250     5.7     300     6.5     400     9.2     500     9.7
#Mann=3,0
    -700     .08       0     -45     .07       0      41     .08       0
#XS Ineff= 2 , 0
             -45    9.25      41             8.2
Bank Sta=-45,41
Exp/Cntr=0.3,0.1

Type RM Length L Ch R =1,5205    ,60,60,60,0,0,0
Node Desc=SCS 258
#Sta/Elev= 15
    -340    11.3    -240   11.25    -140   11.35     -40   11.35   -17.5      -4
     -12      -4      -6      -4       0      -4       6      -4      12      -4
    17.5      -4      40   11.35     140    11.3     240    11.3     340    11.4
#Mann=3,0
    -340     .08       0     -40     .07       0      40     .08       0
Bank Sta=-40,40
Exp/Cntr=0.5,0.3

Type RM Length L Ch R =2,5175    ,,,,0,0,0
Node Desc=Old US 41 Triple 10x10
Bridge Culvert--1,0,-1,-1
Deck Dist Width WeirC Skew NumUp NumDn MinLoCord MaxHiCord MaxSubmerge Is_Ogee
0,60,2.7,,15,15,11.33,,0.95,0
    -340    -240    -140     -40   -17.5     -12      -6       0       6      12
    17.5      40     140     240     340
    11.3   11.25   11.35   11.35   11.33   11.33   11.33   11.33   11.33   11.33
   11.33   11.35    11.3    11.3    11.4
    11.3   11.25   11.35      -5      -5      -5      -5      -5      -5      -5
      -5      -5    11.3    11.3    11.4
    -340    -240    -140     -40   -17.5     -12      -6       0       6      12
    17.5      40     140     240     340
    11.3   11.25   11.35   11.35   11.33   11.33   11.33   11.33   11.33   11.33
   11.33   11.35    11.3    11.3    11.4
    11.3   11.25   11.35      -5      -5      -5      -5      -5      -5      -5
      -5      -5    11.3    11.3    11.4
BR Coef=-1, 0, 0,1.25, 0,,,0.8006408,0,2,1,5.98
Multiple Barrel Culv=2,10,10,60,0.012,0.5,1,11,1,-4,-4, 3,Culvert #1  , 0
     -11     -11       0       0      11      11

Type RM Length L Ch R =1,5145    ,115,115,115,0,0,0
Node Desc=SCS 256
#Sta/Elev= 15
    -340    11.3    -240   11.25    -140   11.35     -40   11.35   -17.5      -4
     -12      -4      -6      -4       0      -4       6      -4      12      -4
    17.5      -4      40   11.35     140    11.3     240    11.3     340    11.4
#Mann=3,0
    -340     .08       0     -40     .07       0      40     .08       0
Bank Sta=-40,40
Exp/Cntr=0.3,0.1

Type RM Length L Ch R =1,5030    ,370,370,370,0,0,0
Node Desc=SCS 254
#Sta/Elev= 13
    -400    9.35    -250    9.05    -130     9.3     -26    9.05      -8    -2.9
       0    -4.5       8    -3.5      16    -2.5      24       2      60     9.1
     160    10.8     300   10.95     400   11.05
#Mann=3,0
    -400     .08       0     -26     .07       0      60     .08       0
Bank Sta=-26,60
Exp/Cntr=0.3,0.1

Type RM Length L Ch R =1,4660    ,7,7,7,0,0,0
Node Desc=SCS 252
#Sta/Elev= 16
    -400      11    -300    10.8    -200    9.95    -100     8.9     -23    6.05
     -18     -.3     -12      -2      -6    -2.7       0    -2.9       6    -2.4
      12    -1.4      18      .1      23     7.3     100    9.25     200     9.8
     400    9.55
#Mann=3,0
    -400     .08       0     -23     .07       0      23     .08       0
Bank Sta=-23,23
Exp/Cntr=0.3,0.1

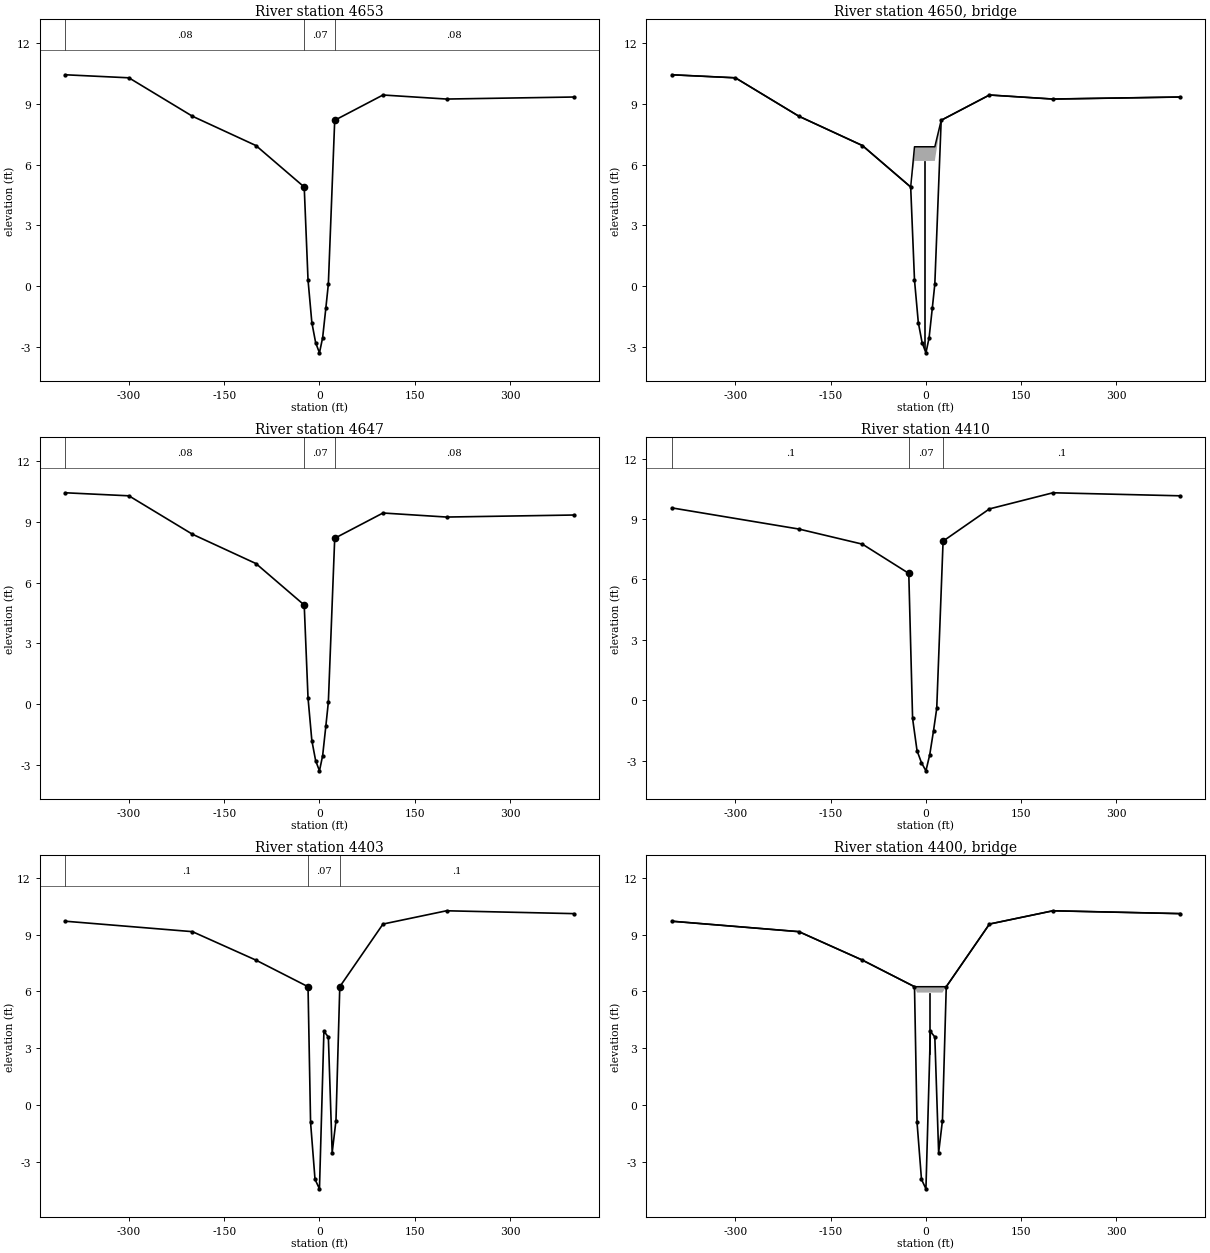
Type RM Length L Ch R =1,4653    ,6,6,6,0,0,0
Node Desc=SCS 248
#Sta/Elev= 16
    -400   10.45    -300    10.3    -200     8.4    -100    6.95     -24     4.9
     -18      .3     -12    -1.8      -6    -2.8       0    -3.3       5   -2.55
      10    -1.1      14      .1      24     8.2     100    9.45     200    9.25
     400    9.35
#Mann=3,0
    -400     .08       0     -24     .07       0      24     .08       0
Bank Sta=-24,24
Exp/Cntr=0.5,0.3

Type RM Length L Ch R =3,4650    ,,,,0,0,0
Node Desc=Bridge # 5 SCS STA 247
Bridge Culvert--1,0,-1,-1
Deck Dist Width WeirC Skew NumUp NumDn MinLoCord MaxHiCord MaxSubmerge Is_Ogee
0,6,2.7,,16,16,6.89,,0.95,0
    -400    -300    -200    -100     -24     -18     -12      -6       0       5
      10      14      24     100     200     400
   10.45    10.3     8.4    6.95     4.9    6.89    6.89    6.89    6.89    6.89
    6.89    6.89     8.2    9.45    9.25    9.35
   10.45    10.3     8.4    6.95     4.9    6.19    6.19    6.19    6.19    6.19
    6.19    6.19     8.2    9.45    9.25    9.35
    -400    -300    -200    -100     -24     -18     -12      -6       0       5
      10      14      24     100     200     400
   10.45    10.3     8.4    6.95     4.9    6.89    6.89    6.89    6.89    6.89
    6.89    6.89     8.2    9.45    9.25    9.35
   10.45    10.3     8.4    6.95     4.9    6.19    6.19    6.19    6.19    6.19
    6.19    6.19     8.2    9.45    9.25    9.35
Pier Skew, UpSta & Num, DnSta & Num=,-2, 2,-2, 2, 0, 0
     2.5     2.5
    -3.3    6.19
     2.5     2.5
    -3.3    6.19
BR Coef= 0, 0,-1,1.05, 0,,,0.8006408,0,2,2,6.19

Type RM Length L Ch R =1,4647    ,237,237,237,0,0,0
Node Desc=SCS 246
#Sta/Elev= 16
    -400   10.45    -300    10.3    -200     8.4    -100    6.95     -24     4.9
     -18      .3     -12    -1.8      -6    -2.8       0    -3.3       5   -2.55
      10    -1.1      14      .1      24     8.2     100    9.45     200    9.25
     400    9.35
#Mann=3,0
    -400     .08       0     -24     .07       0      24     .08       0
Bank Sta=-24,24
Exp/Cntr=0.3,0.1

Type RM Length L Ch R =1,4410    ,7,7,7,0,0,0
Node Desc=SCS 244
#Sta/Elev= 15
    -400    9.55    -200     8.5    -100    7.75     -27     6.3     -21     -.9
     -14    -2.5      -7    -3.1       0    -3.5       6    -2.7      12    -1.5
      17     -.4      27     7.9     100     9.5     200    10.3     400   10.15
#Mann=3,0
    -400      .1       0     -27     .07       0      27      .1       0
Bank Sta=-27,27
Exp/Cntr=0.3,0.1

Type RM Length L Ch R =1,4403    ,6.6,6.6,6.6,0,0,0
Node Desc=SCS 240
#Sta/Elev= 15
    -400     9.7    -200    9.15    -100    7.65     -18    6.25     -14     -.9
      -7    -3.9       0    -4.4       7     3.9      14     3.6      20    -2.5
      26     -.8      32    6.25     100    9.55     200   10.25     400    10.1
#Mann=3,0
    -400      .1       0     -18     .07       0      32      .1       0
#XS Ineff= 2 , 0
             -18    6.25      32            6.25
Bank Sta=-18,32
Exp/Cntr=0.5,0.3

Type RM Length L Ch R =3,4400    ,,,,0,0,0
Node Desc=Bridge # 4 SCS STA 239
Bridge Culvert--1,0,-1,-1
Deck Dist Width WeirC Skew NumUp NumDn MinLoCord MaxHiCord MaxSubmerge Is_Ogee
0,6.6,2.7,,15,15,,,0.95,0
    -400    -200    -100     -18     -14      -7       0       7      14      20
      26      32     100     200     400
     9.7    9.15    7.65    6.25    6.25    6.25    6.25    6.25    6.25    6.25
    6.25    6.25    9.55   10.25    10.1
     9.7    9.15    7.65    6.25    5.94    5.94    5.94    5.94    5.94    5.94
    5.94    6.25    9.55   10.25    10.1
    -400    -200    -100     -18     -14      -7       0       7      14      20
      26      32     100     200     400
     9.7    9.15    7.65    6.25    6.25    6.25    6.25    6.25    6.25    6.25
    6.25    6.25    9.55   10.25    10.1
     9.7    9.15    7.65    6.25    5.94    5.94    5.94    5.94    5.94    5.94
    5.94    6.25    9.55   10.25    10.1
Pier Skew, UpSta & Num, DnSta & Num=,6, 2,6, 2, 0, 0
       2       2
    -4.4    5.94
       2       2
    -4.4    5.94
BR Coef= 0, 0,-1,1.05, 0,,,0.8006408,0,2,2,5.94