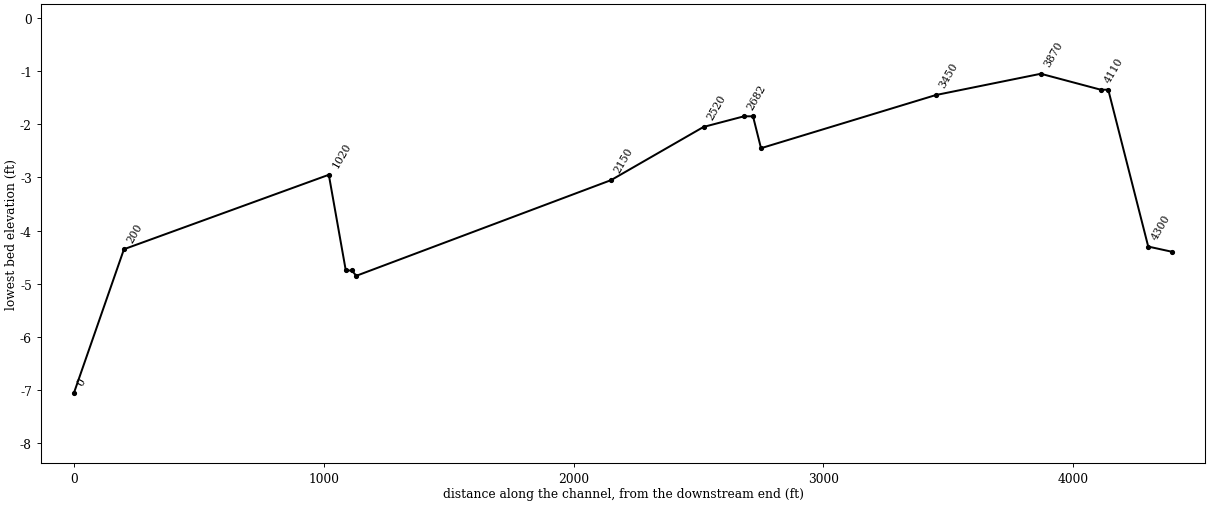
HEC-RAS study oakexscs.prj: Oak Creek SCS HEC-2 Import

--- oakexscs.g01 (geometry) --- (continued)

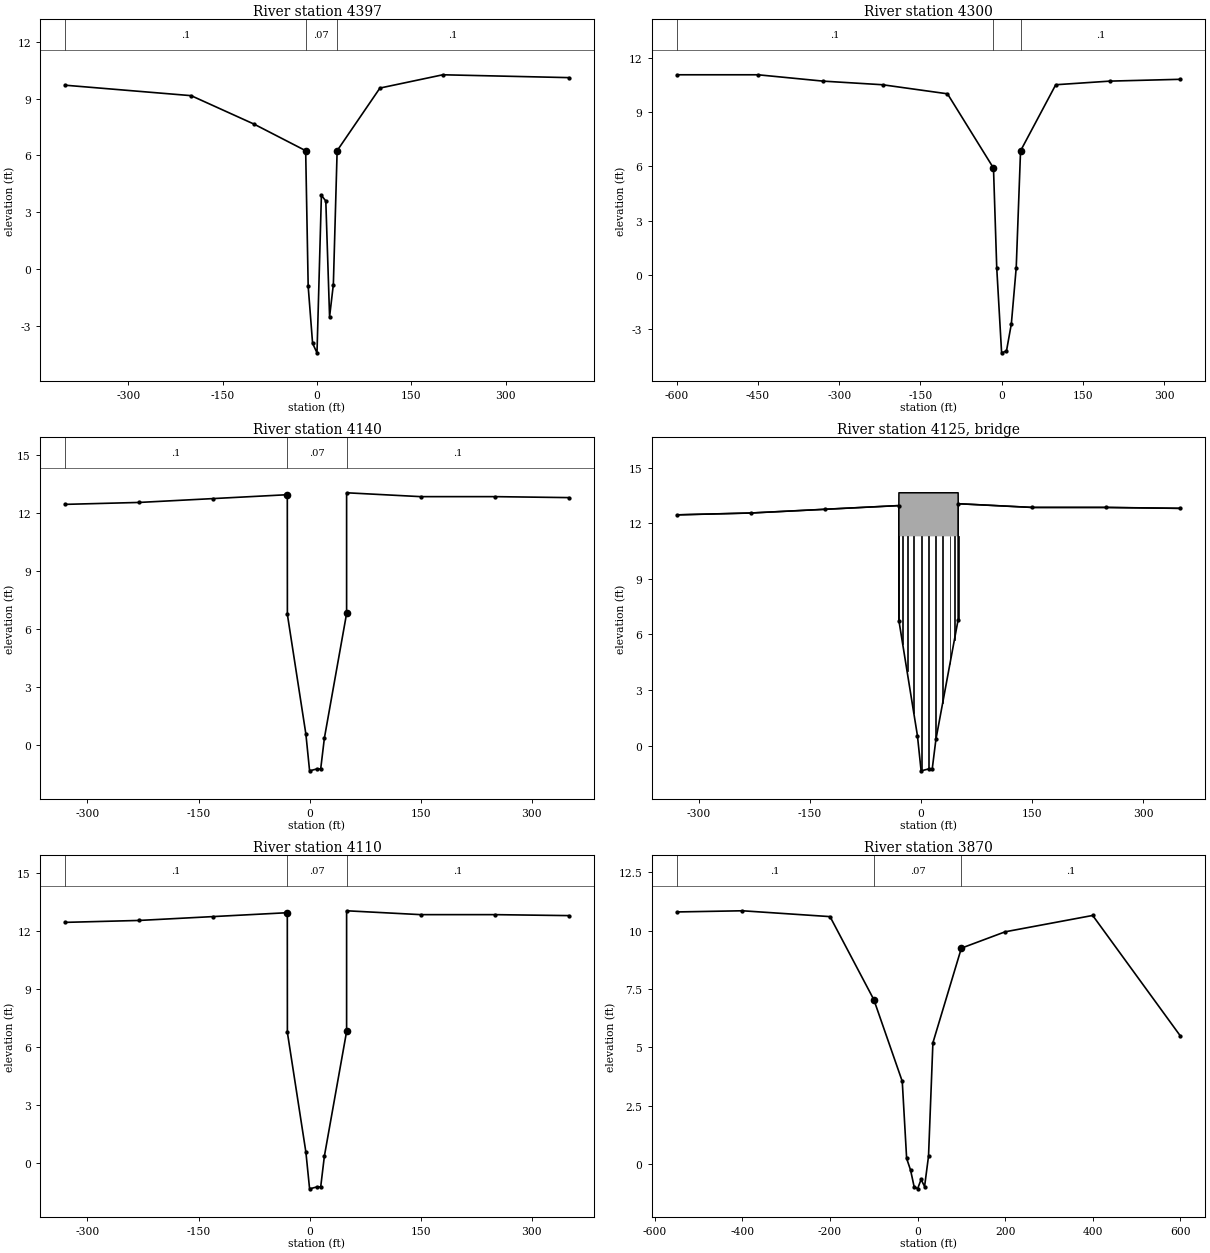
Type RM Length L Ch R =1,4397    ,97,97,97,0,0,0
Node Desc=SCS 238
#Sta/Elev= 15
    -400     9.7    -200    9.15    -100    7.65     -18    6.25     -14     -.9
      -7    -3.9       0    -4.4       7     3.9      14     3.6      20    -2.5
      26     -.8      32    6.25     100    9.55     200   10.25     400    10.1
#Mann=3,0
    -400      .1       0     -18     .07       0      32      .1       0
Bank Sta=-18,32
Exp/Cntr=0.3,0.1

Type RM Length L Ch R =1,4300    ,160,160,160,0,0,0
Node Desc=SCS 236
#Sta/Elev= 15
    -600   11.05    -450   11.05    -330    10.7    -220    10.5    -100      10
     -15     5.9      -9      .4       0    -4.3       9    -4.2      18    -2.7
      27      .4      35    6.85     100    10.5     200    10.7     330    10.8
#Mann=3,0
    -600      .1       0     -15     .07       0      35      .1       0
Bank Sta=-15,35
Exp/Cntr=0.3,0.1

Type RM Length L Ch R =1,4140    ,30,30,30,0,0,0
Node Desc=SCS 232
#Sta/Elev= 15
    -330   12.45    -230   12.55    -130   12.75   -30.1   12.95     -30    6.75
      -5     .55       0   -1.35      10   -1.25      15   -1.25      20     .35
      50     6.8      50   13.05     150   12.85     250   12.85     350    12.8
#Mann=3,0
    -330      .1       0   -30.1     .07       0      50      .1       0
Bank Sta=-30.1,50
Exp/Cntr=0.5,0.3

Type RM Length L Ch R =3,4125    ,,,,0,0,0
Node Desc=Bridge # 3 SCS STA 230
Bridge Culvert--1,0,-1,-1
Deck Dist Width WeirC Skew NumUp NumDn MinLoCord MaxHiCord MaxSubmerge Is_Ogee
0,30,2.7,,15,15,13.64,,0.95,0
    -330    -230    -130   -30.1     -30      -5       0      10      15      20
      50    50.1     150     250     350
   12.45   12.55   12.75   12.95   13.64   13.64   13.64   13.64   13.64   13.64
   13.64   13.05   12.85   12.85    12.8
   12.45   12.55   12.75   12.95   11.29   11.29   11.29   11.29   11.29   11.29
   11.29   13.05   12.85   12.85    12.8
    -330    -230    -130   -30.1     -30      -5       0      10      15      20
      50    50.1     150     250     350
   12.45   12.55   12.75   12.95   13.64   13.64   13.64   13.64   13.64   13.64
   13.64   13.05   12.85   12.85    12.8
   12.45   12.55   12.75   12.95   11.29   11.29   11.29   11.29   11.29   11.29
   11.29   13.05   12.85   12.85    12.8
Pier Skew, UpSta & Num, DnSta & Num=,-30, 2,-30, 2, 0, 0
     1.3     1.3
   -1.35   11.29
     1.3     1.3
   -1.35   11.29
Pier Skew, UpSta & Num, DnSta & Num=,-25, 2,-25, 2, 0, 0
     1.3     1.3
   -1.35   11.29
     1.3     1.3
   -1.35   11.29
Pier Skew, UpSta & Num, DnSta & Num=,-19, 2,-19, 2, 0, 0
     1.3     1.3
   -1.35   11.29
     1.3     1.3
   -1.35   11.29
Pier Skew, UpSta & Num, DnSta & Num=,-10, 2,-10, 2, 0, 0
     1.3     1.3
   -1.35   11.29
     1.3     1.3
   -1.35   11.29
Pier Skew, UpSta & Num, DnSta & Num=,0, 2,0, 2, 0, 0
     1.3     1.3
   -1.35   11.29
     1.3     1.3
   -1.35   11.29
Pier Skew, UpSta & Num, DnSta & Num=,10, 2,10, 2, 0, 0
     1.3     1.3
   -1.35   11.29
     1.3     1.3
   -1.35   11.29
Pier Skew, UpSta & Num, DnSta & Num=,20, 2,20, 2, 0, 0
     1.3     1.3
   -1.35   11.29
     1.3     1.3
   -1.35   11.29
Pier Skew, UpSta & Num, DnSta & Num=,29, 2,29, 2, 0, 0
     1.3     1.3
   -1.35   11.29
     1.3     1.3
   -1.35   11.29
Pier Skew, UpSta & Num, DnSta & Num=,39, 2,39, 2, 0, 0
     1.3     1.3
   -1.35   11.29
     1.3     1.3
   -1.35   11.29
Pier Skew, UpSta & Num, DnSta & Num=,45, 2,45, 2, 0, 0
     1.3     1.3
   -1.35   11.29
     1.3     1.3
   -1.35   11.29
Pier Skew, UpSta & Num, DnSta & Num=,50, 2,50, 2, 0, 0
     1.3     1.3
   -1.35   11.29
     1.3     1.3
   -1.35   11.29
BR Coef= 0, 0,-1,1.05, 0,,,0.8006408,0,2,2,11.29

Type RM Length L Ch R =1,4110    ,240,240,240,0,0,0
Node Desc=SCS 230
#Sta/Elev= 15
    -330   12.45    -230   12.55    -130   12.75   -30.1   12.95     -30    6.75
      -5     .55       0   -1.35      10   -1.25      15   -1.25      20     .35
      50     6.8      50   13.05     150   12.85     250   12.85     350    12.8
#Mann=3,0
    -330      .1       0   -30.1     .07       0      50      .1       0
Bank Sta=-30.1,50
Exp/Cntr=0.3,0.1

Type RM Length L Ch R =1,3870    ,420,420,420,0,0,0
Node Desc=SCS 228
#Sta/Elev= 17
    -550    10.8    -400   10.85    -200    10.6    -100    7.05     -35    3.55
     -25     .25     -16    -.25      -8    -.95       0   -1.05       8    -.65
      16    -.95      25     .35      35     5.2     100    9.25     200    9.95
     400   10.65     600     5.5
#Mann=3,0
    -550      .1       0    -100     .07       0     100      .1       0
Bank Sta=-100,100
Exp/Cntr=0.3,0.1

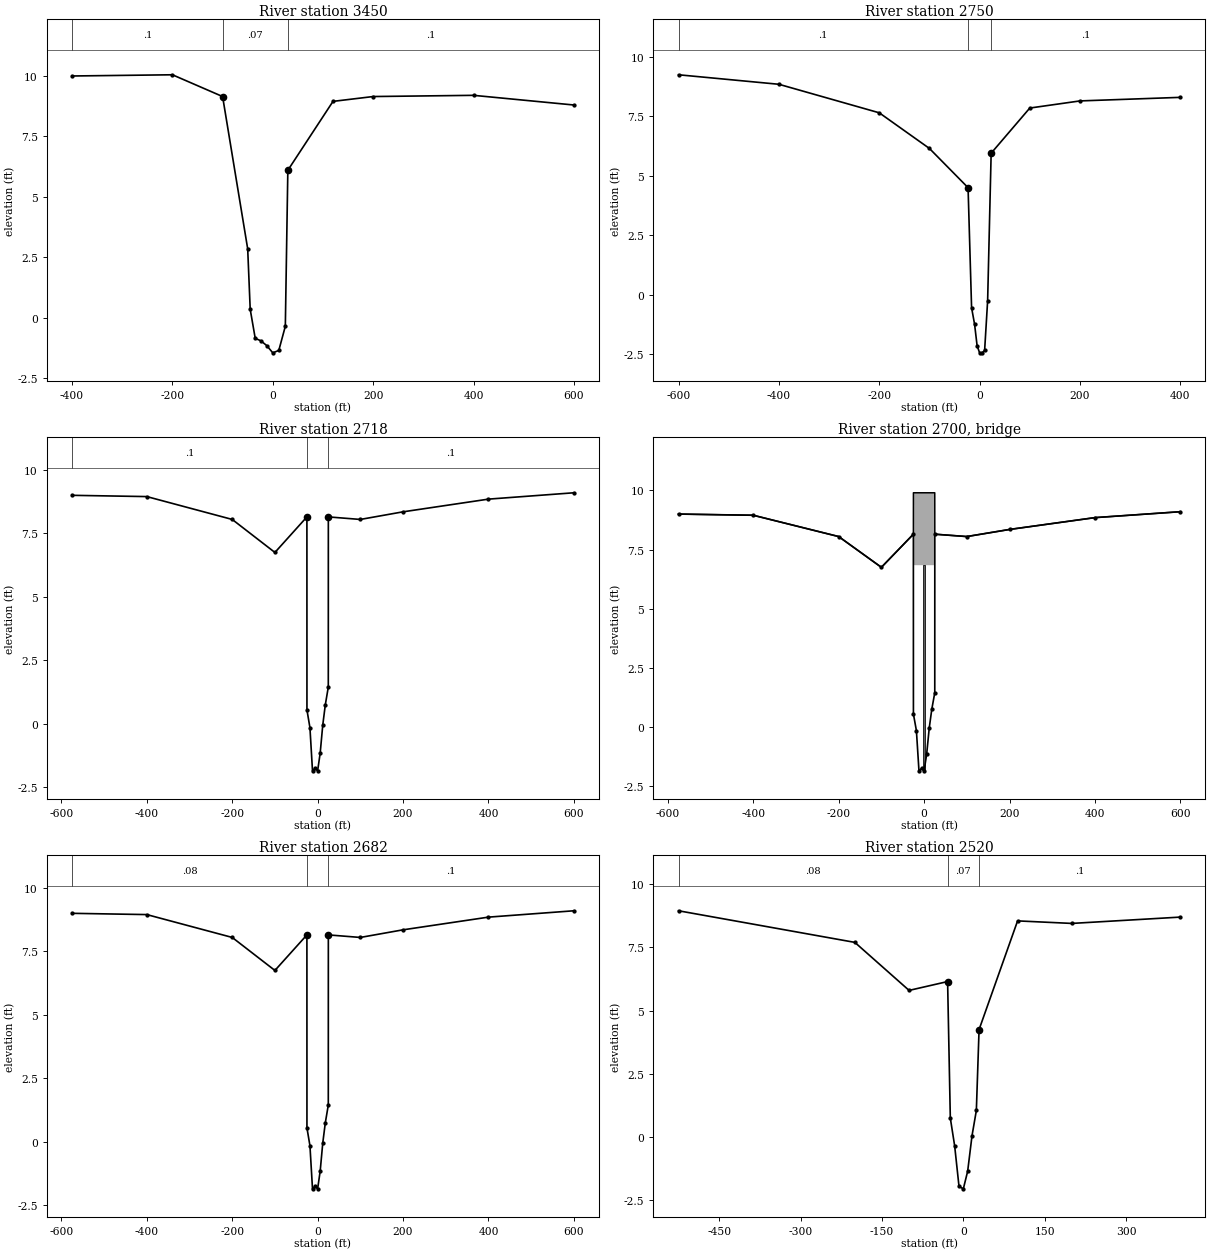
Type RM Length L Ch R =1,3450    ,700,700,700,0,0,0
Node Desc=SCS 226
#Sta/Elev= 16
    -400      10    -200   10.05    -100    9.15     -50    2.85     -45     .35
     -35    -.85     -24    -.95     -12   -1.15       0   -1.45      12   -1.35
      25    -.35      30     6.1     120    8.95     200    9.15     400     9.2
     600     8.8
#Mann=3,0
    -400      .1       0    -100     .07       0      30      .1       0
Bank Sta=-100,30
Exp/Cntr=0.3,0.1

Type RM Length L Ch R =1,2750    ,32,32,32,0,0,0
Node Desc=SCS 224
#Sta/Elev= 16
    -600    9.25    -400    8.85    -200    7.65    -100    6.15     -23     4.5
     -16    -.55     -10   -1.25      -5   -2.15       0   -2.45       5   -2.45
      10   -2.35      16    -.25      23    5.95     100    7.85     200    8.15
     400     8.3
#Mann=3,0
    -600      .1       0     -23     .07       0      23      .1       0
Bank Sta=-23,23
Exp/Cntr=0.3,0.1

Type RM Length L Ch R =1,2718    ,36,36,36,0,0,0
Node Desc=SCS 220
#Sta/Elev= 19
    -575       9    -400    8.95    -200    8.05    -100    6.75   -25.1    8.15
     -25     .55     -18    -.15     -12   -1.85      -6   -1.75       0   -1.85
       6   -1.15      12    -.05      18     .75      25    1.45    25.1    8.15
     100    8.05     200    8.35     400    8.85     600     9.1
#Mann=3,0
    -575      .1       0   -25.1     .07       0    25.1      .1       0
Bank Sta=-25.1,25.1
Exp/Cntr=0.5,0.3

Type RM Length L Ch R =3,2700    ,,,,0,0,0
Node Desc=Bridge # 2 SCS STA 219
Bridge Culvert--1,0,-1,-1
Deck Dist Width WeirC Skew NumUp NumDn MinLoCord MaxHiCord MaxSubmerge Is_Ogee
0,36,2.7,,19,19,8.15,,0.95,0
    -575    -400    -200    -100   -25.1     -25     -18     -12      -6       0
       6      12      18      25    25.1     100     200     400     600
       9    8.95    8.05    6.75    8.15     9.9     9.9     9.9     9.9     9.9
     9.9     9.9     9.9     9.9    8.15    8.05    8.35    8.85     9.1
       9    8.95    8.05    6.75    8.15    6.84    6.84    6.84    6.84    6.84
    6.84    6.84    6.84    6.84    8.15    8.05    8.35    8.85     9.1
    -575    -400    -200    -100   -25.1     -25     -18     -12      -6       0
       6      12      18      25    25.1     100     200     400     600
       9    8.95    8.05    6.75    8.15     9.9     9.9     9.9     9.9     9.9
     9.9     9.9     9.9     9.9    8.15    8.05    8.35    8.85     9.1
       9    8.95    8.05    6.75    8.15    6.84    6.84    6.84    6.84    6.84
    6.84    6.84    6.84    6.84    8.15    8.05    8.35    8.85     9.1
Pier Skew, UpSta & Num, DnSta & Num=,-0.0500002, 2,-0.0500002, 2, 0, 0
     3.5     3.5
   -1.85       9
     3.5     3.5
   -1.85       9
BR Coef= 0, 0,-1,1.25, 0,,,0.8006408,0,2,2,9

Type RM Length L Ch R =1,2682    ,162,162,162,0,0,0
Node Desc=SCS 218
#Sta/Elev= 19
    -575       9    -400    8.95    -200    8.05    -100    6.75   -25.1    8.15
     -25     .55     -18    -.15     -12   -1.85      -6   -1.75       0   -1.85
       6   -1.15      12    -.05      18     .75      25    1.45    25.1    8.15
     100    8.05     200    8.35     400    8.85     600     9.1
#Mann=3,0
    -575     .08       0   -25.1     .07       0    25.1      .1       0
Bank Sta=-25.1,25.1
Exp/Cntr=1.3,0.1

Type RM Length L Ch R =1,2520    ,370,370,370,0,0,0
Node Desc=SCS 216
#Sta/Elev= 15
    -525    8.95    -200     7.7    -100     5.8     -29    6.15     -24     .75
     -16    -.35      -8   -1.95       0   -2.05       8   -1.35      16     .05
      24    1.05      29    4.25     100    8.55     200    8.45     400     8.7
#Mann=3,0
    -525     .08       0     -29     .07       0      29      .1       0
#XS Ineff= 2 , 0
             -29    6.15      29            4.25
Bank Sta=-29,29
Exp/Cntr=1.3,0.1

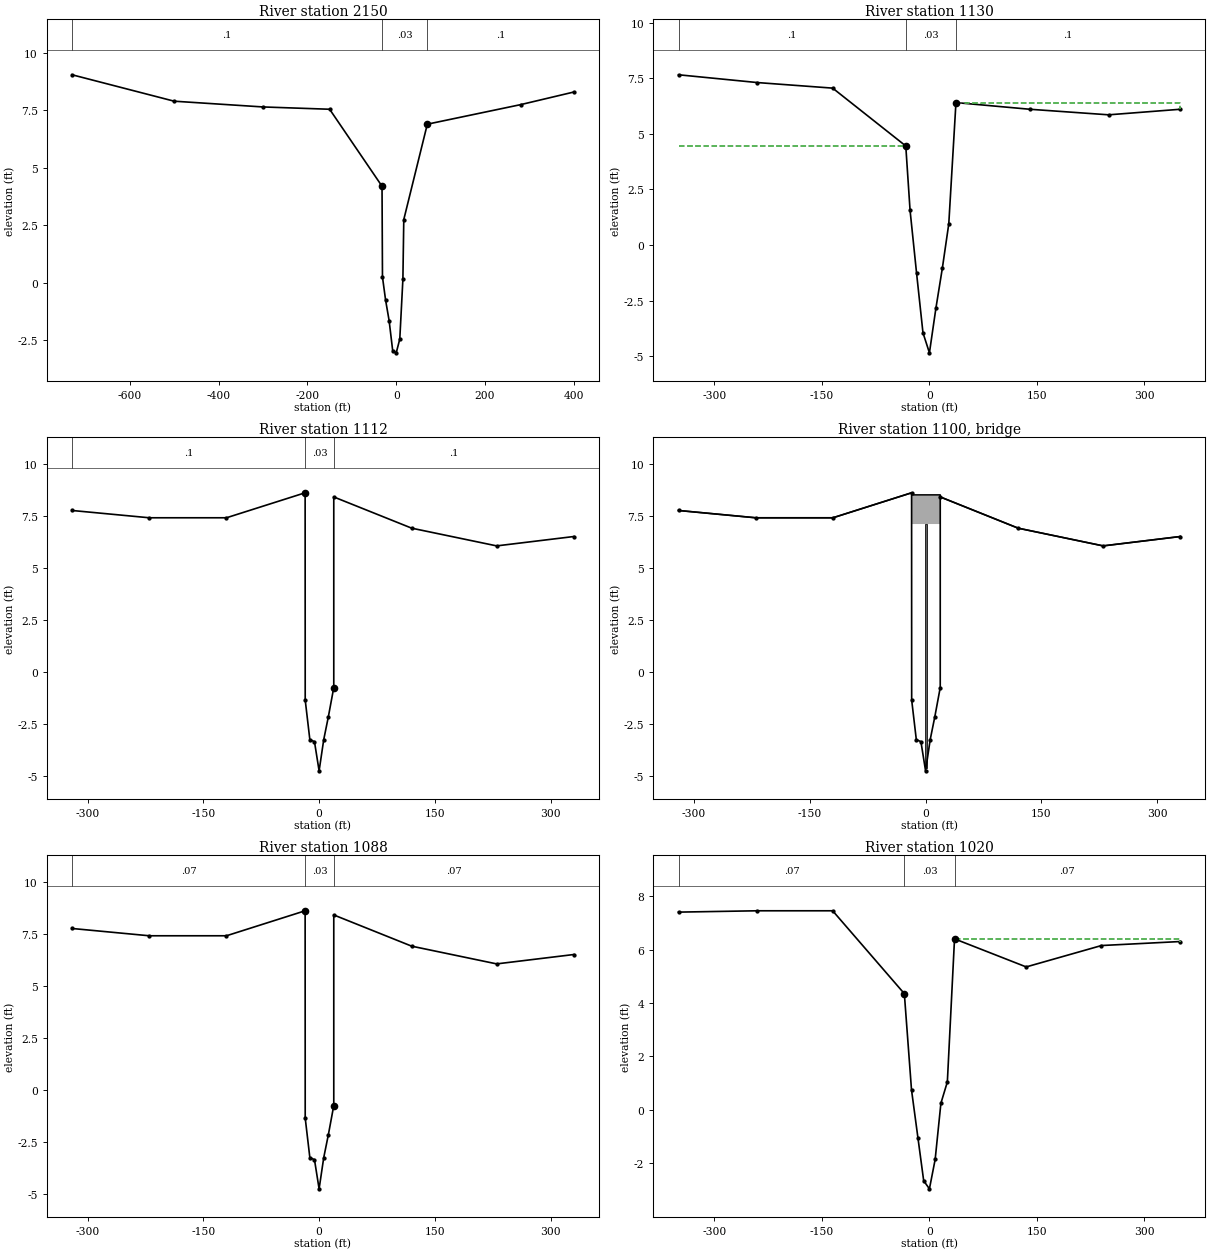
Type RM Length L Ch R =1,2150    ,1020,1020,1020,0,0,0
Node Desc=SCS 214
#Sta/Elev= 16
    -730    9.05    -500     7.9    -300    7.65    -150    7.55     -32     4.2
     -31     .25     -24    -.75     -16   -1.65      -8   -2.95       0   -3.05
       8   -2.45      15     .15      17    2.75      70     6.9     280    7.75
     400     8.3
#Mann=3,0
    -730      .1       0     -32     .03       0      70      .1       0
Bank Sta=-32,70
Exp/Cntr=1.3,0.1

Type RM Length L Ch R =1,1130    ,18,18,18,0,0,0
Node Desc=SCS 212
#Sta/Elev= 15
    -350    7.65    -240     7.3    -135    7.05     -33    4.45     -27    1.55
     -18   -1.25      -9   -3.95       0   -4.85       9   -2.85      18   -1.05
      27     .95      37     6.4     140     6.1     250    5.85     350     6.1
#Mann=3,0
    -350      .1       0     -33     .03       0      37      .1       0
#XS Ineff= 2 , 0
             -33    4.45      37             6.4
Bank Sta=-33,37
Exp/Cntr=1.3,0.1

Type RM Length L Ch R =1,1112    ,24,24,24,0,0,0
Node Desc=SCS 208
#Sta/Elev= 15
    -320    7.75    -220     7.4    -120     7.4   -18.1     8.6     -18   -1.35
     -12   -3.25      -6   -3.35       0   -4.75       6   -3.25      12   -2.15
      19    -.75      19     8.4     120     6.9     230    6.05     330     6.5
#Mann=3,0
    -320      .1       0   -18.1     .03       0      19      .1       0
Bank Sta=-18.1,19
Exp/Cntr=0.5,0.3

Type RM Length L Ch R =3,1100    ,,,,0,0,0
Node Desc=Bridge # 1 SCS STA 207
Bridge Culvert--1,0,-1,-1
Deck Dist Width WeirC Skew NumUp NumDn MinLoCord MaxHiCord MaxSubmerge Is_Ogee
0,24,2.7,,15,15,8.5,,0.95,0
    -320    -220    -120     -18     -18     -12      -6       0       6      12
      19    19.1     120     230     330
    7.75     7.4     7.4     8.6     8.5     8.5     8.5     8.5     8.5     8.5
     8.5     8.4     6.9    6.05     6.5
    7.75     7.4     7.4     8.6     7.1     7.1     7.1     7.1     7.1     7.1
     7.1     8.4     6.9    6.05     6.5
    -320    -220    -120     -18     -18     -12      -6       0       6      12
      19    19.1     120     230     330
    7.75     7.4     7.4     8.6     8.5     8.5     8.5     8.5     8.5     8.5
     8.5     8.4     6.9    6.05     6.5
    7.75     7.4     7.4     8.6     7.1     7.1     7.1     7.1     7.1     7.1
     7.1     8.4     6.9    6.05     6.5
Pier Skew, UpSta & Num, DnSta & Num=,0.5, 2,0.5, 2, 0, 0
       3       3
   -4.75     7.1
       3       3
   -4.75     7.1
BR Coef= 0, 0,-1,1.25, 0,,,0.8006408,0,2,2,7.1

Type RM Length L Ch R =1,1088    ,68,68,68,0,0,0
Node Desc=SCS 206
#Sta/Elev= 15
    -320    7.75    -220     7.4    -120     7.4   -18.1     8.6     -18   -1.35
     -12   -3.25      -6   -3.35       0   -4.75       6   -3.25      12   -2.15
      19    -.75      19     8.4     120     6.9     230    6.05     330     6.5
#Mann=3,0
    -320     .07       0   -18.1     .03       0      19     .07       0
Bank Sta=-18.1,19
Exp/Cntr=0.3,0.1

Type RM Length L Ch R =1,1020    ,820,820,820,0,0,0
Node Desc=SCS 204
#Sta/Elev= 15
    -350     7.4    -240    7.45    -135    7.45     -35    4.35     -25     .75
     -16   -1.05      -8   -2.65       0   -2.95       8   -1.85      16     .25
      25    1.05      35     6.4     135    5.35     240    6.15     350     6.3
#Mann=3,0
    -350     .07       0     -35     .03       0      35     .07       0
#XS Ineff= 2 , 0
             -35    4.35      35             6.4
Bank Sta=-35,35
Exp/Cntr=0.3,0.1

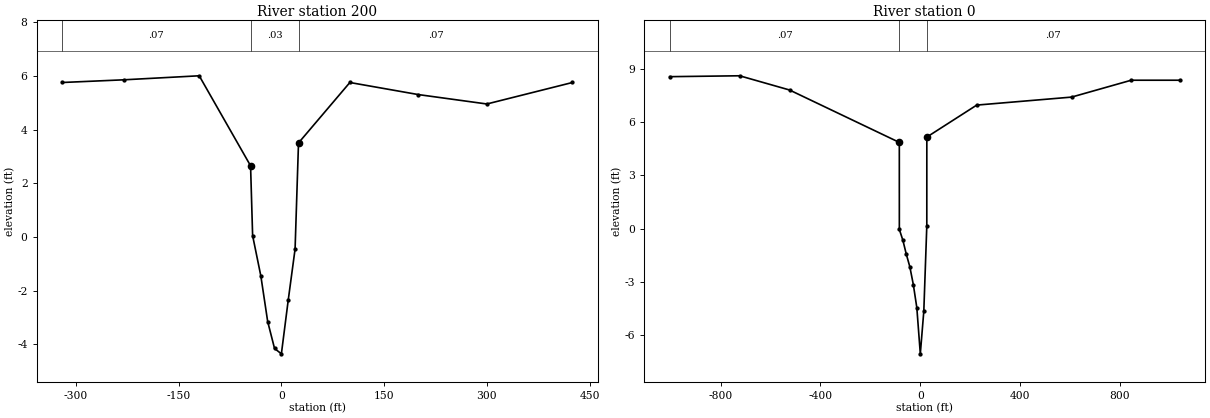
Type RM Length L Ch R =1,200     ,200,200,200,0,0,0
Node Desc= SCS 202
#Sta/Elev= 16
    -320    5.75    -230    5.85    -120       6     -45    2.65     -42     .05
     -30   -1.45     -20   -3.15     -10   -4.15       0   -4.35      10   -2.35
      20    -.45      25     3.5     100    5.75     200     5.3     300    4.95
     425    5.75
#Mann=3,0
    -320     .07       0     -45     .03       0      25     .07       0
Bank Sta=-45,25
Exp/Cntr=0.3,0.1

Type RM Length L Ch R =1,0       ,0,0,0,0,0,0
Node Desc= Confl. w/ Imperial River
#Sta/Elev= 18
   -1004    8.55    -724     8.6    -524     7.8   -84.1    4.85     -84    -.05
     -70    -.65     -56   -1.45     -42   -2.15     -28   -3.15     -14   -4.45
       0   -7.05      14   -4.65      26     .15    26.1    5.15     226    6.95
     606     7.4     845    8.35    1040    8.35
#Mann=3,0
   -1004     .07       0   -84.1     .03       0    26.1     .07       0
Bank Sta=-84.1,26.1
Exp/Cntr=0.3,0.1