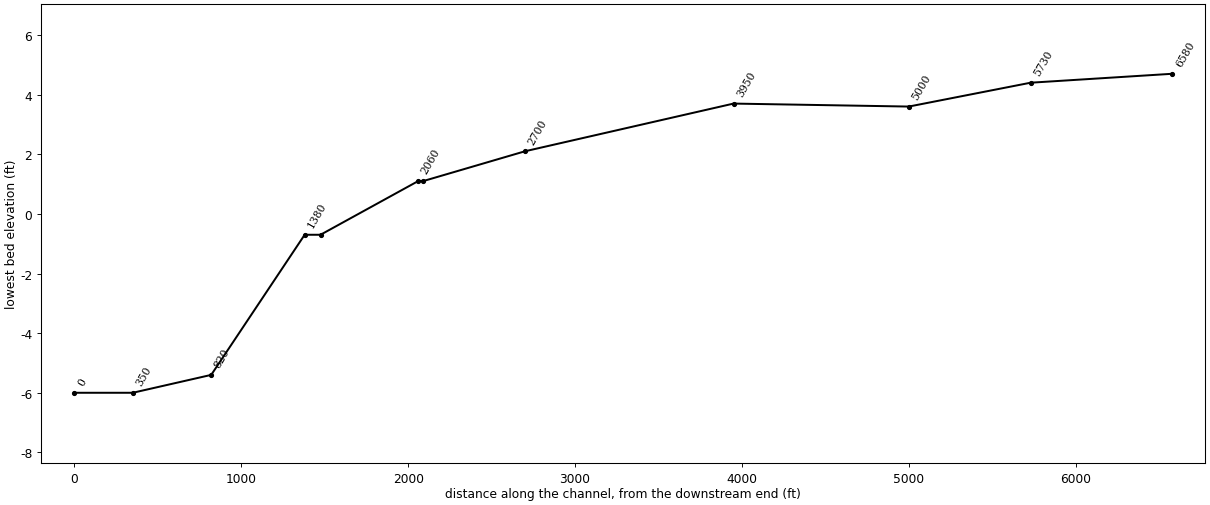
--- olgaex.prj (project) ---

Proj Title=EXISTING OLGA CREEK WATERSHED
Current Plan=p02
Default Exp/Contr=0.3,0.1
English Units
Geom File=g01
Flow File=f01
Plan File=p02
Plan File=p01

--- olgaex.p02 (plan) ---

Plan Title=OLGA PLAN DATA 01
Short Identifier=Plan 01
Geom File=g01
Flow File=f01
Multiple Comp Mode
Subcritical Flow
K Sum by GR= 0
Std Step Tol= .01
Critical Tol= .01
Num of Std Step Trials= 20
Max Error Tol= .3
Flow Tol Ratio= .001
Log Output Level= 0
Friction Slope Method= 1
Parabolic Critical Depth

--- olgaex.f01 (steady flow) ---

Flow Title=OLGA FLOW DATA
Number of Flows and Profiles and Boundary= 5, 4, 1
Rch & RM=OLGA CREEK  ,6580
      20      50     105     145
Rch & RM=OLGA CREEK  ,3950
      20      50     105     145
Rch & RM=OLGA CREEK  ,2090
      20      50     105     145
Rch & RM=OLGA CREEK  ,1380
      20      55     105     145
Rch & RM=OLGA CREEK  ,0
      30      85     160     225
Boundary for Rch & Prof#=OLGA CREEK  , 1
Up Type= 2
Up Value=0
Dn Type= 1
Dn Value=2.5
Boundary for Rch & Prof#=OLGA CREEK  , 2
Up Type= 2
Up Value=0
Dn Type= 1
Dn Value=2.5
Boundary for Rch & Prof#=OLGA CREEK  , 3
Up Type= 2
Up Value=0
Dn Type= 1
Dn Value=2.5
Boundary for Rch & Prof#=OLGA CREEK  , 4
Up Type= 2
Up Value=0
Dn Type= 1
Dn Value=2.5

--- olgaex.g01 (geometry) ---

Geom Title=OLGA GEOMETRY DATA
ViewRect= 0, 1, 1, 0
Reach=OLGA CREEK
Rch X Y Up & X Y Dn=0.491018,0.2969432,0.491018,0.8973799
Rch Arrow X Y Up & X Y Dn=0,0,0,0
Rch Type=0

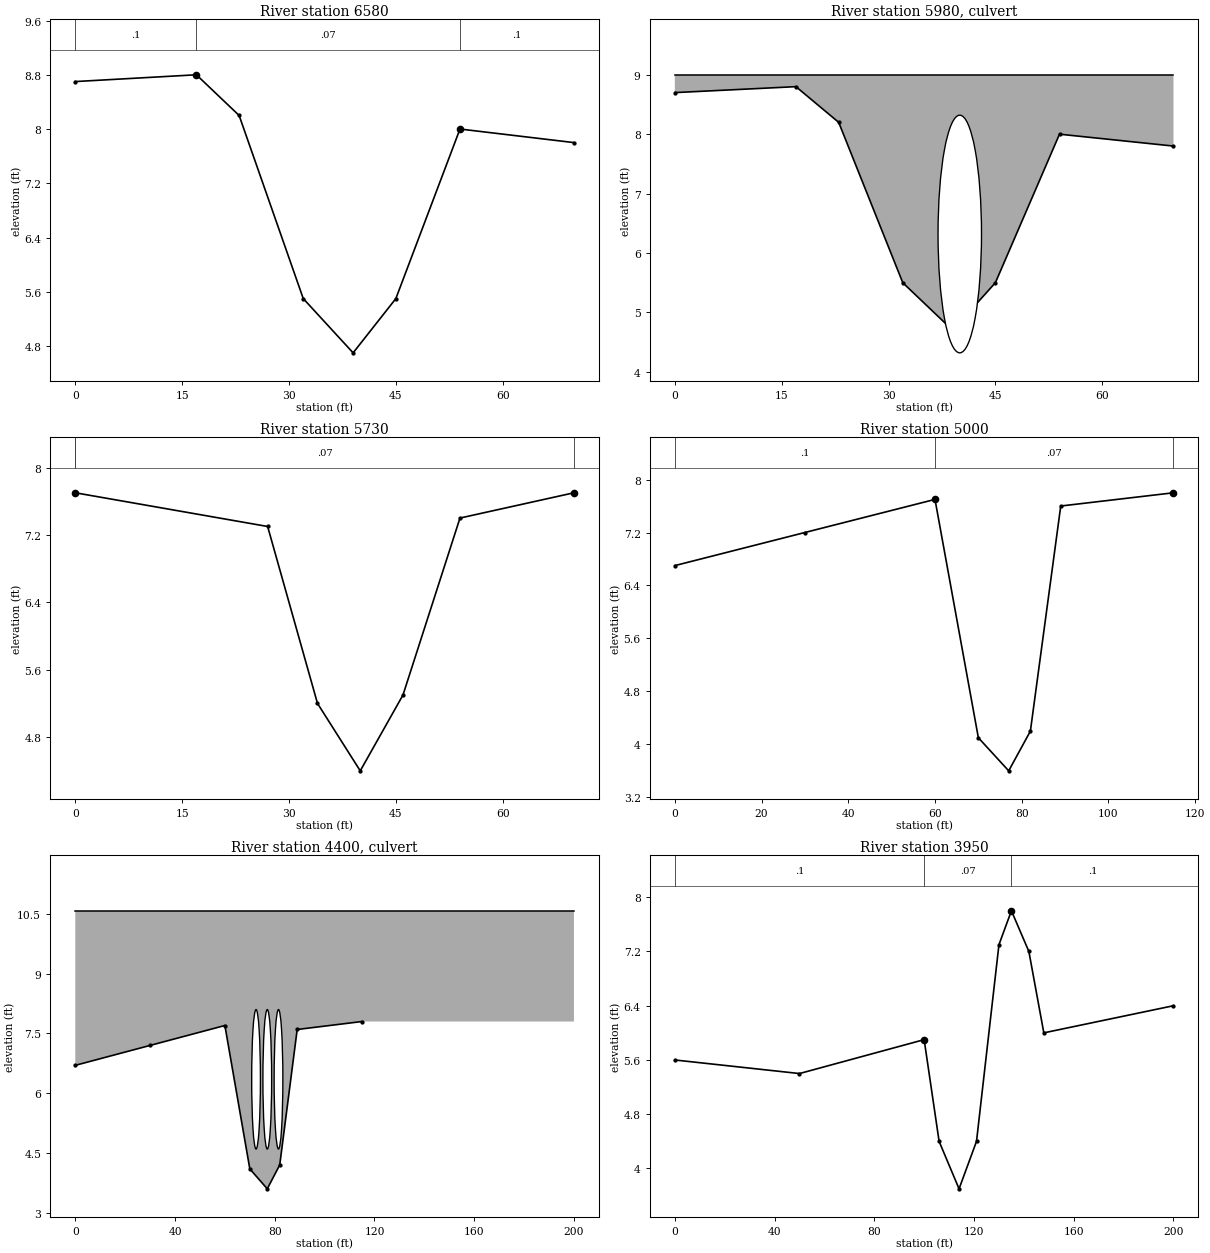
Type RM Length L Ch R =1,6580    ,850,850,850,0,0,0
Node Desc=CHANNEL
#Sta/Elev= 8
       0     8.7      17     8.8      23     8.2      32     5.5      39     4.7
      45     5.5      54       8      70     7.8
#Mann=3,0
       0      .1       0      17     .07       0      54      .1       0
Bank Sta=17,54
Exp/Cntr=0.3,0.1

Type RM Length L Ch R =2,5980    ,,,,0,0,0
Node Desc=48"x74" CMP DIRT ROAD
Bridge Culvert--1,0,-1,-1
Deck Dist Width WeirC Skew NumUp NumDn MinLoCord MaxHiCord MaxSubmerge Is_Ogee
600,19,2.6,,7,7,,,0.95,0
       0      27      34      40      46      54      70
       9       9       9       9       9       9       9
                                                        
       0      27      34      40      46      54      70
       9       9       9       9       9       9       9
                                                        
Abutment Skew #Up #Dn=, 2, 2
       0      70
       9       9
       0      70
       9       9
Culvert=4,4,6.1,19,0.013,0.3,0.5,29,1,4.32,40,4.45,40,Culvert #1  , 0

Type RM Length L Ch R =1,5730    ,730,730,730,0,0,0
Node Desc=CHANNEL
#Sta/Elev= 7
       0     7.7      27     7.3      34     5.2      40     4.4      46     5.3
      54     7.4      70     7.7
#Mann=3,0
       0      .1       0       0     .07       0      70      .1       0
Bank Sta=0,70
Exp/Cntr=0.3,0.1

Type RM Length L Ch R =1,5000    ,1050,1050,1050,0,0,0
Node Desc=CHANNEL
#Sta/Elev= 8
       0     6.7      30     7.2      60     7.7      70     4.1      77     3.6
      82     4.2      89     7.6     115     7.8
#Mann=3,0
       0      .1       0      60     .07       0     115      .1       0
Bank Sta=60,115
Exp/Cntr=0.3,0.1

Type RM Length L Ch R =2,4400    ,,,,0,0,0
Node Desc=(3) 42" RCP STATE ROAD 80
Bridge Culvert--1,0,-1,-1
Deck Dist Width WeirC Skew NumUp NumDn MinLoCord MaxHiCord MaxSubmerge Is_Ogee
600,101.5,2.6,,11,11,,,0.95,0
       0      50     100     106     114     121     130     135     142     148
     200
   10.58   10.58   10.58   10.58   10.58   10.58   10.58   10.58   10.58   10.58
   10.58
                                                                                
        
       0      50     100     106     114     121     130     135     142     148
     200
   10.58   10.58   10.58   10.58   10.58   10.58   10.58   10.58   10.58   10.58
   10.58
                                                                                
        
Abutment Skew #Up #Dn=, 2, 2
       0     200
   10.58   10.58
       0     200
   10.58   10.58
Multiple Barrel Culv=1,3.5,,113,0.013,0.5,0.3,1,1,4.6,4.4, 3,Culvert #1  , 0
    72.5   108.5      77     113    81.5   117.5

Type RM Length L Ch R =1,3950    ,1250,1250,1250,0,0,0
Node Desc=CHANNEL
#Sta/Elev= 11
       0     5.6      50     5.4     100     5.9     106     4.4     114     3.7
     121     4.4     130     7.3     135     7.8     142     7.2     148       6
     200     6.4
#Mann=3,0
       0      .1       0     100     .07       0     135      .1       0
Bank Sta=100,135
Exp/Cntr=0.3,0.1

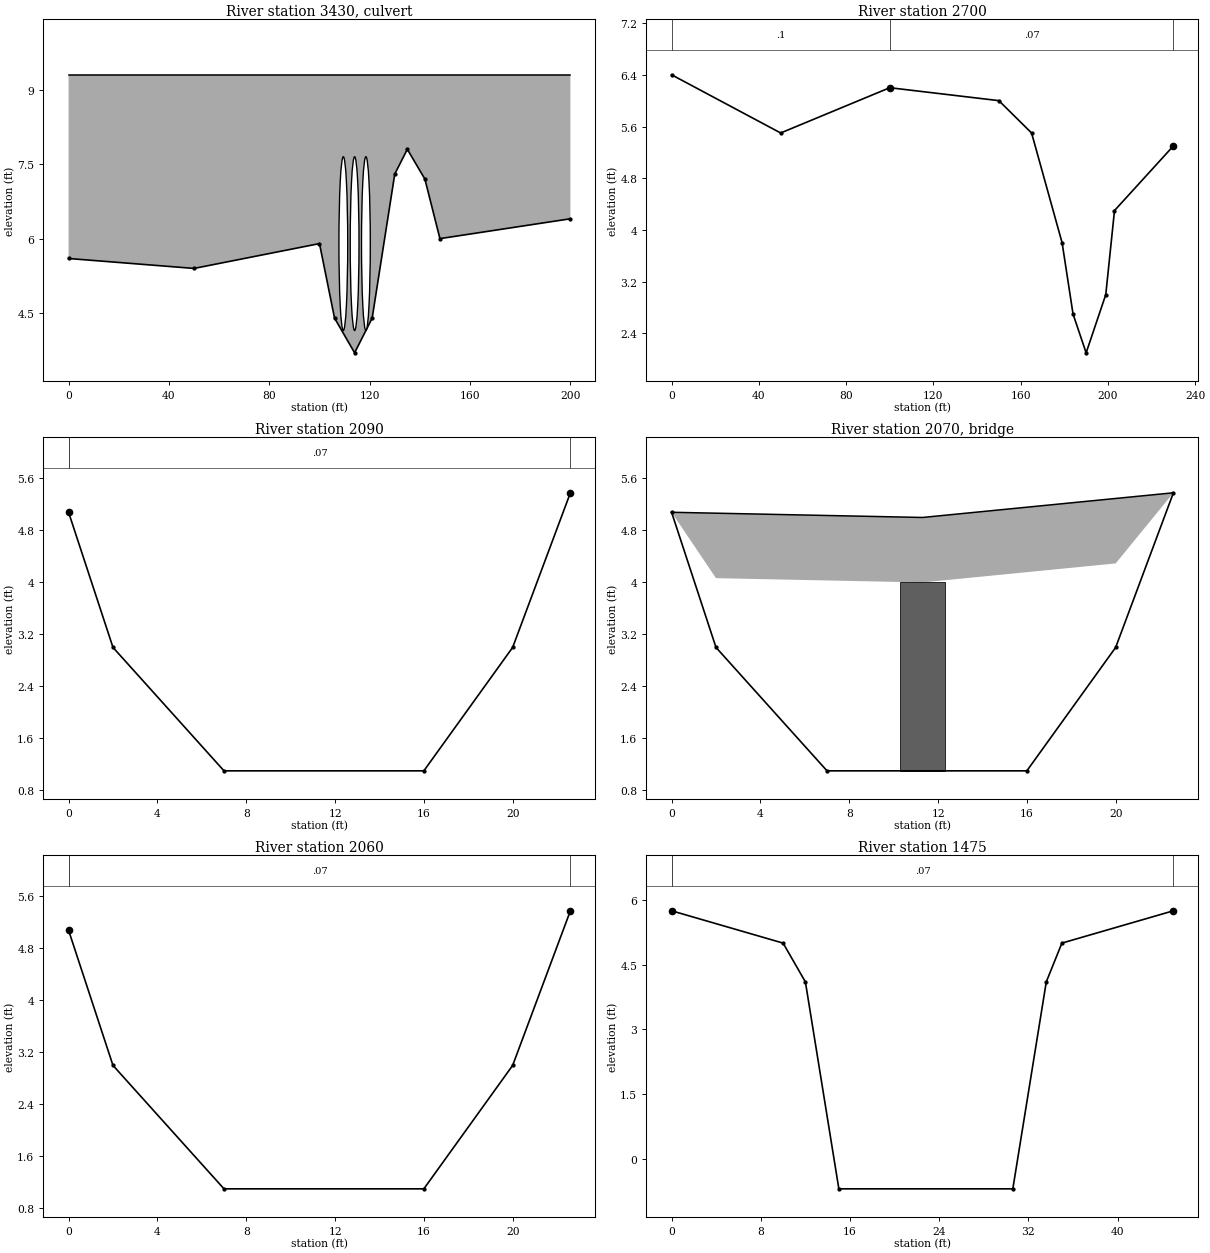
Type RM Length L Ch R =2,3430    ,,,,0,0,0
Node Desc=(3) 42" RCP SOUTH OLGA ROAD
Bridge Culvert--1,0,-1,-1
Deck Dist Width WeirC Skew NumUp NumDn MinLoCord MaxHiCord MaxSubmerge Is_Ogee
520,27.5,2.6,,10,10,,,0.95,0
       0      50     106     114     121     130     135     142     148     200
     9.3     9.3     9.3     9.3     9.3     9.3     9.3     9.3     9.3     9.3
                                                                                
       0      50     106     114     121     130     135     142     148     200
     9.3     9.3     9.3     9.3     9.3     9.3     9.3     9.3     9.3     9.3
                                                                                
Abutment Skew #Up #Dn=, 10, 10
       0      50     100     106     114     121     130     135     142     250
     9.3     9.3     9.3     9.3     9.3     9.3     9.3     9.3     9.3     9.3
       0      50     100     106     114     121     130     135     142     250
     9.3     9.3     9.3     9.3     9.3     9.3     9.3     9.3     9.3     9.3
Multiple Barrel Culv=1,3.5,,40,0.013,0.3,0.5,1,1,4.15,4.15, 3,Culvert #1  , 0
   109.5   185.5     114     190   118.5   194.5

Type RM Length L Ch R =1,2700    ,610,610,610,0,0,0
Node Desc=CHANNEL
#Sta/Elev= 11
       0     6.4      50     5.5     100     6.2     150       6     165     5.5
     179     3.8     184     2.7     190     2.1     199       3     203     4.3
     230     5.3
#Mann=3,0
       0      .1       0     100     .07       0     230      .1       0
Bank Sta=100,230
Exp/Cntr=0.3,0.1

Type RM Length L Ch R =1,2090    ,30,30,30,0,0,0
Node Desc=CHANNEL
#Sta/Elev= 6
       0    5.08       2       3       7     1.1      16     1.1      20       3
    22.6    5.38
#Mann=3,0
       0      .1       0       0     .07       0    22.6      .1       0
Bank Sta=0,22.6
Exp/Cntr=0.3,0.1

Type RM Length L Ch R =3,2070    ,,,,0,0,0
Node Desc=FOOT BRIDGE
Bridge Culvert--1,0,-1,-1
Deck Dist Width WeirC Skew NumUp NumDn MinLoCord MaxHiCord MaxSubmerge Is_Ogee
20,8,2.8,,3,3,,,0.95,0
       0    11.3    22.6
    5.08       5    5.38
    4.08       4    4.38
       0    11.3    22.6
    5.08       5    5.38
    4.08       4    4.38
Pier Skew, UpSta & Num, DnSta & Num=,11.3, 4,11.3, 4, 0, 0
       2       2       1       1
     1.1       2       2       4
       2       2       1       1
     1.1       2       2       4
BR Coef= 1, 0, 0,, 0,,,0.8,0,0,1,

Type RM Length L Ch R =1,2060    ,585,585,585,0,0,0
Node Desc=CHANNEL
#Sta/Elev= 6
       0    5.08       2       3       7     1.1      16     1.1      20       3
    22.6    5.38
#Mann=3,0
       0      .1       0       0     .07       0    22.6      .1       0
Bank Sta=0,22.6
Exp/Cntr=0.3,0.1

Type RM Length L Ch R =1,1475    ,95,95,95,0,0,0
Node Desc=CHANNEL
#Sta/Elev= 8
       0    5.75      10       5      12     4.1      15     -.7    30.6     -.7
    33.6     4.1      35       5      45    5.75
#Mann=3,0
       0      .1       0       0     .07       0      45      .1       0
Bank Sta=0,45
Exp/Cntr=0.3,0.1

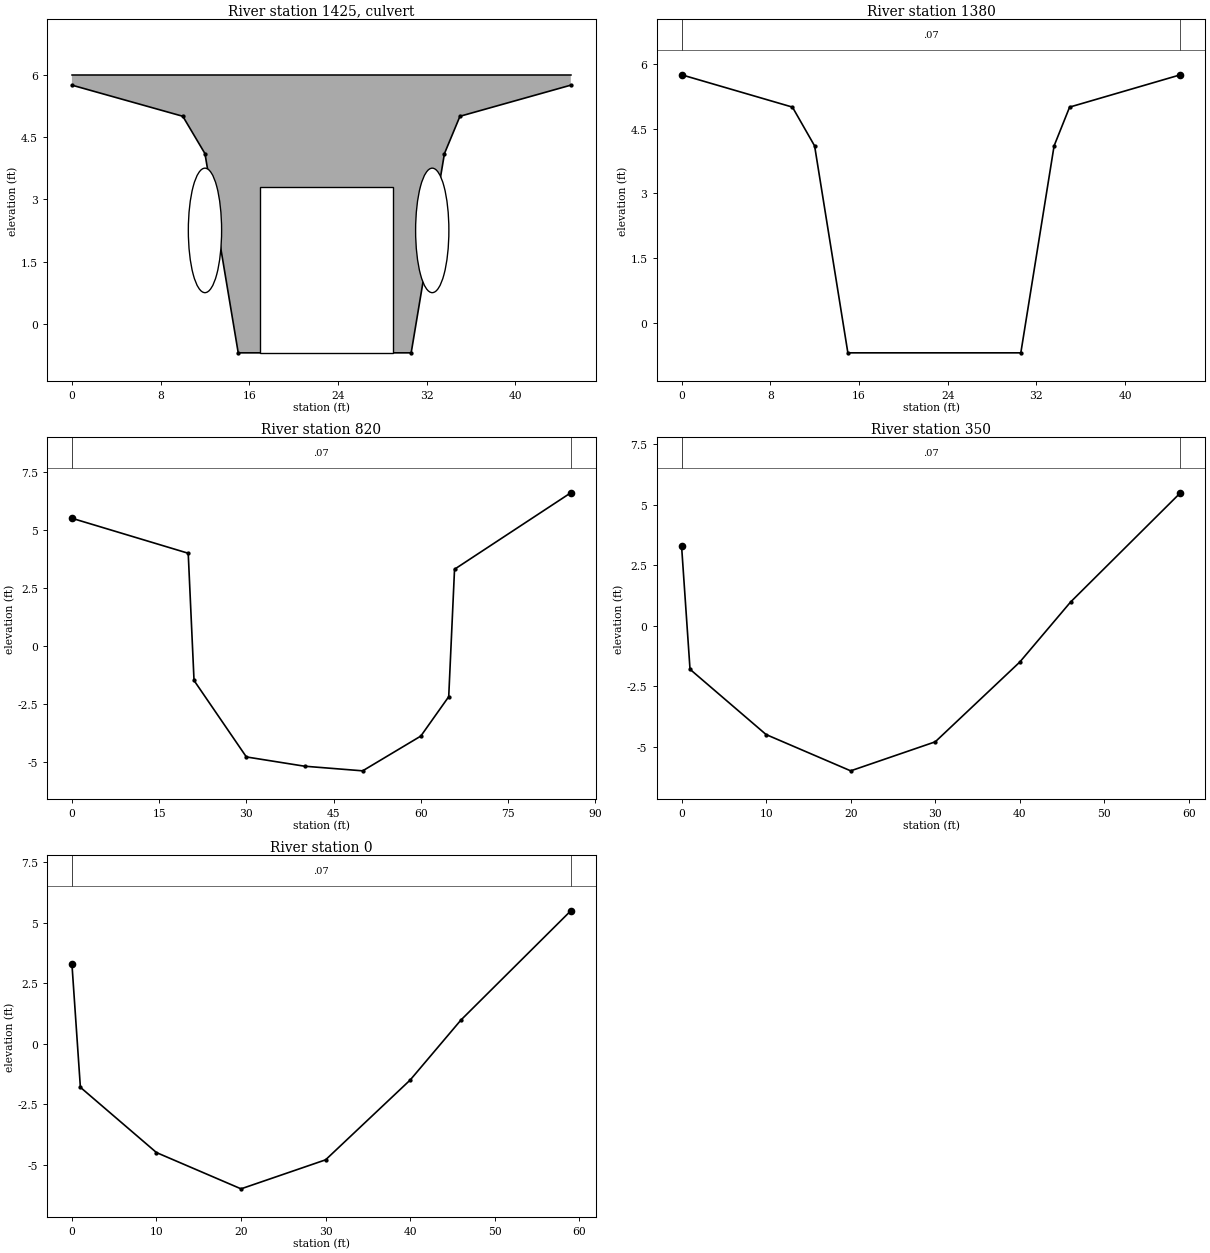
Type RM Length L Ch R =2,1425    ,,,,0,0,0
Node Desc=B.C & (2) 36" AT OLD OLGA ROAD
Bridge Culvert--1,0,-1,-1
Deck Dist Width WeirC Skew NumUp NumDn MinLoCord MaxHiCord MaxSubmerge Is_Ogee
40,18,2.8,,8,8,6,,0.95,0
       0      10      12      15    30.6    33.6      35      45
       6       6       6       6       6       6       6       6
                                                                
       0      10      12      15    30.6    33.6      35      45
       6       6       6       6       6       6       6       6
                                                                
Abutment Skew #Up #Dn=, 8, 8
       0      10      12      15    30.6    33.6      35      45
       6       6       6       6       6       6       6       6
       0      10      12      15    30.6    33.6      35      45
       6       6       6       6       6       6       6       6
Multiple Barrel Culv=1,3,,18,0.013,0.3,0.5,1,1,0.75,0.67, 2,Culvert #1  , 0
      12      12    32.5    32.5
Culvert=2,4,12,18,0.013,0.3,0.5,10,1,-0.7,23,-0.7,23,Culvert #2  , 0

Type RM Length L Ch R =1,1380    ,560,560,560,0,0,0
Node Desc=CHANNEL
#Sta/Elev= 8
       0    5.75      10       5      12     4.1      15     -.7    30.6     -.7
    33.6     4.1      35       5      45    5.75
#Mann=3,0
       0      .1       0       0     .07       0      45      .1       0
Bank Sta=0,45
Exp/Cntr=0.3,0.1

Type RM Length L Ch R =1,820     ,470,470,470,0,0,0
Node Desc=CHANNEL
#Sta/Elev= 10
       0     5.5      20    3.99      21    -1.5      30    -4.8      40    -5.2
      50    -5.4      60    -3.9    64.8    -2.2    65.8     3.3    85.8     6.6
#Mann=3,0
       0      .1       0       0     .07       0    85.8      .1       0
Bank Sta=0,85.8
Exp/Cntr=0.3,0.1

Type RM Length L Ch R =1,350     ,350,350,350,0,0,0
Node Desc=CHANNEL
#Sta/Elev= 8
       0     3.3       1    -1.8      10    -4.5      20      -6      30    -4.8
      40    -1.5      46     .98      59     5.5
#Mann=3,0
       0      .1       0       0     .07       0      59      .1       0
Bank Sta=0,59
Exp/Cntr=0.3,0.1

Type RM Length L Ch R =1,0       ,0,0,0,0,0,0
Node Desc=CHANNEL
#Sta/Elev= 8
       0     3.3       1    -1.8      10    -4.5      20      -6      30    -4.8
      40    -1.5      46     .98      59     5.5
#Mann=3,0
       0      .1       0       0     .07       0      59      .1       0
Bank Sta=0,59
Exp/Cntr=0.3,0.1