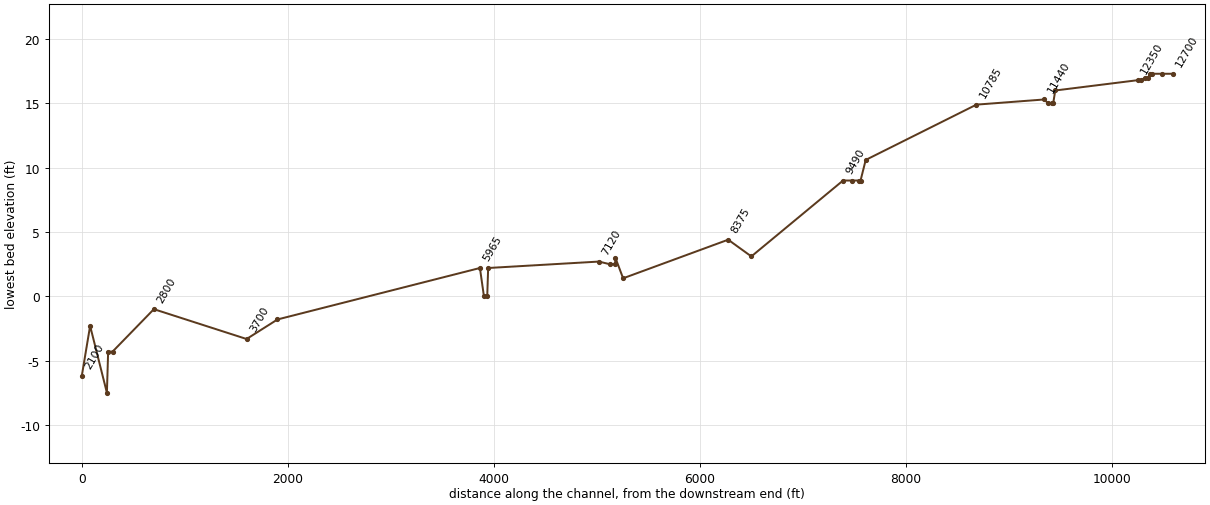
--- owlpr96.prj (project) ---

Proj Title=Owl Creek 1996 Proposed Conditions
Current Plan=p01
Default Exp/Contr=0.3,0.1
English Units
Geom File=g01
Geom File=g02
Flow File=f01
Plan File=p01
Plan File=p02

--- owlpr96.p01 (plan) ---

Plan Title=Owl Proposed 96
Short Identifier=Owl Prop. 96
Geom File=g01
Flow File=f01
Multiple Comp Mode
Subcritical Flow
K Sum by GR= 0
Std Step Tol= .01
Critical Tol= .01
Num of Std Step Trials= 20
Max Error Tol= .3
Flow Tol Ratio= .001
Log Output Level= 0
Friction Slope Method= 0
Multiple Critical Depth

--- owlpr96.f01 (steady flow) ---

Flow Title=Owl Creek 96
Number of Flows and Profiles and Boundary= 8, 4, 1
Rch & RM=1           ,12700
      18      44     140     184
Rch & RM=1           ,11483
      18      44     140     184
Rch & RM=1           ,10785
      19      47     150     197
Rch & RM=1           ,9578
      19      47     150     197
Rch & RM=1           ,9490
      21      53     171     224
Rch & RM=1           ,7223
      21      53     171     224
Rch & RM=1           ,7120
      23      57     183     240
Rch & RM=1           ,2100
      23      57     183     240
Boundary for Rch & Prof#=1           , 1
Up Type= 32767
Up Value=0
Dn Type= 1
Dn Value=2.5
Boundary for Rch & Prof#=1           , 2
Up Type= 32767
Up Value=0
Dn Type= 1
Dn Value=2.51
Boundary for Rch & Prof#=1           , 3
Up Type= 32767
Up Value=0
Dn Type= 1
Dn Value=2.7
Boundary for Rch & Prof#=1           , 4
Up Type= 32767
Up Value=0
Dn Type= 1
Dn Value=2.98

--- owlpr96.g01 (geometry) ---

Geom Title=Owl Creek Proposed 1996
ViewRect= 0, 1, 1, 0
Reach=1
Rch X Y Up & X Y Dn=0.5,0.9,0.5,0.1
Rch Arrow X Y Up & X Y Dn=0,0,0,0
Rch Type=0

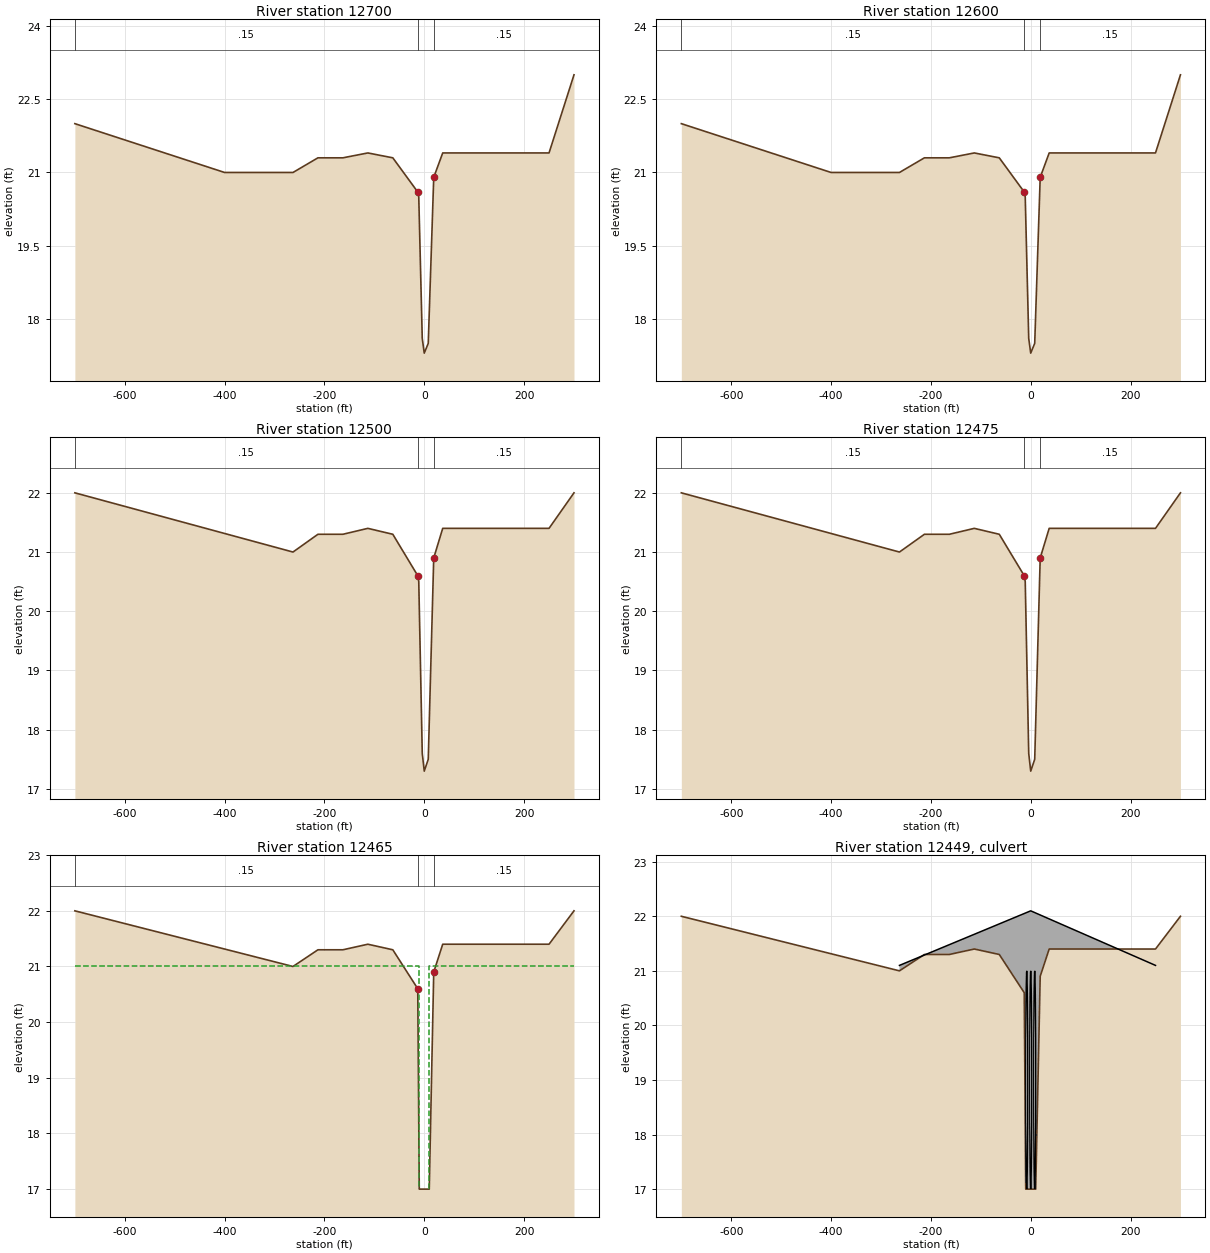
Type RM Length L Ch R =1,12700   ,100,100,100,0,0,0
Node Desc=JEI X-SEC.
#Sta/Elev= 16
    -700      22    -400      21    -263      21    -213    21.3    -163    21.3
    -113    21.4     -63    21.3     -13    20.6     -11    20.5      -4    17.6
       0    17.3       8    17.5      19    20.9      37    21.4     250    21.4
     300      23
#Mann=3,0
    -700     .15       0     -13     .07       0      19     .15       0
Bank Sta=-13,19
Exp/Cntr=0.3,0.1

Type RM Length L Ch R =1,12600   ,100,100,100,0,0,0
Node Desc=JEI X-SEC.
#Sta/Elev= 16
    -700      22    -400      21    -263      21    -213    21.3    -163    21.3
    -113    21.4     -63    21.3     -13    20.6     -11    20.5      -4    17.6
       0    17.3       8    17.5      19    20.9      37    21.4     250    21.4
     300      23
#Mann=3,0
    -700     .15       0     -13     .07       0      19     .15       0
Bank Sta=-13,19
Exp/Cntr=0.3,0.1

Type RM Length L Ch R =1,12500   ,25,25,25,0,0,0
Node Desc=JEI X-SEC.
#Sta/Elev= 15
    -700      22    -263      21    -213    21.3    -163    21.3    -113    21.4
     -63    21.3     -13    20.6     -11    20.5      -4    17.6       0    17.3
       8    17.5      19    20.9      37    21.4     250    21.4     300      22
#Mann=3,0
    -700     .15       0     -13     .07       0      19     .15       0
Bank Sta=-13,19
Exp/Cntr=0.3,0.1

Type RM Length L Ch R =1,12475   ,10,10,10,0,0,0
Node Desc=JEI X-SEC.
#Sta/Elev= 15
    -700      22    -263      21    -213    21.3    -163    21.3    -113    21.4
     -63    21.3     -13    20.6     -11    20.5      -4    17.6       0    17.3
       8    17.5      19    20.9      37    21.4     250    21.4     300      22
#Mann=3,0
    -700     .15       0     -13     .07       0      19     .15       0
Bank Sta=-13,19
Exp/Cntr=0.3,0.1

Type RM Length L Ch R =1,12465   ,32,32,32,0,0,0
Node Desc=JEI X-SEC.
#Sta/Elev= 15
    -700      22    -263      21    -213    21.3    -163    21.3    -113    21.4
     -63    21.3     -13    20.6     -10      17      -4      17       0      17
      10      17      19    20.9      37    21.4     250    21.4     300      22
#Mann=3,0
    -700     .15       0     -13     .07       0      19     .15       0
#XS Ineff= 2 , 0
             -10      21      10              21
Bank Sta=-13,19
Exp/Cntr=0.3,0.1

Type RM Length L Ch R =2,12449   ,,,,0,0,0
Node Desc=DRIVEWAY - JEI 1996 - Prop.Triple 48" RCP
Bridge Culvert--1,0,-1,-1
Deck Dist Width WeirC Skew NumUp NumDn MinLoCord MaxHiCord MaxSubmerge Is_Ogee
0,15,2.6,,3,3,21.1,,0.95,0
    -263       0     250
    21.1    22.1    21.1
       0       0       0
    -271       0     229
    21.2    22.1    22.1
       0       0       0
BR Coef= 1,-1,-1,, 0,,,,-1,,0,
Culvert=1,4,,32,0.012,0.5,1,1,1,17,-8,17,-8,Culvert #1  , 0
Culvert=1,4,,32,0.012,0.5,1,1,1,17,0,17,0,Culvert #2  , 0
Culvert=1,4,,32,0.012,0.5,1,1,1,17,8,17,8,Culvert #3  , 0

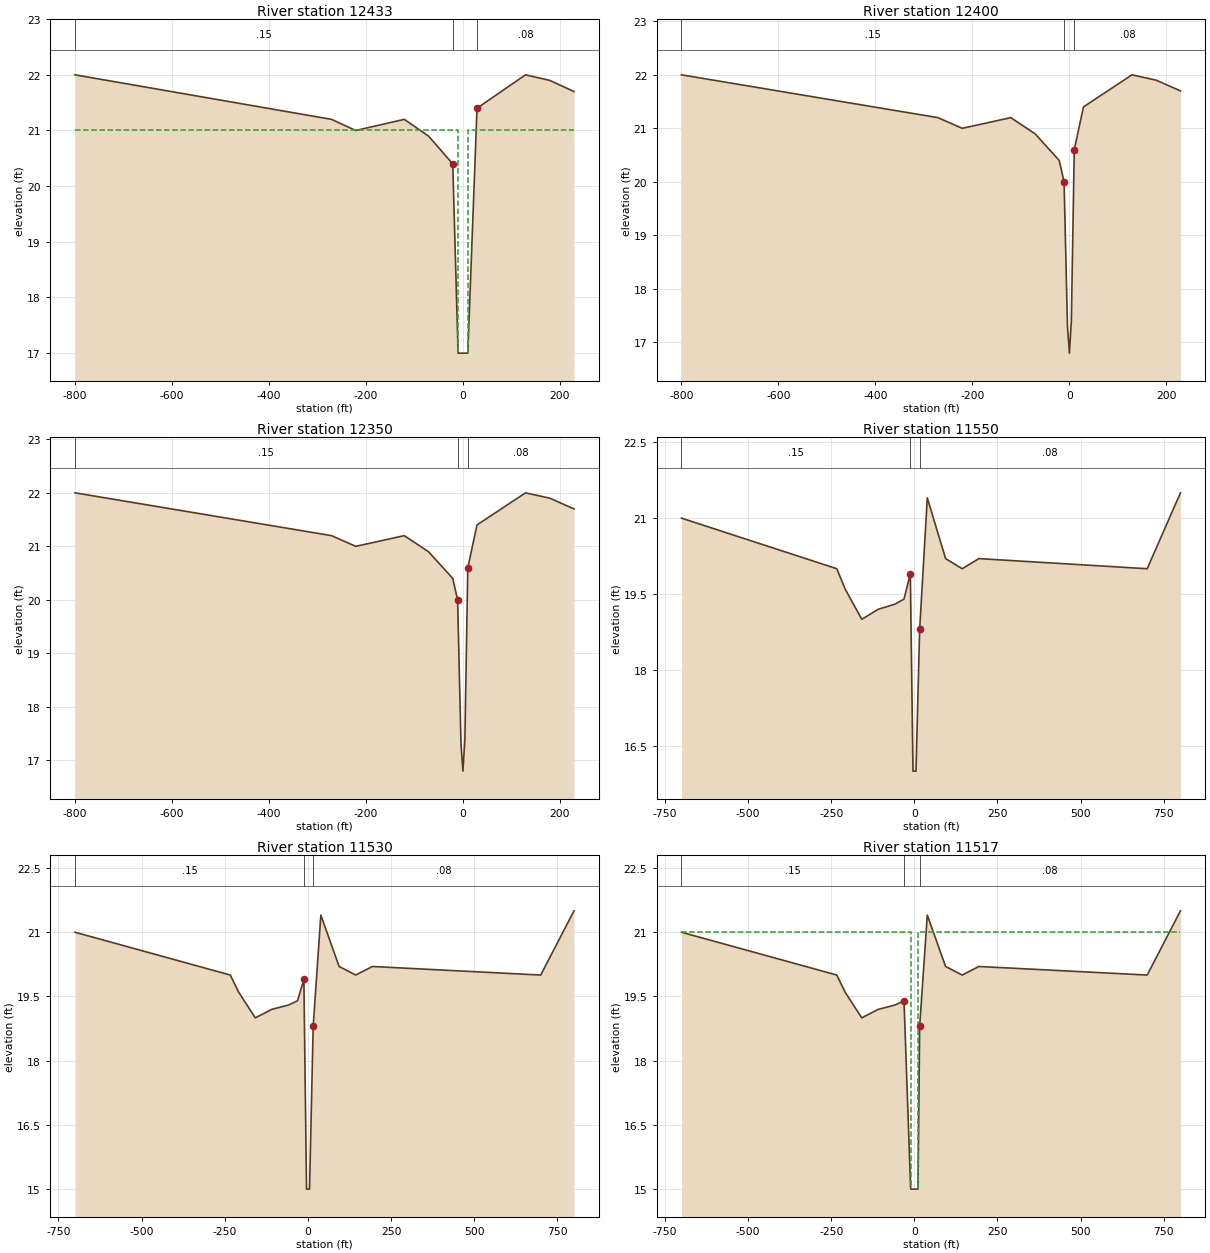
Type RM Length L Ch R =1,12433   ,40,40,40,0,0,0
Node Desc=JEI X-SEC.
#Sta/Elev= 17
    -800      22    -271    21.2    -221      21    -171    21.1    -121    21.2
     -71    20.9     -21    20.4     -10      17      -4      17       0      17
       4      17      10      17      29    21.4      79    21.7     129      22
     179    21.9     229    21.7
#Mann=3,0
    -800     .15       0     -21     .07       0      29     .08       0
#XS Ineff= 2 , 0
             -10      21      10              21
Bank Sta=-21,29
Exp/Cntr=0.3,0.1

Type RM Length L Ch R =1,12400   ,33,33,33,0,0,0
Node Desc=JEI X-SEC.
#Sta/Elev= 17
    -800      22    -271    21.2    -221      21    -171    21.1    -121    21.2
     -71    20.9     -21    20.4     -11      20      -4    17.3       0    16.8
       4    17.4      10    20.6      29    21.4      79    21.7     129      22
     179    21.9     229    21.7
#Mann=3,0
    -800     .15       0     -11     .07       0      10     .08       0
Bank Sta=-11,10
Exp/Cntr=0.3,0.1

Type RM Length L Ch R =1,12350   ,800,800,800,0,0,0
Node Desc=JEI X-SEC.
#Sta/Elev= 17
    -800      22    -271    21.2    -221      21    -171    21.1    -121    21.2
     -71    20.9     -21    20.4     -11      20      -4    17.3       0    16.8
       4    17.4      10    20.6      29    21.4      79    21.7     129      22
     179    21.9     229    21.7
#Mann=3,0
    -800     .15       0     -11     .07       0      10     .08       0
Bank Sta=-11,10
Exp/Cntr=0.3,0.1

Type RM Length L Ch R =1,11550   ,20,20,20,0,0,0
Node Desc=JEI X-SEC.
#Sta/Elev= 18
    -700      21    -233      20    -208    19.6    -158      19    -108    19.2
     -58    19.3     -31    19.4     -12    19.9      -4      16       0      16
       5      16      16    18.8      39    21.4      94    20.2     144      20
     194    20.2     700      20     800    21.5
#Mann=3,0
    -700     .15       0     -12     .07       0      16     .08       0
Bank Sta=-12,16
Exp/Cntr=0.3,0.1

Type RM Length L Ch R =1,11530   ,13,13,13,0,0,0
Node Desc=JEI X-SEC.
#Sta/Elev= 18
    -700      21    -233      20    -208    19.6    -158      19    -108    19.2
     -58    19.3     -31    19.4     -12    19.9      -4      15       0      15
       5      15      16    18.8      39    21.4      94    20.2     144      20
     194    20.2     700      20     800    21.5
#Mann=3,0
    -700     .15       0     -12     .07       0      16     .08       0
Bank Sta=-12,16
Exp/Cntr=0.3,0.1

Type RM Length L Ch R =1,11517   ,34,34,34,0,0,0
Node Desc=JEI X-SEC.
#Sta/Elev= 18
    -700      21    -233      20    -208    19.6    -158      19    -108    19.2
     -58    19.3     -31    19.4     -11      15      -4      15       0      15
      11      15      16    18.8      39    21.4      94    20.2     144      20
     194    20.2     700      20     800    21.5
#Mann=3,0
    -700     .15       0     -31     .07       0      16     .08       0
#XS Ineff= 2 , 0
             -11      21      11              21
Bank Sta=-31,16
Exp/Cntr=0.3,0.1

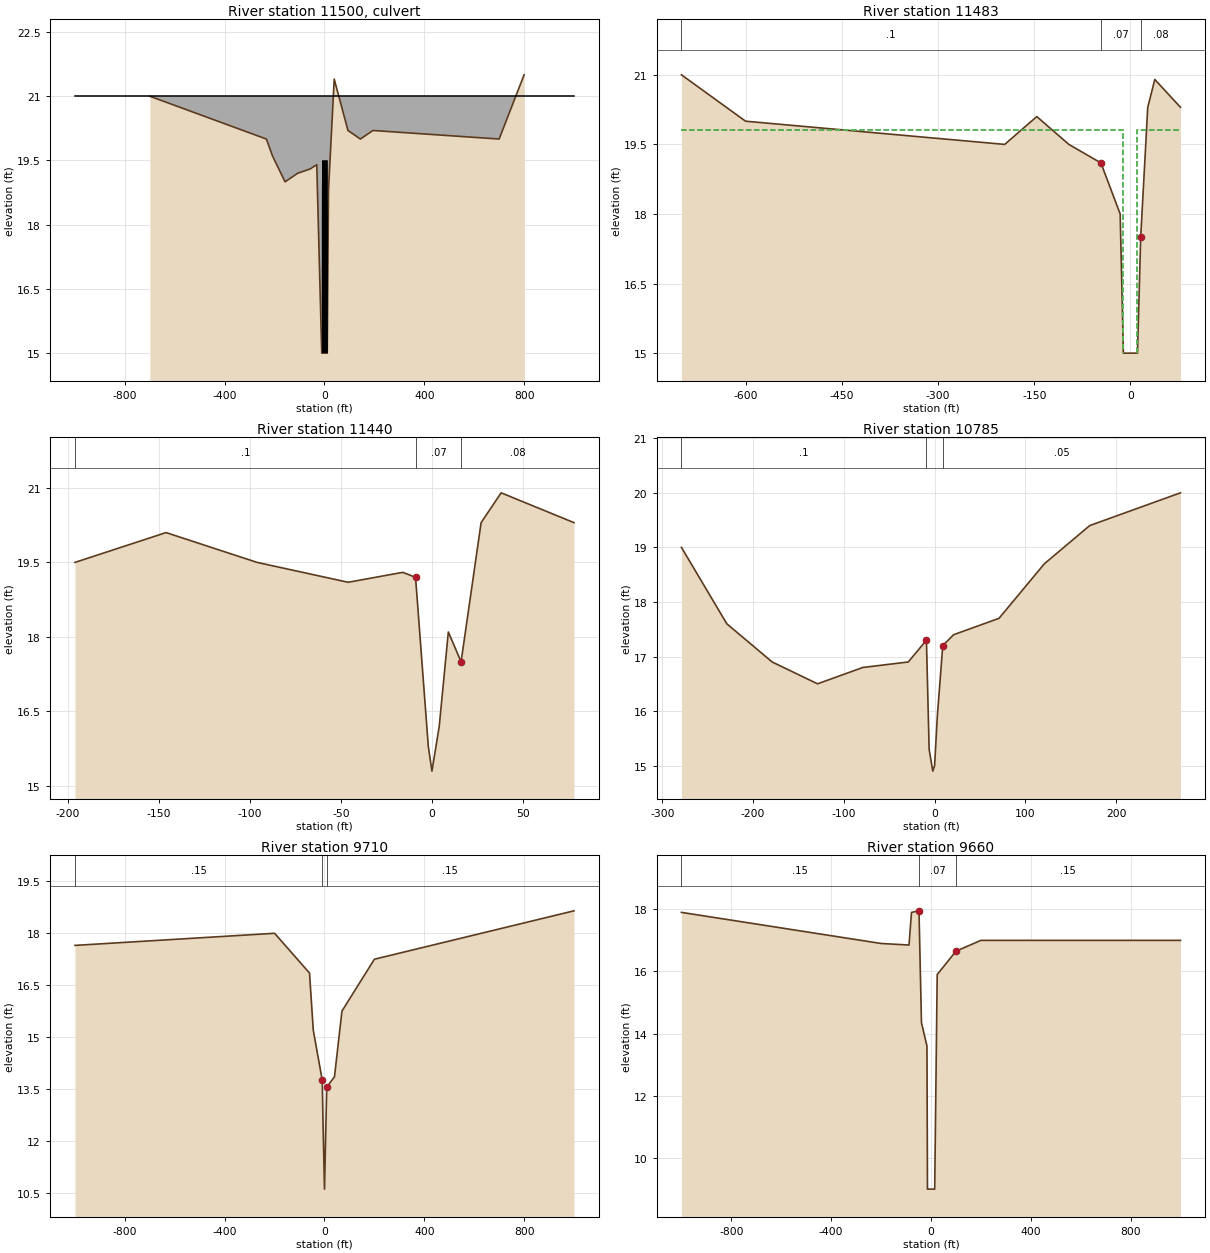
Type RM Length L Ch R =2,11500   ,,,,0,0,0
Node Desc=SHIRLEY LN. - JEI 1996 - Prop. Dbl. 54" RCP
Bridge Culvert--1,0,-1,-1
Deck Dist Width WeirC Skew NumUp NumDn MinLoCord MaxHiCord MaxSubmerge Is_Ogee
0,25,2.6,,4,3,,,0.95,0
   -1000    -233     194    1000
      21      21      21      21
       0       0       0       0
   -1000    -196      78
      21      21      21
       0       0       0
Multiple Barrel Culv=1,4.5,,34,0.012,0.5,1,1,1,15,15, 3,Culvert #1  , 0
      -6      -6       2       2       9       9

Type RM Length L Ch R =1,11483   ,43,43,43,0,0,0
Node Desc=JEI X-SEC.
#Sta/Elev= 16
    -700      21    -600      20    -196    19.5    -146    20.1     -96    19.5
     -46    19.1     -16      18     -11      15      -4      15       0      15
       4      15      11      15      16    17.5      27    20.3      38    20.9
      78    20.3
#Mann=3,0
    -700      .1       0     -46     .07       0      16     .08       0
#XS Ineff= 2 , 0
             -11    19.8      11            19.8
Bank Sta=-46,16
Exp/Cntr=0.3,0.1

Type RM Length L Ch R =1,11440   ,655,655,655,0,0,0
Node Desc=JEI X-SEC.
#Sta/Elev= 14
    -196    19.5    -146    20.1     -96    19.5     -46    19.1     -16    19.3
      -9    19.2      -2    15.8       0    15.3       4    16.2       9    18.1
      16    17.5      27    20.3      38    20.9      78    20.3
#Mann=3,0
    -196      .1       0      -9     .07       0      16     .08       0
Bank Sta=-9,16
Exp/Cntr=0.3,0.1

Type RM Length L Ch R =1,10785   ,1075,1075,1075,0,0,0
Node Desc=JEI X-SEC.
#Sta/Elev= 18
    -279      19    -229    17.6    -179    16.9    -129    16.5     -79    16.8
     -29    16.9      -9    17.3      -6    15.3      -2    14.9       0      15
       3    15.9       9    17.2      21    17.4      71    17.7     121    18.7
     171    19.4     221    19.7     271      20
#Mann=3,0
    -279      .1       0      -9     .07       0       9     .05       0
#XS Ineff= 2 , 0
              -9    17.3       9            17.2
Bank Sta=-9,9
Exp/Cntr=0.3,0.1

Type RM Length L Ch R =1,9710    ,140,50,1,0,0,0
Node Desc= SCS 228
#Sta/Elev= 13
   -1000   17.65    -200      18     -60   16.85     -45    15.2      -9   13.75
      -6   12.55       0    10.6       6   12.55       9   13.55      40   13.85
      70   15.75     200   17.25    1000   18.65
#Mann=3,0
   -1000     .15       0      -9     .07       0       9     .15       0
Bank Sta=-9,9
Exp/Cntr=0.3,0.1

Type RM Length L Ch R =1,9660    ,18,18,18,0,0,0
Node Desc= SCS 226
#Sta/Elev= 14
   -1000    17.9    -200    16.9     -88   16.85     -78    17.9     -48   17.95
     -38   14.35     -16    13.6     -14       9       0       9      15       9
      25    15.9     100   16.65     200      17    1000      17
#Mann=3,0
   -1000     .15       0     -48     .07       0     100     .15       0
Bank Sta=-48,100
Exp/Cntr=0.3,0.1

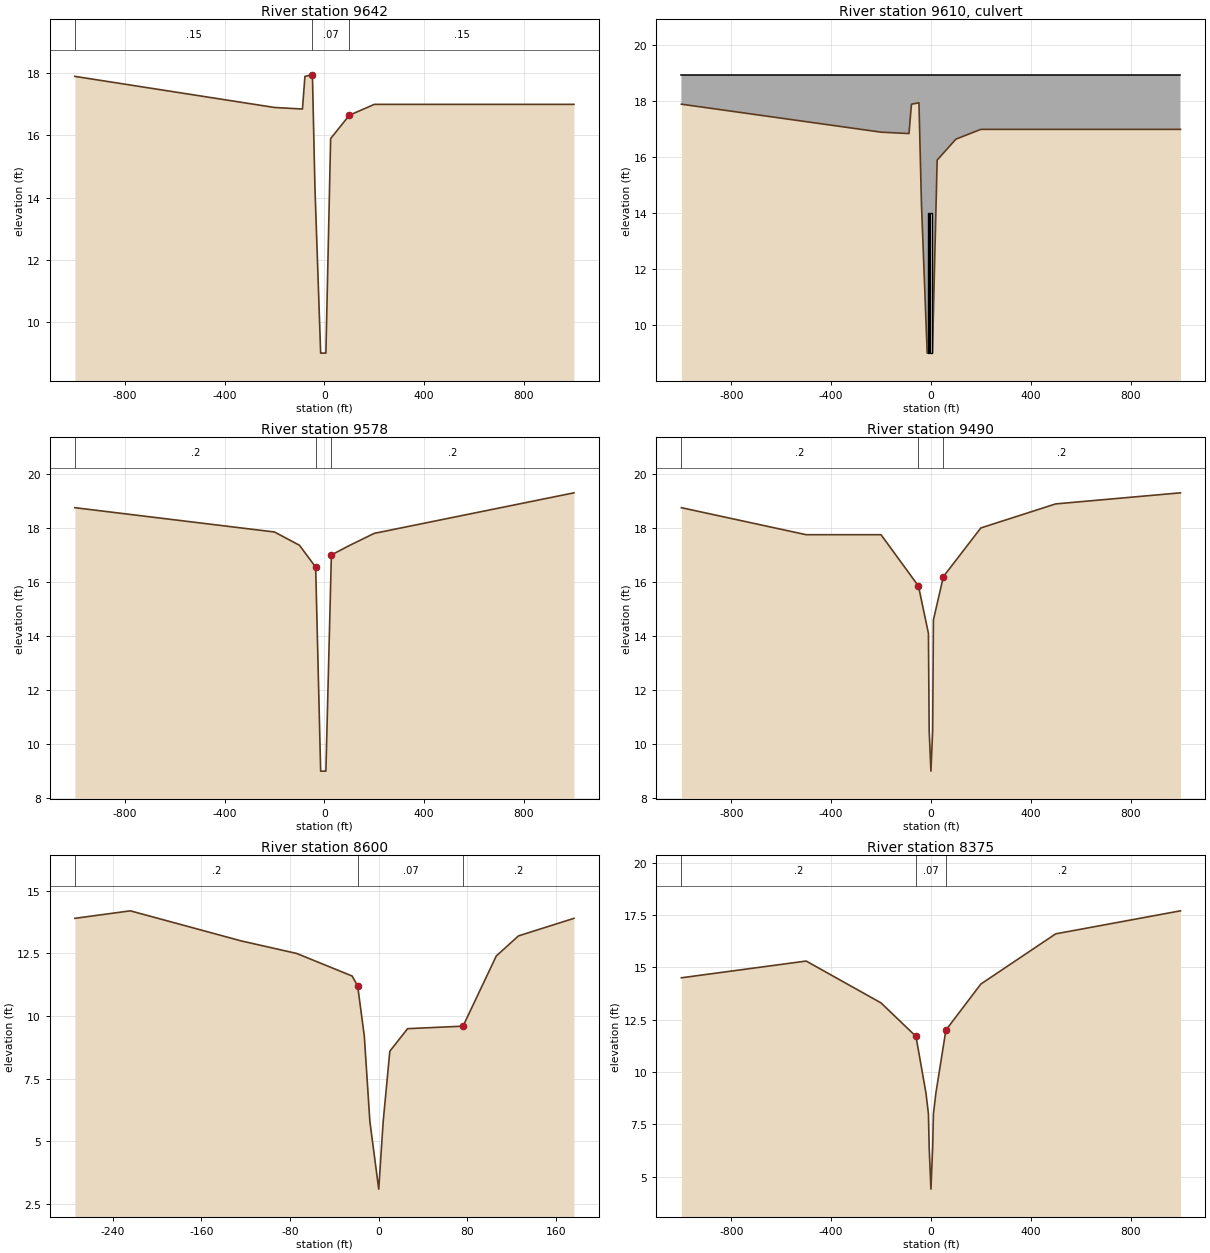
Type RM Length L Ch R =1,9642    ,64,64,64,0,0,0
Node Desc= SCS 226
#Sta/Elev= 14
   -1000    17.9    -200    16.9     -88   16.85     -78    17.9     -48   17.95
     -38   14.35     -15       9   -12.5       9       0       9       6       9
      25    15.9     100   16.65     200      17    1000      17
#Mann=3,0
   -1000     .15       0     -48     .07       0     100     .15       0
Bank Sta=-48,100
Exp/Cntr=0.3,0.1

Type RM Length L Ch R =2,9610    ,,,,0,0,0
Node Desc=SR 31 Prop. Double 5' x 6'
Bridge Culvert--1,0,-1,-1
Deck Dist Width WeirC Skew NumUp NumDn MinLoCord MaxHiCord MaxSubmerge Is_Ogee
0,45,2.7,,2,2,,,0.95,0
   -1000    1000
   18.95   18.95
     1.8     1.8
   -1000    1000
   18.95   18.95
     1.8     1.8
BR Coef= 1, 0, 0,, 0,,,0.8,0,0,0,
Multiple Barrel Culv=2,5,6,64,0.012,0.5,1,10,1,9,9, 2,Culvert # 1 , 0
     -10     -10       0       0

Type RM Length L Ch R =1,9578    ,88,88,88,0,0,0
Node Desc= SCS 222
#Sta/Elev= 11
   -1000   18.75    -200   17.85    -100   17.36     -35   16.55     -15       9
       0       9       6       9      28      17     100   17.35     200    17.8
    1000    19.3
#Mann=3,0
   -1000      .2       0     -35     .07       0      28      .2       0
Bank Sta=-35,28
Exp/Cntr=0.3,0.1

Type RM Length L Ch R =1,9490    ,890,890,890,0,0,0
Node Desc= SCS 220
#Sta/Elev= 13
   -1000   18.75    -500   17.75    -200   17.75     -50   15.85     -10    14.1
      -7    10.5       0       9       7    10.5      10    14.6      50    16.2
     200      18     500   18.89    1000    19.3
#Mann=3,0
   -1000      .2       0     -50     .07       0      50      .2       0
Bank Sta=-50,50
Exp/Cntr=0.3,0.1

Type RM Length L Ch R =1,8600    ,225,225,225,0,0,0
Node Desc=JEI X-SEC.
#Sta/Elev= 17
    -274    13.9    -224    14.2    -174    13.6    -124      13     -74    12.5
     -24    11.6     -19    11.2     -13     9.2      -8     5.8       0     3.1
       4     5.8      10     8.6      26     9.5      76     9.6     106    12.4
     126    13.2     176    13.9
#Mann=3,0
    -274      .2       0     -19     .07       0      76      .2       0
Bank Sta=-19,76
Exp/Cntr=0.3,0.1

Type RM Length L Ch R =1,8375    ,1020,1020,1020,0,0,0
Node Desc= SCS 218
#Sta/Elev= 15
   -1000    14.5    -500    15.3    -200    13.3     -60    11.7     -20       9
     -10       8      -7     6.4       0     4.4       7     6.4      10       8
      20       9      60      12     200    14.2     500    16.6    1000    17.7
#Mann=3,0
   -1000      .2       0     -60     .07       0      60      .2       0
Bank Sta=-60,60
Exp/Cntr=0.3,0.1

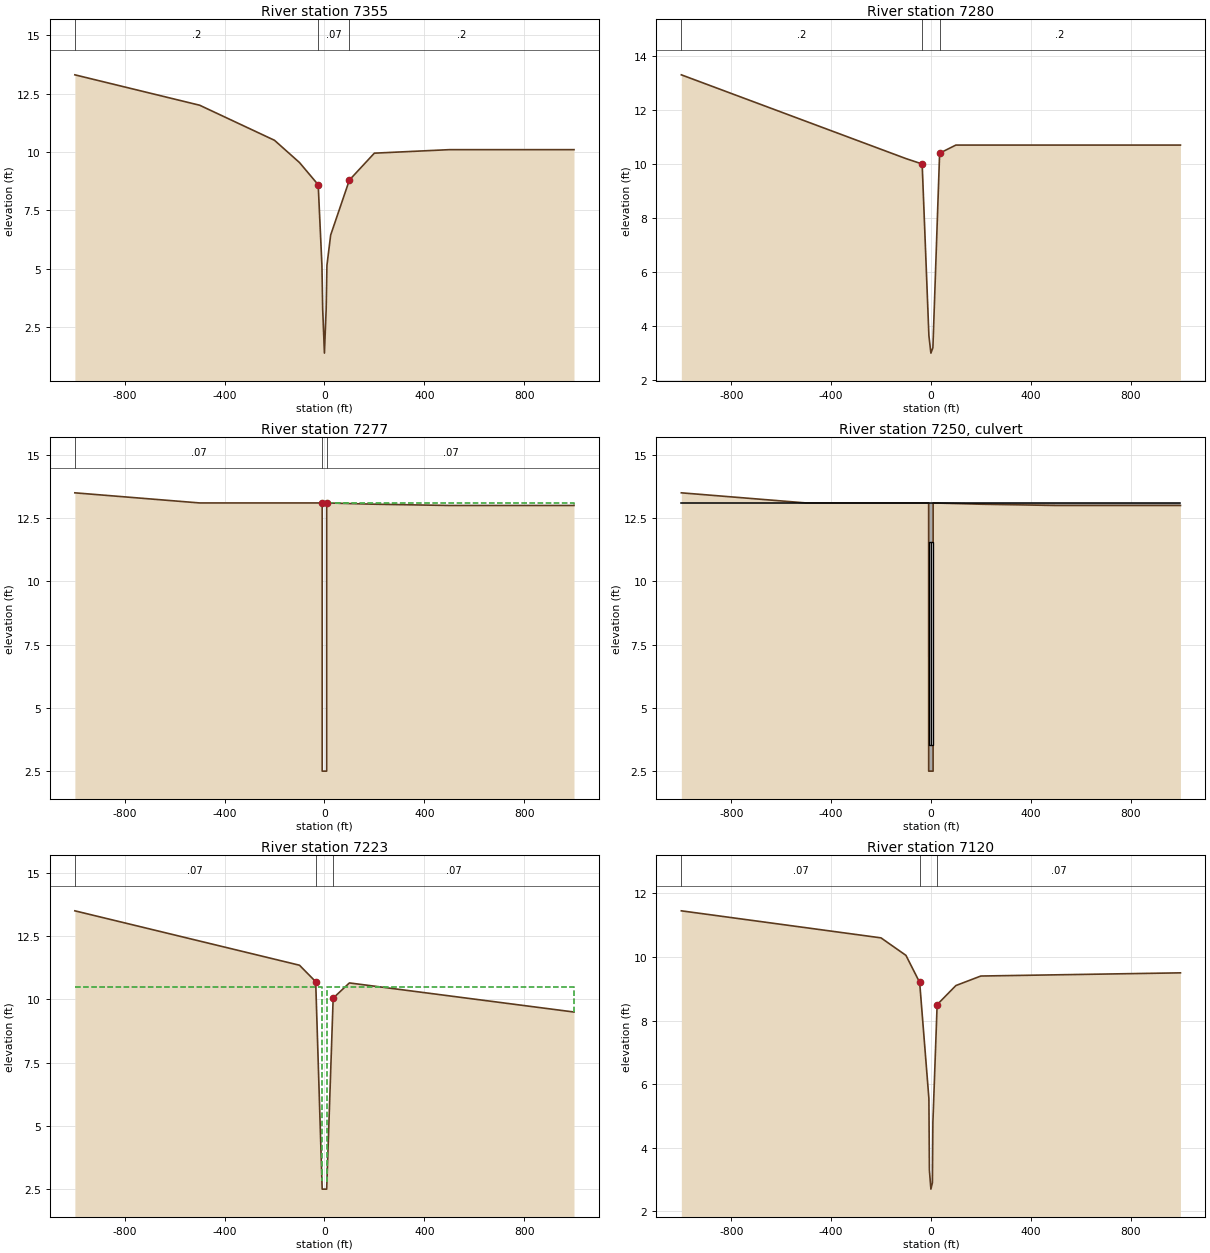
Type RM Length L Ch R =1,7355    ,75,75,75,0,0,0
Node Desc= SCS 216
#Sta/Elev= 15
   -1000    13.3    -500      12    -200    10.5    -100    9.55     -25     8.6
     -10    5.15      -7     3.3       0     1.4       7     3.3      10    5.15
      25    6.45     100     8.8     200    9.95     500    10.1    1000    10.1
#Mann=3,0
   -1000      .2       0     -25     .07       0     100      .2       0
Bank Sta=-25,100
Exp/Cntr=0.3,0.1

Type RM Length L Ch R =1,7280    ,3,3,3,0,0,0
Node Desc= SCS 214
#Sta/Elev= 9
   -1000    13.3    -100    10.2     -35      10      -8    3.65       0       3
       8     3.2      35    10.4     100    10.7    1000    10.7
#Mann=3,0
   -1000      .2       0     -35     .07       0      35      .2       0
Bank Sta=-35,35
Exp/Cntr=0.3,0.1

Type RM Length L Ch R =1,7277    ,54,54,54,0,0,0
Node Desc= SCS 212
#Sta/Elev= 10
   -1000    13.5    -500    13.1    -200    13.1      -9    13.1    -8.9     2.5
     8.9     2.5       9    13.1     200   13.05     500      13    1000      13
#Mann=3,0
   -1000     .07       0      -9     .07       0       9     .07       0
#XS Ineff= 2 , 0
             -10    13.1      10            13.1
Bank Sta=-9,9
Exp/Cntr=0.3,0.1

Type RM Length L Ch R =2,7250    ,,,,0,0,0
Node Desc=CR 78 ( 2  8' x  8' Boxes)  SCS 211
Bridge Culvert--1,0,-1,-1
Deck Dist Width WeirC Skew NumUp NumDn MinLoCord MaxHiCord MaxSubmerge Is_Ogee
0,54,2.7,,2,2,13.1,,0.95,0
   -1000    1000
    13.1    13.1
       0       0
   -1000    1000
    13.1    13.1
       0       0
Multiple Barrel Culv=2,8,8,54,0.012,0.2,0.5,10,2,3.55,2.5, 2,Culvert # 1 , 0
      -5      -5       5       5

Type RM Length L Ch R =1,7223    ,103,103,103,0,0,0
Node Desc= SCS 210
#Sta/Elev= 9
   -1000    13.5    -100   11.35     -35    10.7      -9     2.5       0     2.5
       9     2.5      35   10.05     100   10.65    1000     9.5
#Mann=3,0
   -1000     .07       0     -35     .07       0      35     .07       0
#XS Ineff= 2 , 0
             -10    10.5      10            10.5
Bank Sta=-35,35
Exp/Cntr=0.3,0.1

Type RM Length L Ch R =1,7120    ,1075,1075,1075,0,0,0
Node Desc= SCS 208
#Sta/Elev= 13
   -1000   11.45    -200    10.6    -100   10.05     -45     9.2      -8    5.55
      -6     3.3       0     2.7       6     2.9       8     4.8      25     8.5
     100     9.1     200     9.4    1000     9.5
#Mann=3,0
   -1000     .07       0     -45     .07       0      25     .07       0
Bank Sta=-45,25
Exp/Cntr=0.3,0.1

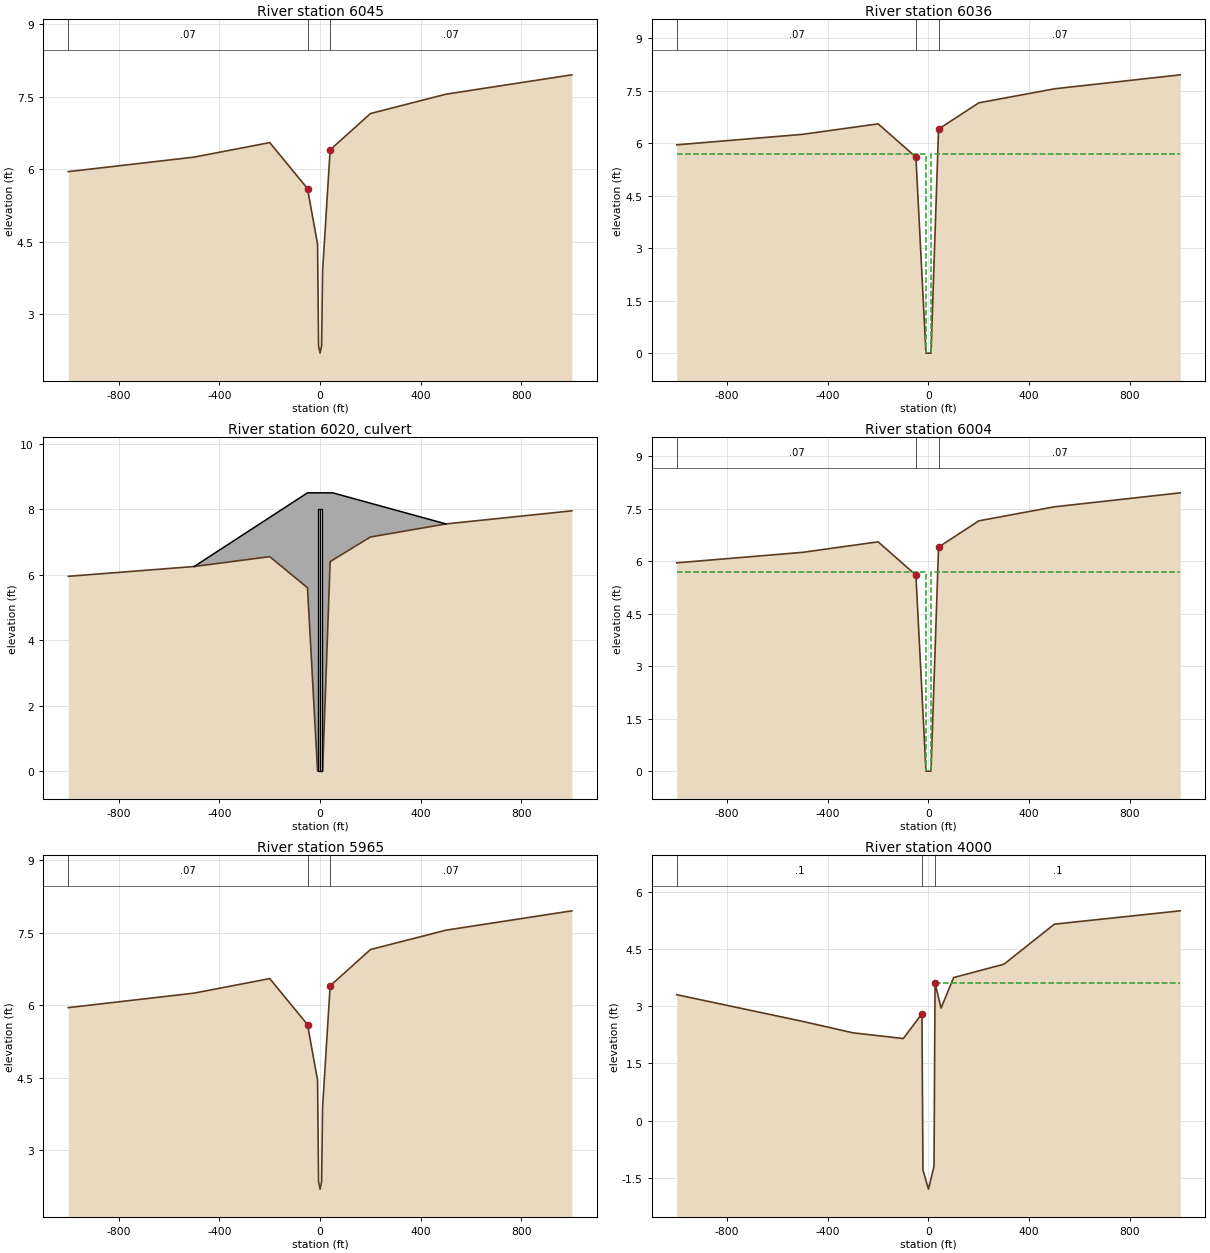
Type RM Length L Ch R =1,6045    ,9,9,9,0,0,0
Node Desc= SCS 206
#Sta/Elev= 13
   -1000    5.95    -500    6.25    -200    6.55     -50     5.6     -10    4.45
      -6    2.35       0     2.2       6    2.35      10     3.9      40     6.4
     200    7.15     500    7.55    1000    7.95
#Mann=3,0
   -1000     .07       0     -50     .07       0      40     .07       0
Bank Sta=-50,40
Exp/Cntr=0.3,0.1

Type RM Length L Ch R =1,6036    ,32,32,32,0,0,0
Node Desc= SCS 206
#Sta/Elev= 13
   -1000    5.95    -500    6.25    -200    6.55     -50     5.6     -10       0
      -6       0       0       0       6       0      10       0      40     6.4
     200    7.15     500    7.55    1000    7.95
#Mann=3,0
   -1000     .07       0     -50     .07       0      40     .07       0
#XS Ineff= 2 , 0
              -9     5.7       9             5.7
Bank Sta=-50,40
Exp/Cntr=0.3,0.1

Type RM Length L Ch R =2,6020    ,,,,0,0,0
Node Desc=Greenwell D/W Prop. Dbl. 8 x 8
Bridge Culvert--1,0,-1,-1
Deck Dist Width WeirC Skew NumUp NumDn MinLoCord MaxHiCord MaxSubmerge Is_Ogee
0,21,2.6,,4,4,,,0.95,0
    -500     -50      50     500
    6.25     8.5     8.5    7.55
    6.25       0       0    7.55
    -500     -50      50     500
    6.25     8.5     8.5    7.55
    6.25       0       0    7.55
Multiple Barrel Culv=2,8,8,32,0.012,0.5,1,10,1,0,0, 2,Culvert #1  , 0
      -5      -5       5       5

Type RM Length L Ch R =1,6004    ,39,39,39,0,0,0
Node Desc= SCS 206
#Sta/Elev= 13
   -1000    5.95    -500    6.25    -200    6.55     -50     5.6     -10       0
      -6       0       0       0       6       0      10       0      40     6.4
     200    7.15     500    7.55    1000    7.95
#Mann=3,0
   -1000     .07       0     -50     .07       0      40     .07       0
#XS Ineff= 2 , 0
              -9     5.7       9             5.7
Bank Sta=-50,40
Exp/Cntr=0.3,0.1

Type RM Length L Ch R =1,5965    ,1965,1965,1965,0,0,0
Node Desc= SCS 206
#Sta/Elev= 13
   -1000    5.95    -500    6.25    -200    6.55     -50     5.6     -10    4.45
      -6    2.35       0     2.2       6    2.35      10     3.9      40     6.4
     200    7.15     500    7.55    1000    7.95
#Mann=3,0
   -1000     .07       0     -50     .07       0      40     .07       0
Bank Sta=-50,40
Exp/Cntr=0.3,0.1

Type RM Length L Ch R =1,4000    ,300,300,300,0,0,0
Node Desc= SCS 204
#Sta/Elev= 14
   -1000     3.3    -500     2.6    -300     2.3    -100    2.15     -26     2.8
     -22    -1.3       0    -1.8      22    -1.2      26     3.6      50    2.95
     100    3.75     300     4.1     500    5.15    1000     5.5
#Mann=3,0
   -1000      .1       0     -26     .07       0      26      .1       0
#XS Ineff= 2 , 0
             -26     2.8      26             3.6
Bank Sta=-26,26
Exp/Cntr=0.3,0.1

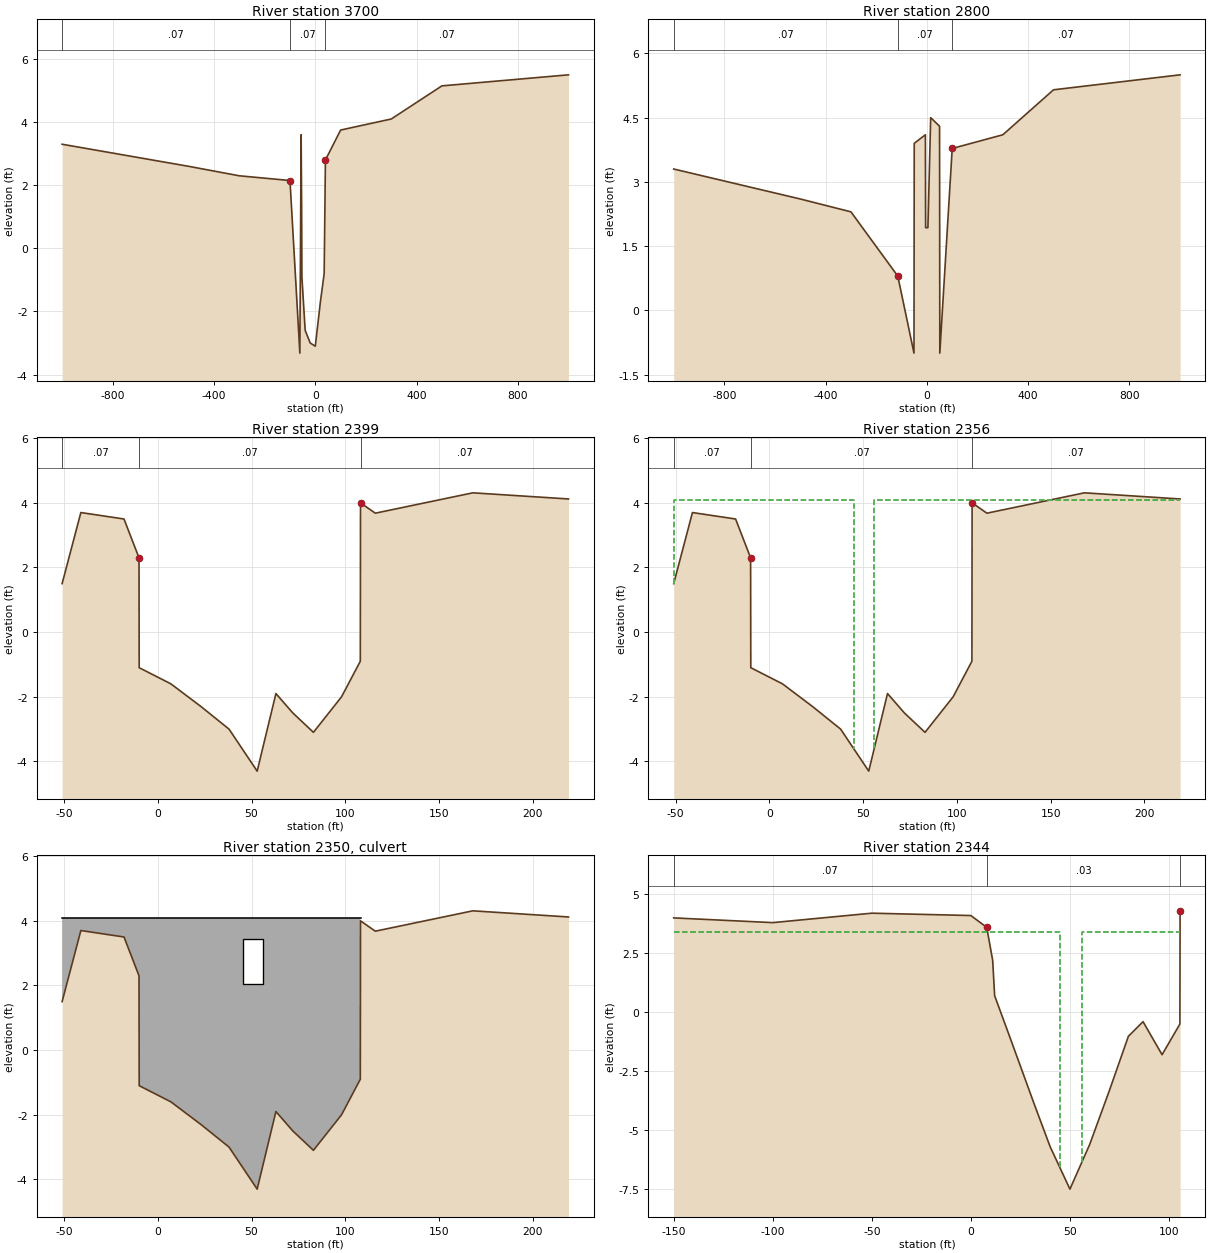
Type RM Length L Ch R =1,3700    ,900,900,900,0,0,0
Node Desc= SCS 203
#Sta/Elev= 18
   -1000     3.3    -500     2.6    -300     2.3    -100    2.15     -61   -3.32
     -56     3.6     -54     1.3     -53     -.9     -40    -2.6     -20      -3
       0    -3.1      20    -1.7      35     -.8      40     2.8     100    3.75
     300     4.1     500    5.15    1000     5.5
#Mann=3,0
   -1000     .07       0    -100     .07       0      40     .07       0
Bank Sta=-100,40
Exp/Cntr=0.3,0.1

Type RM Length L Ch R =1,2800    ,401,401,401,0,0,0
Node Desc= SCS 202
#Sta/Elev= 16
   -1000     3.3    -500     2.6    -300     2.3    -115      .8     -51      -1
     -50     3.9      -6     4.1      -5    1.93       4    1.93      15     4.5
      50     4.3      51      -1     100    3.78     300     4.1     500    5.15
    1000     5.5
#Mann=3,0
   -1000     .07       0    -115     .07       0     100     .07       0
Bank Sta=-115,100
Exp/Cntr=0.3,0.1

Type RM Length L Ch R =1,2399    ,43,43,43,0,0,0
Node Desc=JEI X-SEC.
#Sta/Elev= 18
     -51     1.5     -41     3.7     -18     3.5     -10     2.3    -9.9    -1.1
       7    -1.6      23    -2.3      38      -3      53    -4.3      63    -1.9
      72    -2.5      83    -3.1      98      -2     108     -.9   108.1       4
     116    3.68     168    4.31     219    4.12
#Mann=3,0
     -51     .07       0     -10     .07       0   108.1     .07       0
Bank Sta=-10,108.1
Exp/Cntr=0.3,0.1

Type RM Length L Ch R =1,2356    ,12,12,12,0,0,0
Node Desc=JEI X-SEC.
#Sta/Elev= 18
     -51     1.5     -41     3.7     -18     3.5     -10     2.3    -9.9    -1.1
       7    -1.6      23    -2.3      38      -3      53    -4.3      63    -1.9
      72    -2.5      83    -3.1      98      -2     108     -.9   108.1       4
     116    3.68     168    4.31     219    4.12
#Mann=3,0
     -51     .07       0     -10     .07       0   108.1     .07       0
#XS Ineff= 2 , 0
              45     4.1      56             4.1
Bank Sta=-10,108.1
Exp/Cntr=0.3,0.1

Type RM Length L Ch R =2,2350    ,,,,0,0,0
Node Desc=Spillway @ confl. w/Trout Creek
Bridge Culvert--1,0,-1,-1
Deck Dist Width WeirC Skew NumUp NumDn MinLoCord MaxHiCord MaxSubmerge Is_Ogee
0,12,2.6,,4,4,,,0.95,0
     -51     -40       0   108.1
     4.1     4.1     4.1     4.1
       0       0      -8      -8
     -51     -40       0   108.1
     4.1     4.1     4.1     4.1
       0       0      -8      -8
Culvert=2,1.4,10.7,12,0.018,0.3,0.5,8,1,2.04,51,1.95,51,Culvert #1  , 0

Type RM Length L Ch R =1,2344    ,163,163,163,0,0,0
Node Desc=JEI X-SEC.
#Sta/Elev= 18
    -150       4    -100     3.8     -50     4.2       0     4.1       8     3.6
      11     2.2      12      .7      19     -.9      32    -3.9      40    -5.7
      50    -7.5      60    -5.6      70    -3.3    79.5   -1.02    86.9     -.4
    96.5    -1.8   105.5     -.5   105.6     4.3
#Mann=3,0
    -150     .07       0       8     .03       0   105.6     .07       0
#XS Ineff= 2 , 0
              45     3.4      56             3.4
Bank Sta=8,105.6
Exp/Cntr=0.3,0.1

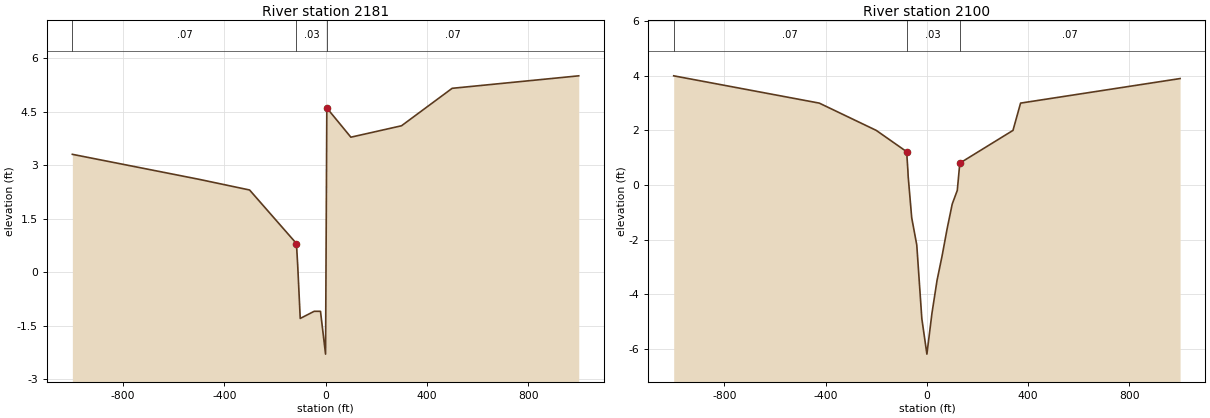
Type RM Length L Ch R =1,2181    ,81,81,81,0,0,0
Node Desc= SCS 201
#Sta/Elev= 14
   -1000     3.3    -500     2.6    -300     2.3    -115      .8    -110     .19
    -100    -1.3     -45    -1.1     -20    -1.1       0    -2.3       5     4.6
     100    3.78     300     4.1     500    5.15    1000     5.5
#Mann=3,0
   -1000     .07       0    -115     .03       0       5     .07       0
Bank Sta=-115,5
Exp/Cntr=0.3,0.1

Type RM Length L Ch R =1,2100    ,100,100,100,0,0,0
Node Desc= JEI 100
#Sta/Elev= 20
   -1000       4    -425       3    -200       2     -80    1.22     -75     .52
     -74     .32     -60    -1.2     -40    -2.2     -20    -4.9       0    -6.2
      20    -4.7      40    -3.5      60    -2.6      80    -1.6     100     -.7
     120     -.2     130      .8     340       2     370       3    1000     3.9
#Mann=3,0
   -1000     .07       0     -80     .03       0     130     .07       0
Bank Sta=-80,130
Exp/Cntr=0.3,0.1