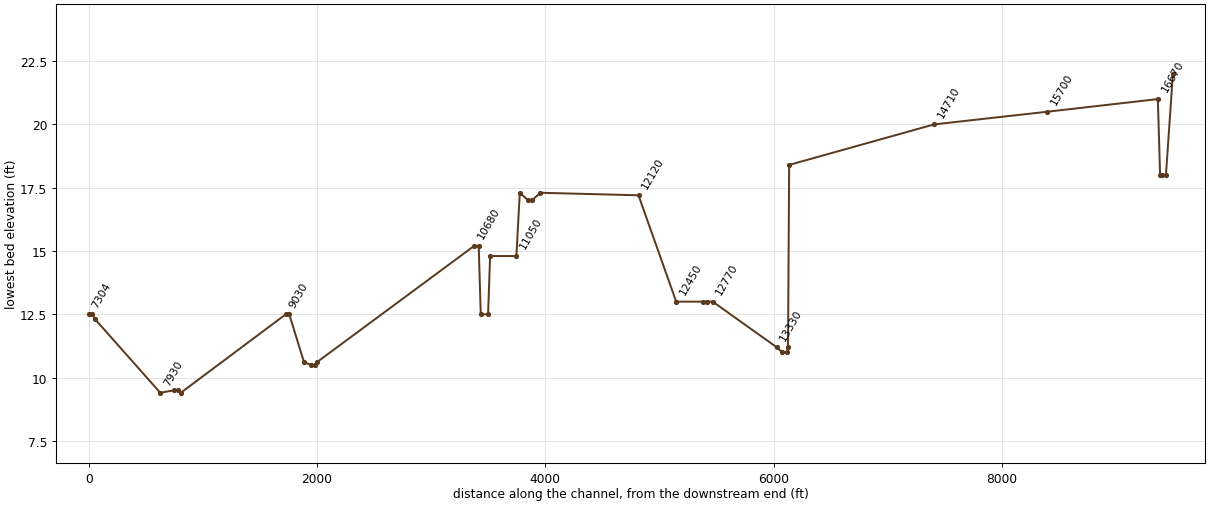
--- palmprop.prj (project) ---

Proj Title=Palm Creek Proposed Cond.  1996
Current Plan=p05
Default Exp/Contr=0.3,0.1
English Units
Geom File=g04
Geom File=g03
Geom File=g02
Geom File=g01
Flow File=f02
Flow File=f01
Plan File=p05
Plan File=p04
Plan File=p03
Plan File=p02
Plan File=p01

--- palmprop.p05 (plan) ---

Plan Title=Palm Creek Proposed Conditions 1996
Short Identifier=Palm Pr 96
Geom File=g04
Flow File=f02
Multiple Comp Mode
Subcritical Flow
K Sum by GR= 0
Std Step Tol= .01
Critical Tol= .01
Num of Std Step Trials= 20
Max Error Tol= .3
Flow Tol Ratio= .001
Log Output Level= 0
Friction Slope Method= 0
Multiple Critical Depth

--- palmprop.f02 (steady flow) ---

Flow Title=Palm Creek 1996 JEI Flows
Number of Flows and Profiles and Boundary= 11, 4, 2
Rch & RM=2           ,16770
       9      27      85     118
Rch & RM=2           ,13420
       9      27      85     118
Rch & RM=2           ,13380
      12      39     120     166
Rch & RM=2           ,10720
      12      39     120     166
Rch & RM=2           ,10680
      15      47     145     201
Rch & RM=2           ,6153
      15      47     145     201
Rch & RM=2           ,6110
      21      66     206     285
Rch & RM=1           ,3250
      21      66     206     285
Rch & RM=1           ,2313
      21      66     206     285
Rch & RM=1           ,2270
      22      69     213     294
Rch & RM=1           ,630
      22      69     213     294
Boundary for Rch & Prof#=2           , 1
Up Type= 1
Up Value=2.5
Dn Type= 32767
Dn Value=0
Boundary for Rch & Prof#=2           , 2
Up Type= 1
Up Value=2.5
Dn Type= 32767
Dn Value=0
Boundary for Rch & Prof#=2           , 3
Up Type= 1
Up Value=2.5
Dn Type= 32767
Dn Value=0
Boundary for Rch & Prof#=2           , 4
Up Type= 1
Up Value=2.5
Dn Type= 32767
Dn Value=0
Boundary for Rch & Prof#=1           , 1
Up Type= 32767
Up Value=0
Dn Type= 1
Dn Value=2.5
Boundary for Rch & Prof#=1           , 2
Up Type= 32767
Up Value=0
Dn Type= 1
Dn Value=2.5
Boundary for Rch & Prof#=1           , 3
Up Type= 32767
Up Value=0
Dn Type= 1
Dn Value=2.5
Boundary for Rch & Prof#=1           , 4
Up Type= 32767
Up Value=0
Dn Type= 1
Dn Value=2.5

--- palmprop.g04 (geometry) ---

Geom Title=Palm Creek 96 Proposed Conditions
ViewRect= 0, 1, 1, 0
Reach=2
Rch X Y Up & X Y Dn=0.1,0.9,0.5,0.5
Rch Arrow X Y Up & X Y Dn=0,0,0,0
Rch Type=0

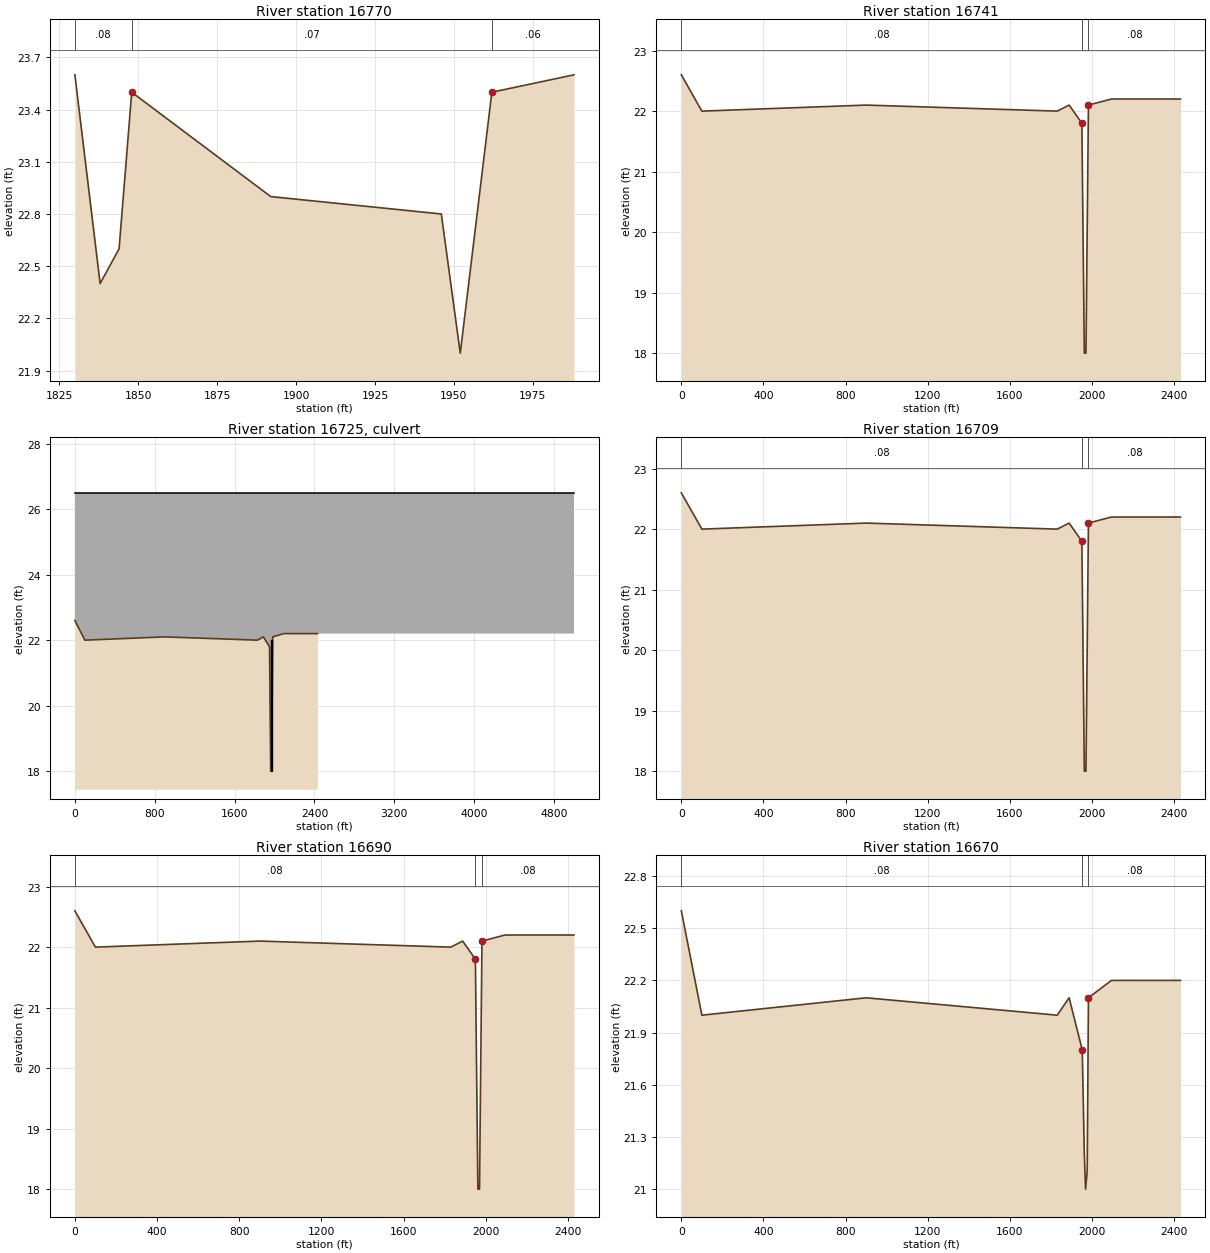
Type RM Length L Ch R =1,16770   ,61,61,61,0,0,0
Node Desc=SCS 175
#Sta/Elev= 9
    1830    23.6    1838    22.4    1844    22.6    1848    23.5    1892    22.9
    1946    22.8    1952      22    1962    23.5    1988    23.6
#Mann=3,0
    1830     .08       0    1848     .07       0    1962     .06       0
Bank Sta=1848,1962
Exp/Cntr=0.3,0.1

Type RM Length L Ch R =1,16741   ,32,32,32,0,0,0
Node Desc=SCS 166
#Sta/Elev= 11
       0    22.6     100      22     900    22.1    1830      22    1888    22.1
    1950    21.8    1962      18    1970      18    1982    22.1    2094    22.2
    2430    22.2
#Mann=3,0
       0     .08       0    1950     .07       0    1982     .08       0
Bank Sta=1950,1982
Exp/Cntr=0.3,0.1

Type RM Length L Ch R =2,16725   ,,,,0,0,0
Node Desc=DRIVEWAY PROPOSED 4 X 8
Bridge Culvert--1,0,-1,-1
Deck Dist Width WeirC Skew NumUp NumDn MinLoCord MaxHiCord MaxSubmerge Is_Ogee
0,13,2.6,,2,2,,,0.95,0
       0    5000
    26.5    26.5
      10      10
       0    5000
    26.5    26.5
      10      10
BR Coef= 1, 0, 0,, 0,,,0.8,0,0,1,
Culvert=2,4,8,32,0.012,0.5,1,8,1,18,1966,18,1966,Culvert #1  , 0

Type RM Length L Ch R =1,16709   ,19,19,19,0,0,0
Node Desc=SCS 166
#Sta/Elev= 11
       0    22.6     100      22     900    22.1    1830      22    1888    22.1
    1950    21.8    1962      18    1970      18    1982    22.1    2094    22.2
    2430    22.2
#Mann=3,0
       0     .08       0    1950     .07       0    1982     .08       0
Bank Sta=1950,1982
Exp/Cntr=0.3,0.1

Type RM Length L Ch R =1,16690   ,20,20,20,0,0,0
Node Desc=SCS 166
#Sta/Elev= 11
       0    22.6     100      22     900    22.1    1830      22    1888    22.1
    1950    21.8    1962      18    1970      18    1982    22.1    2094    22.2
    2430    22.2
#Mann=3,0
       0     .08       0    1950     .07       0    1982     .08       0
Bank Sta=1950,1982
Exp/Cntr=0.3,0.1

Type RM Length L Ch R =1,16670   ,970,970,970,0,0,0
Node Desc=SCS 166
#Sta/Elev= 12
       0    22.6     100      22     900    22.1    1830      22    1888    22.1
    1952    21.8    1962    21.2    1968      21    1976    21.1    1982    22.1
    2094    22.2    2430    22.2
#Mann=3,0
       0     .08       0    1952     .07       0    1982     .08       0
Bank Sta=1952,1982
Exp/Cntr=0.3,0.1

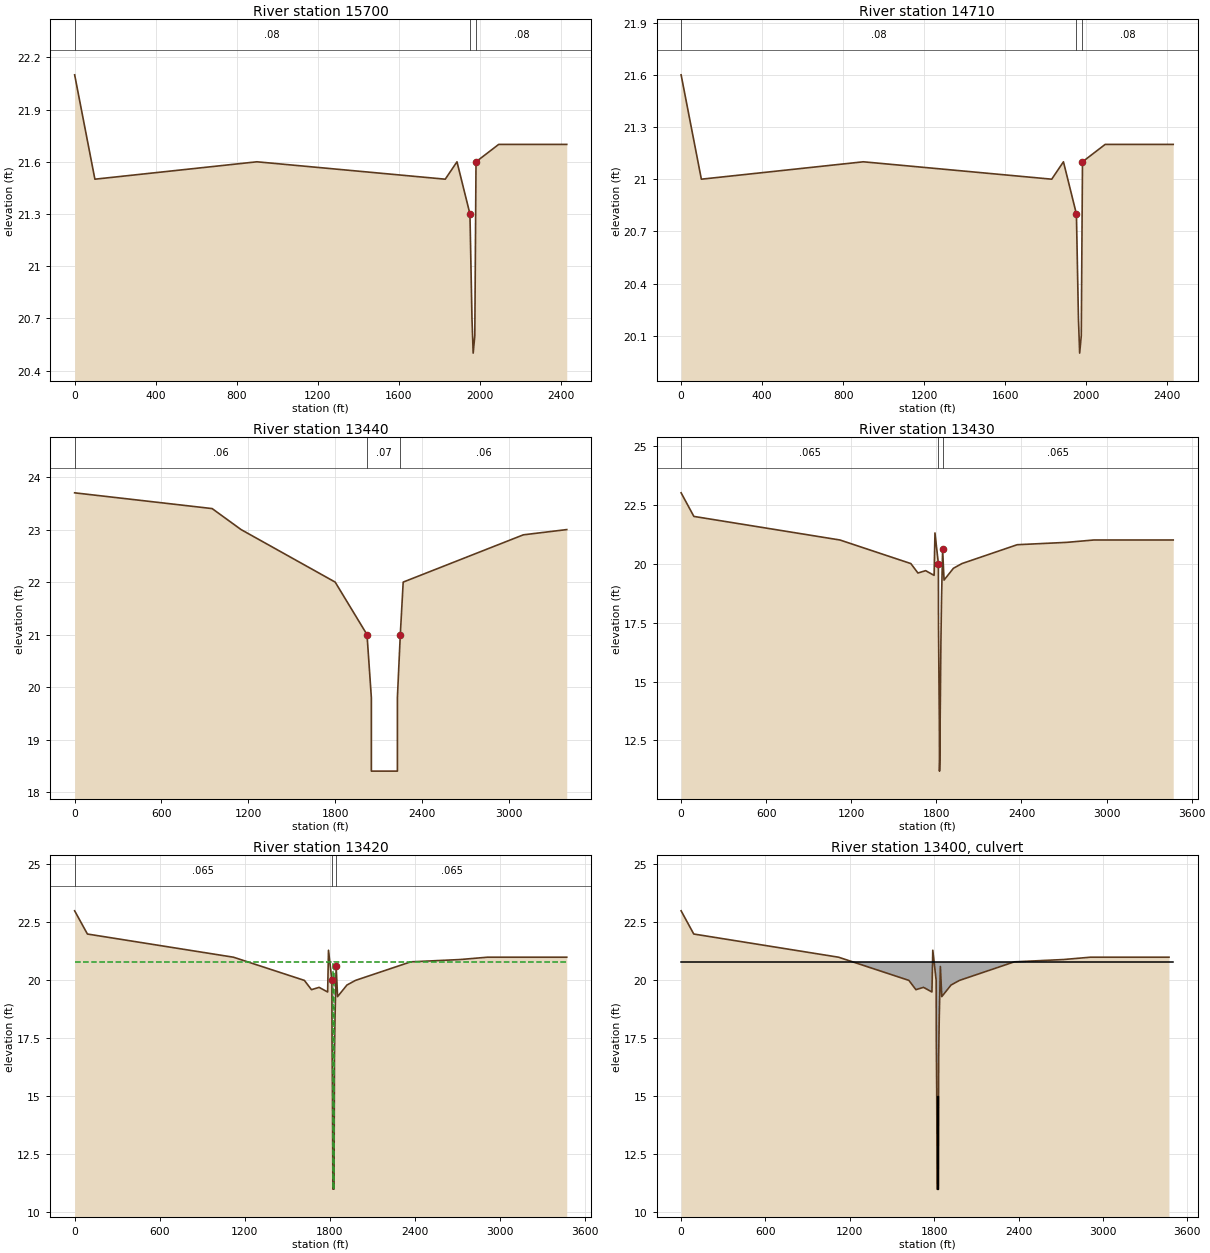
Type RM Length L Ch R =1,15700   ,990,990,990,0,0,0
Node Desc=SCS 165 +0.5'
#Sta/Elev= 12
       0    22.1     100    21.5     900    21.6    1830    21.5    1888    21.6
    1952    21.3    1962    20.7    1968    20.5    1976    20.6    1982    21.6
    2094    21.7    2430    21.7
#Mann=3,0
       0     .08       0    1952     .07       0    1982     .08       0
Bank Sta=1952,1982
Exp/Cntr=0.3,0.1

Type RM Length L Ch R =1,14710   ,1270,1270,1270,0,0,0
Node Desc=SCS 165
#Sta/Elev= 12
       0    21.6     100      21     900    21.1    1830      21    1888    21.1
    1952    20.8    1962    20.2    1968      20    1976    20.1    1982    21.1
    2094    21.2    2430    21.2
#Mann=3,0
       0     .08       0    1952     .07       0    1982     .08       0
Bank Sta=1952,1982
Exp/Cntr=0.3,0.1

Type RM Length L Ch R =1,13440   ,10,10,10,0,0,0
Node Desc=SCS 161
#Sta/Elev= 13
       0    23.7     950    23.4    1150      23    1800      22    2020      21
    2050    19.8    2050    18.4    2230    18.4    2230    19.8    2250      21
    2270      22    3100    22.9    3400      23
#Mann=3,0
       0     .06       0    2020     .07       0    2250     .06       0
Bank Sta=2020,2250
Exp/Cntr=0.3,0.1

Type RM Length L Ch R =1,13430   ,10,10,10,0,0,0
Node Desc=SCS 160
#Sta/Elev= 26
       0      23      90      22    1120      21    1620      20    1670    19.6
    1724    19.7    1784    19.5    1790    21.3    1814      20    1815    17.4
    1816    16.7    1818    15.2    1821    13.2    1822    11.2    1824    11.6
    1827    13.6    1832    16.7    1836    18.4    1844    20.6    1854    19.3
    1920    19.8    1980      20    2370    20.8    2720    20.9    2910      21
    3470      21
#Mann=3,0
       0    .065       0    1814     .07       0    1844    .065       0
Bank Sta=1814,1844
Exp/Cntr=0.5,0.3

Type RM Length L Ch R =1,13420   ,40,40,40,0,0,0
Node Desc=SCS 160
#Sta/Elev= 26
       0      23      90      22    1120      21    1620      20    1670    19.6
    1724    19.7    1784    19.5    1790    21.3    1814      20    1815    17.4
    1816    16.7    1818    15.2    1821      11    1822      11    1824      11
    1829      11    1832    16.7    1836    18.4    1844    20.6    1854    19.3
    1920    19.8    1980      20    2370    20.8    2720    20.9    2910      21
    3470      21
#Mann=3,0
       0    .065       0    1814     .07       0    1844    .065       0
#XS Ineff= 2 , 0
            1821    20.8    1829            20.8
Bank Sta=1814,1844
Exp/Cntr=0.5,0.3

Type RM Length L Ch R =2,13400   ,,,,0,0,0
Node Desc=REUBEN LANE PROP. 4 X 8
Bridge Culvert--1,0,-1,-1
Deck Dist Width WeirC Skew NumUp NumDn MinLoCord MaxHiCord MaxSubmerge Is_Ogee
5,18,2.6,,2,2,,,0.95,0
       0    3500
    20.8    20.8
      10      10
       0    3500
    20.8    20.8
      10      10
BR Coef= 1,-1, 0,, 0,,,0.8,0,0.08,0,
Culvert=2,4,8,40,0.012,0.5,1,10,1,11,1825,11,1825,Culvert #1  , 0

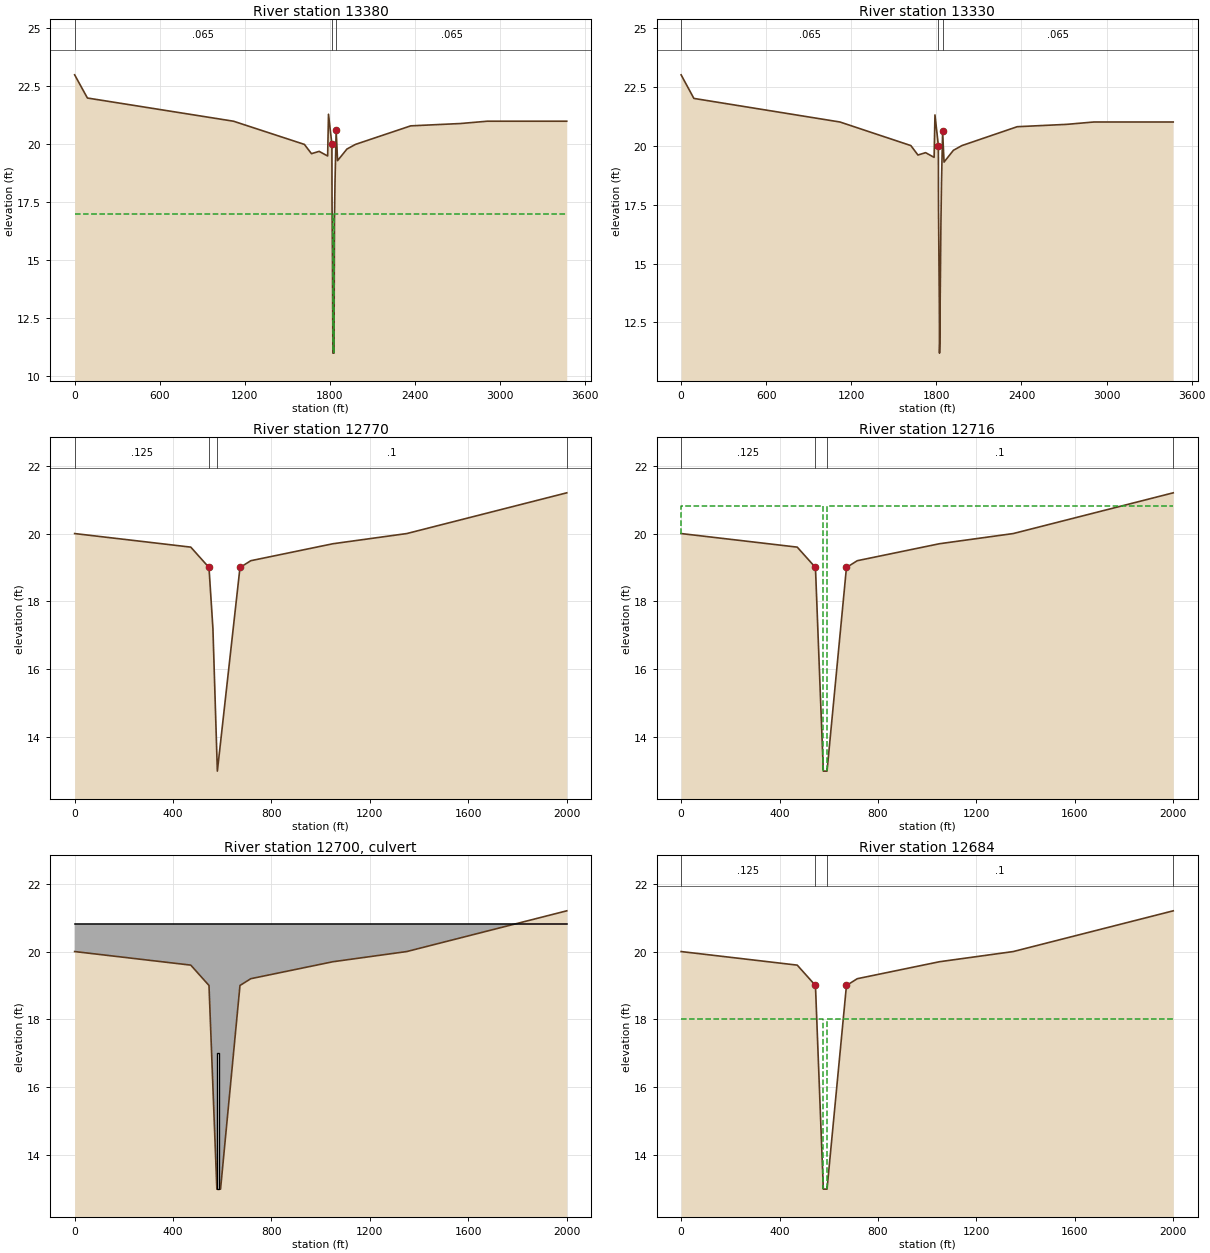
Type RM Length L Ch R =1,13380   ,50,50,50,0,0,0
Node Desc=SCS 155
#Sta/Elev= 26
       0      23      90      22    1120      21    1620      20    1670    19.6
    1724    19.7    1784    19.5    1790    21.3    1814      20    1815    17.4
    1816    16.7    1818    15.2    1821      11    1822      11    1824      11
    1829      11    1832    16.7    1836    18.4    1844    20.6    1854    19.3
    1920    19.8    1980      20    2370    20.8    2720    20.9    2910      21
    3470      21
#Mann=3,1
       0    .065       1    1814     .07       9    1844    .065      19
#XS Ineff= 2 , 0
            1821      17    1829              17
Bank Sta=1814,1844
Exp/Cntr=0.3,0.1

Type RM Length L Ch R =1,13330   ,560,560,560,0,0,0
Node Desc=SCS 155
#Sta/Elev= 26
       0      23      90      22    1120      21    1620      20    1670    19.6
    1724    19.7    1784    19.5    1790    21.3    1814      20    1815    17.4
    1816    16.7    1818    15.2    1821    13.2    1822    11.2    1824    11.6
    1827    13.6    1832    16.7    1836    18.4    1844    20.6    1854    19.3
    1920    19.8    1980      20    2370    20.8    2720    20.9    2910      21
    3470      21
#Mann=3,1
       0    .065       1    1814     .07       9    1844    .065      19
Bank Sta=1814,1844
Exp/Cntr=0.3,0.1

Type RM Length L Ch R =1,12770   ,54,54,54,0,0,0
Node Desc=SCS 1
#Sta/Elev= 10
       0      20     472    19.6     546      19     562    17.2     580      13
     672      19     716    19.2    1050    19.7    1350      20    2000    21.2
#Mann=4,1
       0    .125       1     546     .07       3     580      .1       5
    2000     .08      10
Bank Sta=546,672
Exp/Cntr=0.3,0.1

Type RM Length L Ch R =1,12716   ,32,32,32,0,0,0
Node Desc=SCS 1
#Sta/Elev= 10
       0      20     472    19.6     546      19     578      13     593      13
     672      19     716    19.2    1050    19.7    1350      20    2000    21.2
#Mann=4,1
       0    .125       1     546     .07       3     593      .1       5
    2000     .08      10
#XS Ineff= 2 , 0
             578    20.8     593            20.8
Bank Sta=546,672
Exp/Cntr=0.3,0.1

Type RM Length L Ch R =2,12700   ,,,,0,0,0
Node Desc=S. OF REUBEN LN.  PROP. 4 X 8
Bridge Culvert--1,0,-1,-1
Deck Dist Width WeirC Skew NumUp NumDn MinLoCord MaxHiCord MaxSubmerge Is_Ogee
0,15,2.6,,2,2,,,0.95,0
       0    2000
    20.8    20.8
      12      12
       0    2000
    20.8    20.8
      12      12
Culvert=2,4,8,32,0.012,0.5,1,10,1,13,582,13,582,Culvert #1  , 0

Type RM Length L Ch R =1,12684   ,234,234,234,0,0,0
Node Desc=SCS 1
#Sta/Elev= 10
       0      20     472    19.6     546      19     578      13     593      13
     672      19     716    19.2    1050    19.7    1350      20    2000    21.2
#Mann=4,1
       0    .125       1     546     .07       3     593      .1       5
    2000     .08      10
#XS Ineff= 2 , 0
             578      18     593              18
Bank Sta=546,672
Exp/Cntr=0.3,0.1

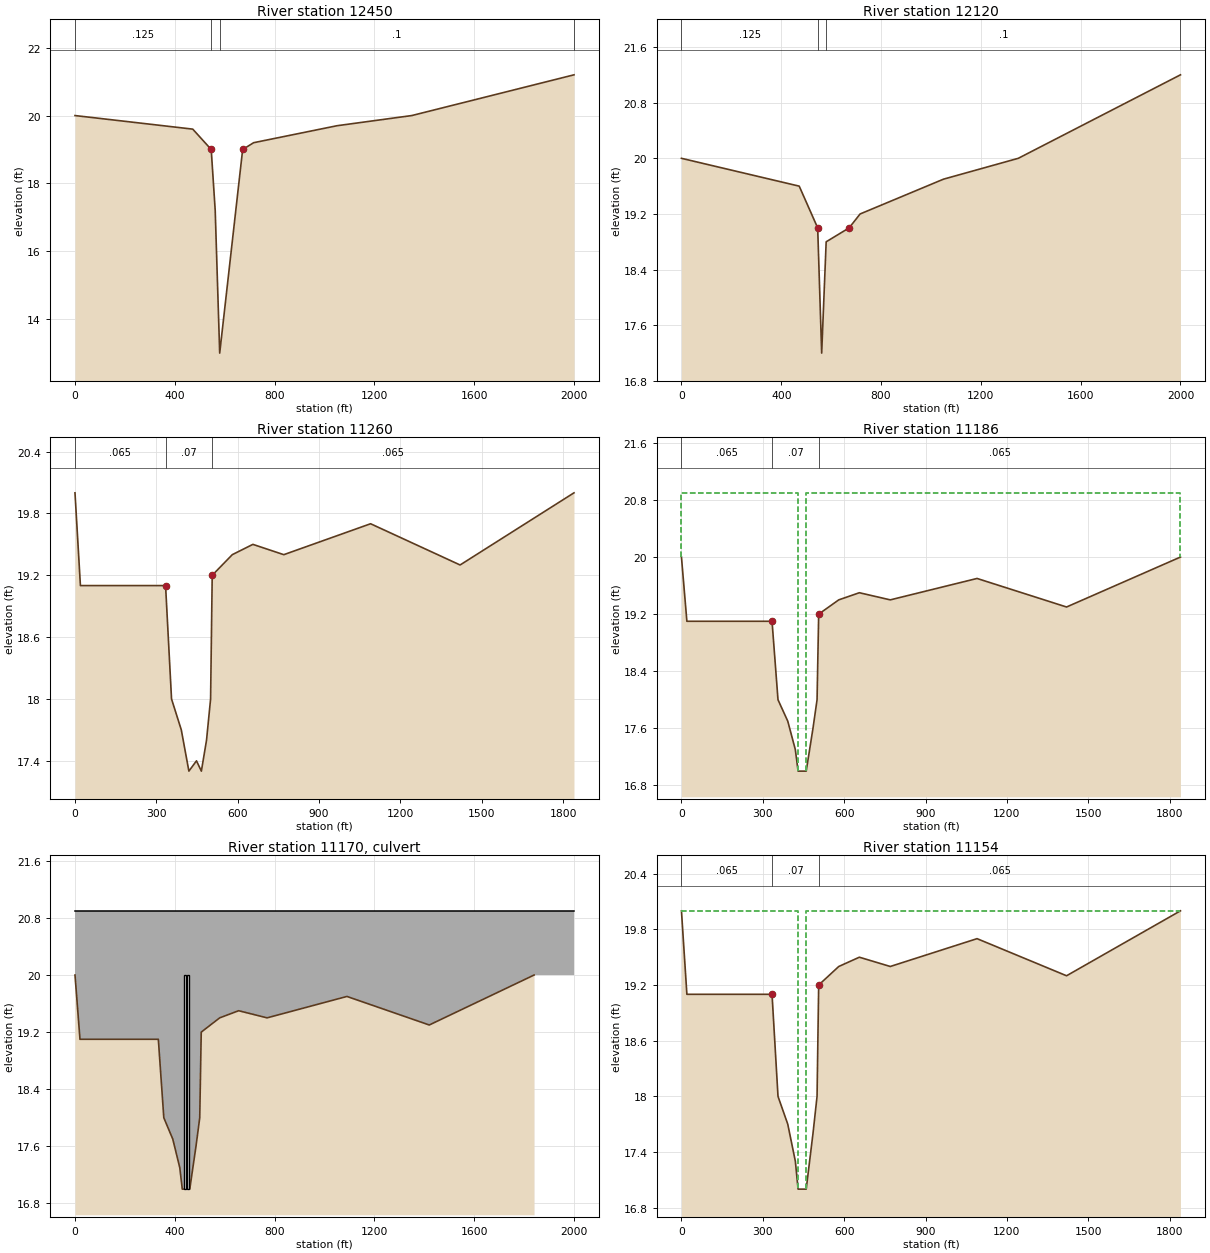
Type RM Length L Ch R =1,12450   ,330,330,330,0,0,0
Node Desc=SCS 1
#Sta/Elev= 10
       0      20     472    19.6     546      19     562    17.2     580      13
     672      19     716    19.2    1050    19.7    1350      20    2000    21.2
#Mann=4,1
       0    .125       1     546     .07       3     580      .1       5
    2000     .08      10
Bank Sta=546,672
Exp/Cntr=0.3,0.1

Type RM Length L Ch R =1,12120   ,860,860,860,0,0,0
Node Desc=SCS 1
#Sta/Elev= 10
       0      20     472    19.6     546      19     562    17.2     580    18.8
     672      19     716    19.2    1050    19.7    1350      20    2000    21.2
#Mann=4,1
       0    .125       1     546     .07       3     580      .1       5
    2000     .08      10
Bank Sta=546,672
Exp/Cntr=0.3,0.1

Type RM Length L Ch R =1,11260   ,74,74,74,0,0,0
Node Desc=SCS 145
#Sta/Elev= 18
       0      20      20    19.1     270    19.1     334    19.1     356      18
     392    17.7     420    17.3     448    17.4     466    17.3     485    17.6
     500      18     506    19.2     580    19.4     656    19.5     770    19.4
    1090    19.7    1420    19.3    1840      20
#Mann=3,1
       0    .065       1     334     .07       4     506    .065      12
Bank Sta=334,506
Exp/Cntr=0.3,0.1

Type RM Length L Ch R =1,11186   ,32,32,32,0,0,0
Node Desc=SCS 145
#Sta/Elev= 18
       0      20      20    19.1     270    19.1     334    19.1     356      18
     392    17.7     420    17.3     430      17     460      17     485    17.6
     500      18     506    19.2     580    19.4     656    19.5     770    19.4
    1090    19.7    1420    19.3    1840      20
#Mann=3,1
       0    .065       1     334     .07       4     506    .065      12
#XS Ineff= 2 , 0
             430    20.9     460            20.9
Bank Sta=334,506
Exp/Cntr=0.3,0.1

Type RM Length L Ch R =2,11170   ,,,,0,0,0
Node Desc=FPL ESMT. PROP. DBL. 3 X 9
Bridge Culvert--1,0,-1,-1
Deck Dist Width WeirC Skew NumUp NumDn MinLoCord MaxHiCord MaxSubmerge Is_Ogee
0,12,2.6,,2,2,,,0.95,0
       0    2000
    20.9    20.9
      17      17
       0    2000
    20.9    20.9
      17      17
Multiple Barrel Culv=2,3,8,32,0.012,0.5,1,10,1,17,17, 2,Culvert #1  , 0
     442     442     453     453

Type RM Length L Ch R =1,11154   ,74,74,74,0,0,0
Node Desc=SCS 145
#Sta/Elev= 18
       0      20      20    19.1     270    19.1     334    19.1     356      18
     392    17.7     420    17.3     430      17     460      17     485    17.6
     500      18     506    19.2     580    19.4     656    19.5     770    19.4
    1090    19.7    1420    19.3    1840      20
#Mann=3,1
       0    .065       1     334     .07       4     506    .065      12
#XS Ineff= 2 , 0
             430      20     460              20
Bank Sta=334,506
Exp/Cntr=0.3,0.1

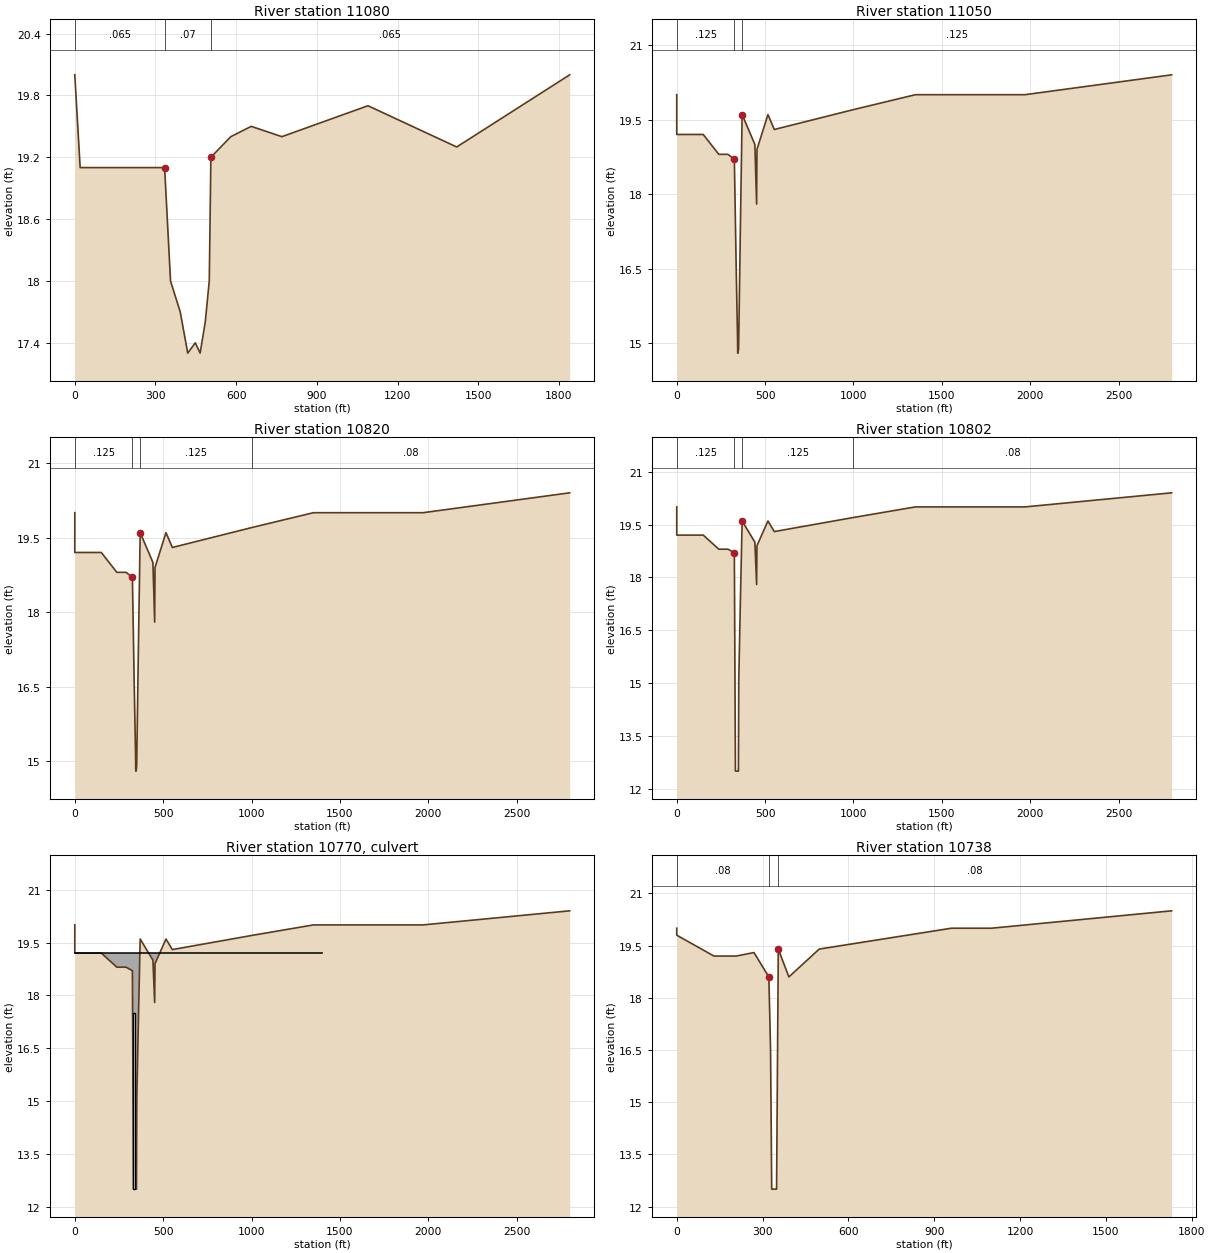
Type RM Length L Ch R =1,11080   ,30,30,30,0,0,0
Node Desc=SCS 145
#Sta/Elev= 18
       0      20      20    19.1     270    19.1     334    19.1     356      18
     392    17.7     420    17.3     448    17.4     466    17.3     485    17.6
     500      18     506    19.2     580    19.4     656    19.5     770    19.4
    1090    19.7    1420    19.3    1840      20
#Mann=3,1
       0    .065       1     334     .07       4     506    .065      12
Bank Sta=334,506
Exp/Cntr=0.3,0.1

Type RM Length L Ch R =1,11050   ,230,230,230,0,0,0
Node Desc=SCS 140
#Sta/Elev= 25
       0      20       0    19.2      40    19.2     150    19.2     238    18.8
     290    18.8     326    18.7     336    16.6     344    15.1     345    14.8
     347    14.8     350    14.9     351    15.1     360    17.3     370    19.6
     442      19     452    17.8     454    18.9     516    19.6     552    19.3
    1000    19.7    1350      20    1650      20    1970      20    2800    20.4
#Mann=3,0
       0    .125       0     326     .07       0     370    .125       0
Bank Sta=326,370
Exp/Cntr=0.5,0.3

Type RM Length L Ch R =1,10820   ,18,18,18,0,0,0
Node Desc=SCS 135
#Sta/Elev= 25
       0      20       0    19.2      40    19.2     150    19.2     238    18.8
     290    18.8     326    18.7     336    16.6     344    15.1     345    14.8
     347    14.8     350    14.9     351    15.1     360    17.3     370    19.6
     442      19     452    17.8     454    18.9     516    19.6     552    19.3
    1000    19.7    1350      20    1650      20    1970      20    2800    20.4
#Mann=4,1
       0    .125       1     326     .07       7     370    .125      15
    1000     .08      21
Bank Sta=326,370
Exp/Cntr=0.3,0.1

Type RM Length L Ch R =1,10802   ,64,64,64,0,0,0
Node Desc=SCS 135
#Sta/Elev= 22
       0      20       0    19.2      40    19.2     150    19.2     238    18.8
     290    18.8     326    18.7     332    12.5     349    12.5     351    15.1
     360    17.3     370    19.6     442      19     452    17.8     454    18.9
     516    19.6     552    19.3    1000    19.7    1350      20    1650      20
    1970      20    2800    20.4
#Mann=4,1
       0    .125       1     326     .07       7     370    .125      12
    1000     .08      18
Bank Sta=326,370
Exp/Cntr=0.3,0.1

Type RM Length L Ch R =2,10770   ,,,,0,0,0
Node Desc=DEAL ROAD PROP. 5 X 10
Bridge Culvert--1,0,-1,-1
Deck Dist Width WeirC Skew NumUp NumDn MinLoCord MaxHiCord MaxSubmerge Is_Ogee
0,30,2.6,,2,2,,,0.95,0
       0    1400
    19.2    19.2
      12      12
       0    1400
    19.2    19.2
      12      12
Culvert=2,5,10,64,0.012,0.5,1,10,1,12.5,336,12.5,336,Culvert #1  , 0

Type RM Length L Ch R =1,10738   ,18,18,18,0,0,0
Node Desc=SCS 130
#Sta/Elev= 15
       0      20       0    19.8     130    19.2     208    19.2     270    19.3
     322    18.6     328    16.5     332    12.5     349    12.5     355    19.4
     392    18.6     498    19.4     960      20    1100      20    1730    20.5
#Mann=3,0
       0     .08       0     322     .07       0     355     .08       0
Bank Sta=322,355
Exp/Cntr=0.5,0.3

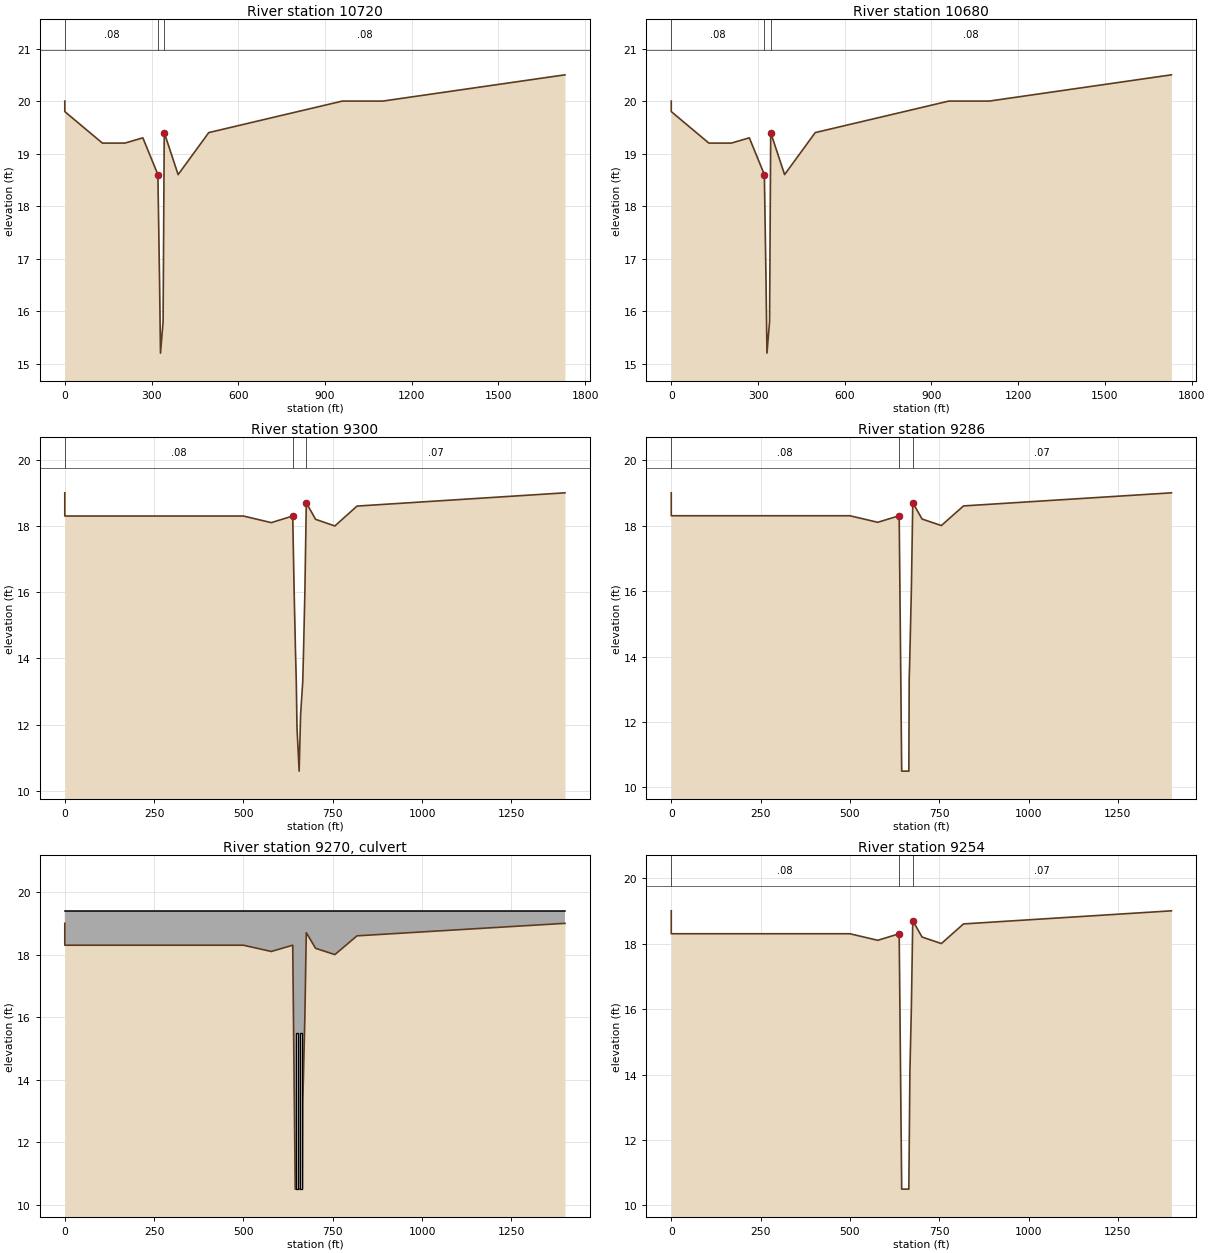
Type RM Length L Ch R =1,10720   ,40,40,40,0,0,0
Node Desc=SCS 130
#Sta/Elev= 15
       0      20       0    19.8     130    19.2     208    19.2     270    19.3
     322    18.6     328    16.5     331    15.2     340    15.8     344    19.4
     392    18.6     498    19.4     960      20    1100      20    1730    20.5
#Mann=3,0
       0     .08       0     322     .07       0     344     .08       0
Bank Sta=322,344
Exp/Cntr=0.5,0.3

Type RM Length L Ch R =1,10680   ,1380,1380,1380,0,0,0
Node Desc=SCS 125
#Sta/Elev= 15
       0      20       0    19.8     130    19.2     208    19.2     270    19.3
     322    18.6     328    16.5     331    15.2     340    15.8     344    19.4
     392    18.6     498    19.4     960      20    1100      20    1730    20.5
#Mann=3,1
       0     .08       1     322     .07       6     344     .08      10
Bank Sta=322,344
Exp/Cntr=0.3,0.1

Type RM Length L Ch R =1,9300    ,14,14,14,0,0,0
Node Desc=SCS 120
#Sta/Elev= 19
       0      19       0    18.3     500    18.3     578    18.1     638    18.3
     642      16     646    14.1     648    13.3     650    11.9     656    10.6
     660    12.3     666    13.3     668    14.1     672      16     676    18.7
     702    18.2     756      18     818    18.6    1400      19
#Mann=3,1
       0     .08       1     638     .07       5     676     .07      15
Bank Sta=638,676
Exp/Cntr=0.3,0.1

Type RM Length L Ch R =1,9286    ,32,32,32,0,0,0
Node Desc=SCS 120
#Sta/Elev= 15
       0      19       0    18.3     500    18.3     578    18.1     638    18.3
     645    10.5     665    10.5     666    13.3     668    14.1     672      16
     676    18.7     702    18.2     756      18     818    18.6    1400      19
#Mann=3,1
       0     .08       1     638     .07       5     676     .07      11
Bank Sta=638,676
Exp/Cntr=0.3,0.1

Type RM Length L Ch R =2,9270    ,,,,0,0,0
Node Desc=PIONEER RD. CULVERT PROP. DBL. 5 X 6
Bridge Culvert--1,0,-1,-1
Deck Dist Width WeirC Skew NumUp NumDn MinLoCord MaxHiCord MaxSubmerge Is_Ogee
0,13,2.6,,2,2,,,0.95,0
       0    1400
    19.4    19.4
      10      10
       0    1400
    19.4    19.4
      10      10
Culvert=2,5,6,32,0.012,0.5,1,10,1,10.5,650,10.5,650,Culvert #1  , 0
Culvert=2,5,6,32,0.012,0.5,1,10,1,10.5,660,10.5,660,Culvert #2  , 0

Type RM Length L Ch R =1,9254    ,64,64,64,0,0,0
Node Desc=SCS 120
#Sta/Elev= 14
       0      19       0    18.3     500    18.3     578    18.1     638    18.3
     645    10.5     665    10.5     668    14.1     672      16     676    18.7
     702    18.2     756      18     818    18.6    1400      19
#Mann=3,1
       0     .08       1     638     .07       5     676     .07      10
Bank Sta=638,676
Exp/Cntr=0.3,0.1

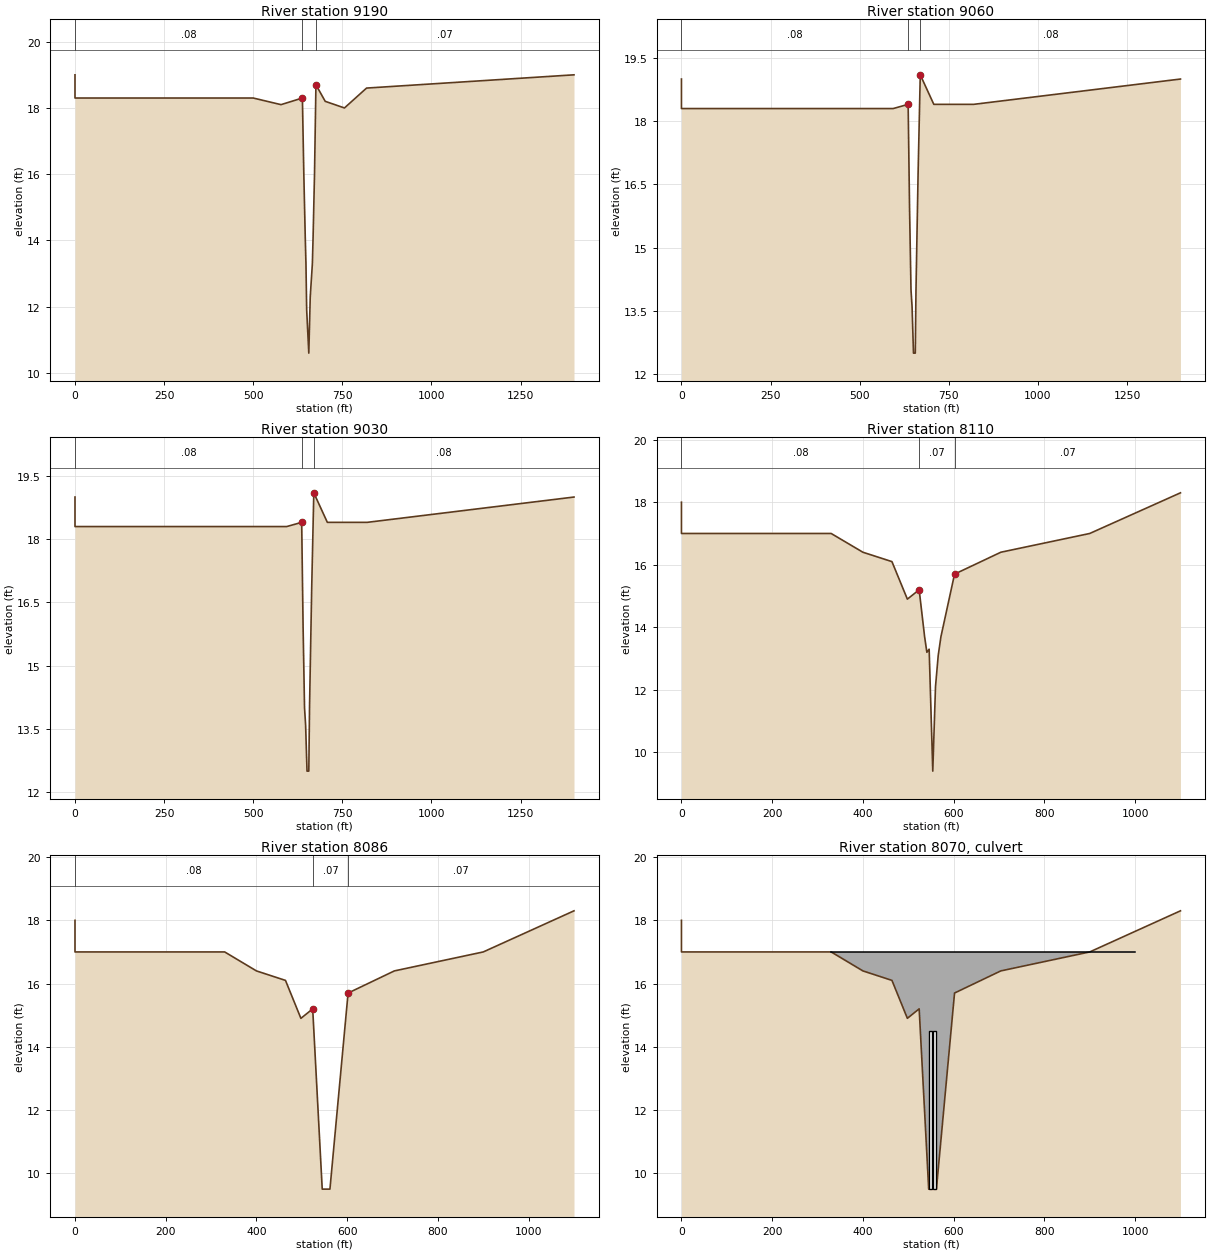
Type RM Length L Ch R =1,9190    ,130,130,130,0,0,0
Node Desc=SCS 120
#Sta/Elev= 19
       0      19       0    18.3     500    18.3     578    18.1     638    18.3
     642      16     646    14.1     648    13.3     650    11.9     656    10.6
     660    12.3     666    13.3     668    14.1     672      16     676    18.7
     702    18.2     756      18     818    18.6    1400      19
#Mann=3,1
       0     .08       1     638     .07       5     676     .07      15
Bank Sta=638,676
Exp/Cntr=0.3,0.1

Type RM Length L Ch R =1,9060    ,30,30,30,0,0,0
Node Desc=SCS 115
#Sta/Elev= 16
       0      19       0    18.3     500    18.3     594    18.3     636    18.4
     640    15.9     644      14     647    13.6     651    12.5     656    12.5
     658      14     664    16.8     670    19.1     708    18.4     820    18.4
    1400      19
#Mann=3,0
       0     .08       0     636     .07       0     670     .08       0
Bank Sta=636,670
Exp/Cntr=0.5,0.3

Type RM Length L Ch R =1,9030    ,920,920,920,0,0,0
Node Desc=SCS 110
#Sta/Elev= 16
       0      19       0    18.3     500    18.3     594    18.3     636    18.4
     640    15.9     644      14     647    13.6     651    12.5     656    12.5
     658      14     664    16.8     670    19.1     708    18.4     820    18.4
    1400      19
#Mann=3,1
       0     .08       1     636     .07       5     670     .08      13
Bank Sta=636,670
Exp/Cntr=0.3,0.1

Type RM Length L Ch R =1,8110    ,24,24,24,0,0,0
Node Desc=SCS 105
#Sta/Elev= 18
       0      18       0      17     330      17     400    16.4     464    16.1
     498    14.9     524    15.2     536    13.7     541    13.2     546    13.3
     554     9.4     560    12.1     566    13.1     572    13.7     602    15.7
     704    16.4     900      17    1100    18.3
#Mann=3,1
       0     .08       1     524     .07       7     602     .07      15
Bank Sta=524,602
Exp/Cntr=0.3,0.1

Type RM Length L Ch R =1,8086    ,32,32,32,0,0,0
Node Desc=SCS 105
#Sta/Elev= 13
       0      18       0      17     330      17     400    16.4     464    16.1
     498    14.9     524    15.2     545     9.5     562     9.5     602    15.7
     704    16.4     900      17    1100    18.3
#Mann=3,1
       0     .08       1     524     .07       7     602     .07      10
Bank Sta=524,602
Exp/Cntr=0.3,0.1

Type RM Length L Ch R =2,8070    ,,,,0,0,0
Node Desc=DEUCE RD. PROP. DBL. 5 X 6
Bridge Culvert--1,0,-1,-1
Deck Dist Width WeirC Skew NumUp NumDn MinLoCord MaxHiCord MaxSubmerge Is_Ogee
0,18,2.6,,6,6,,,0.95,0
     330     500     500     600     600    1000
      17      17      17      17      17      17
      12      12       8       8      12      12
     330     500     500     600     600    1000
      17      17      17      17      17      17
      12      12       8       8      12      12
BR Coef= 1, 0, 0,1.25, 0,,,0.8,0,0.8,0,
Multiple Barrel Culv=2,5,6,32,0.012,0.5,1,10,1,9.5,9.5, 2,Culvert #1  , 0
     549     549     558     558

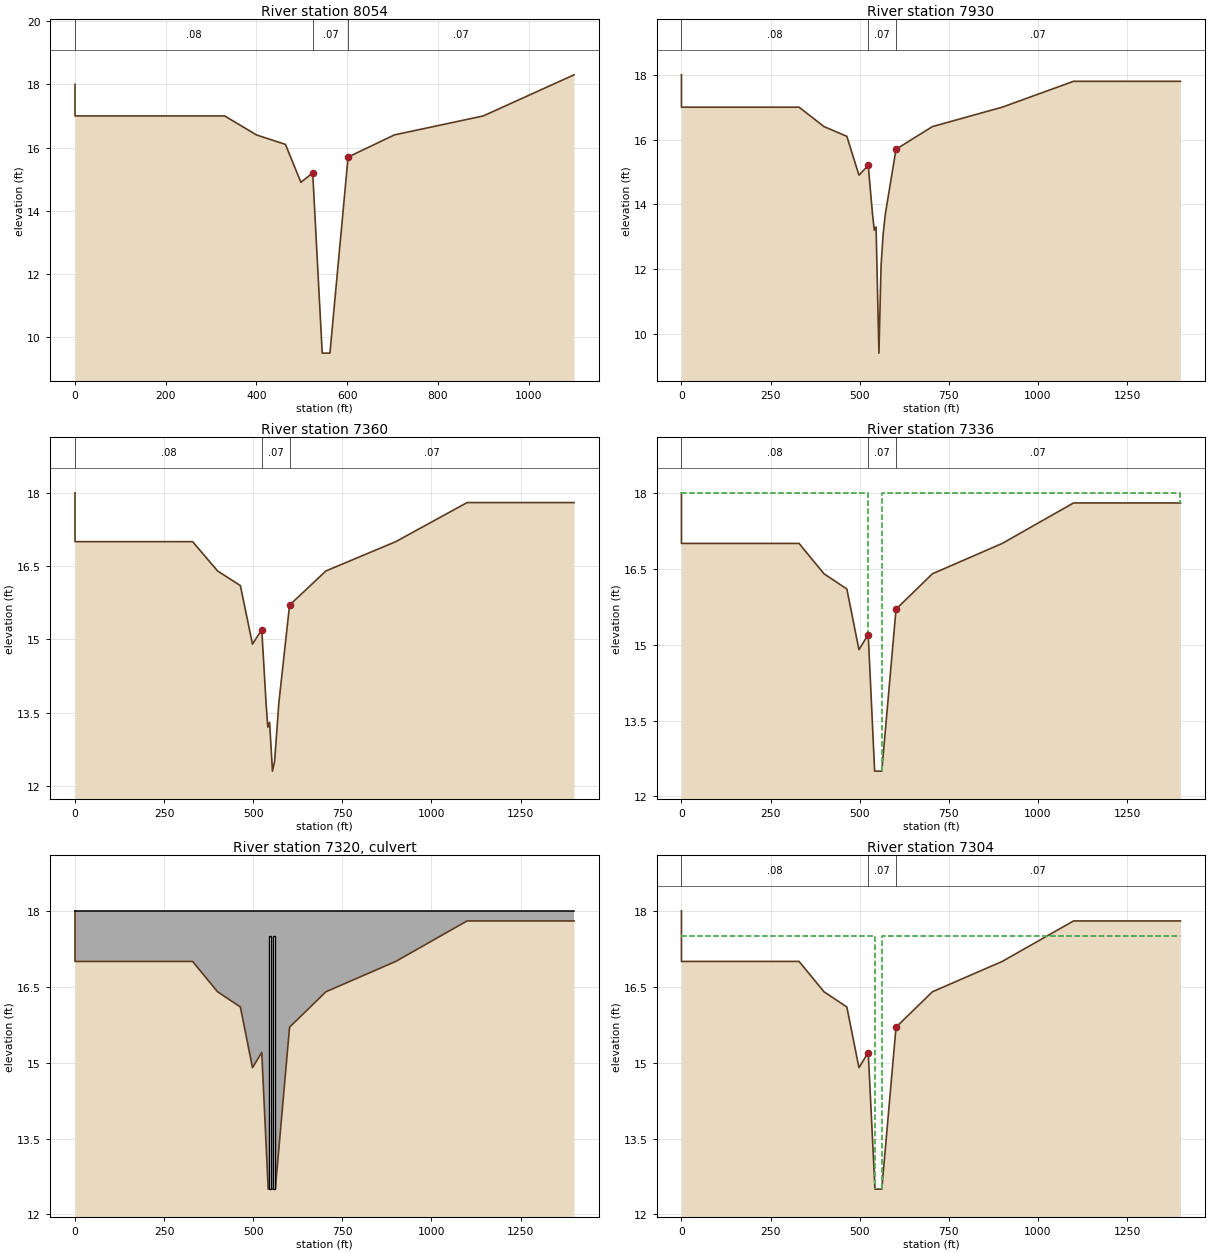
Type RM Length L Ch R =1,8054    ,124,124,124,0,0,0
Node Desc=SCS 105
#Sta/Elev= 13
       0      18       0      17     330      17     400    16.4     464    16.1
     498    14.9     524    15.2     545     9.5     562     9.5     602    15.7
     704    16.4     900      17    1100    18.3
#Mann=3,1
       0     .08       1     524     .07       7     602     .07      10
Bank Sta=524,602
Exp/Cntr=0.3,0.1

Type RM Length L Ch R =1,7930    ,570,570,570,0,0,0
Node Desc=SCS 105
#Sta/Elev= 19
       0      18       0      17     330      17     400    16.4     464    16.1
     498    14.9     524    15.2     536    13.7     541    13.2     546    13.3
     554     9.4     560    12.1     566    13.1     572    13.7     602    15.7
     704    16.4     900      17    1100    17.8    1400    17.8
#Mann=3,1
       0     .08       1     524     .07       7     602     .07      15
Bank Sta=524,602
Exp/Cntr=0.3,0.1

Type RM Length L Ch R =1,7360    ,24,24,24,0,0,0
Node Desc=SCS 105
#Sta/Elev= 19
       0      18       0      17     330      17     400    16.4     464    16.1
     498    14.9     524    15.2     536    13.7     541    13.2     546    13.3
     554    12.3     560    12.5     566    13.1     572    13.7     602    15.7
     704    16.4     900      17    1100    17.8    1400    17.8
#Mann=3,1
       0     .08       1     524     .07       7     602     .07      15
Bank Sta=524,602
Exp/Cntr=0.3,0.1

Type RM Length L Ch R =1,7336    ,32,32,32,0,0,0
Node Desc=SCS 105
#Sta/Elev= 14
       0      18       0      17     330      17     400    16.4     464    16.1
     498    14.9     524    15.2     542    12.5     562    12.5     602    15.7
     704    16.4     900      17    1100    17.8    1400    17.8
#Mann=3,1
       0     .08       1     524     .07       7     602     .07      10
#XS Ineff= 2 , 0
             524      18     562              18
Bank Sta=524,602
Exp/Cntr=0.3,0.1

Type RM Length L Ch R =2,7320    ,,,,0,0,0
Node Desc=4,700' N. OF SR 78 PROP DBL 5 X 7
Bridge Culvert--1,0,-1,-1
Deck Dist Width WeirC Skew NumUp NumDn MinLoCord MaxHiCord MaxSubmerge Is_Ogee
0,10,2.6,,2,2,,,0.95,0
       0    1400
      18      18
      10      10
       0    1400
      18      18
      10      10
Multiple Barrel Culv=2,5,7,32,0.012,0.5,1,8,3,12.5,12.5, 2,Culvert #1  , 0
     547     547     558     558

Type RM Length L Ch R =1,7304    ,134,134,134,0,0,0
Node Desc=SCS 105
#Sta/Elev= 17
       0      18       0      17     330      17     400    16.4     464    16.1
     498    14.9     524    15.2     543    12.5     546    12.5     554    12.5
     562    12.5     562    12.5     602    15.7     704    16.4     900      17
    1100    17.8    1400    17.8
#Mann=3,1
       0     .08       1     524     .07       7     602     .07      13
#XS Ineff= 2 , 0
             543    17.5     562            17.5
Bank Sta=524,602
Exp/Cntr=0.3,0.1