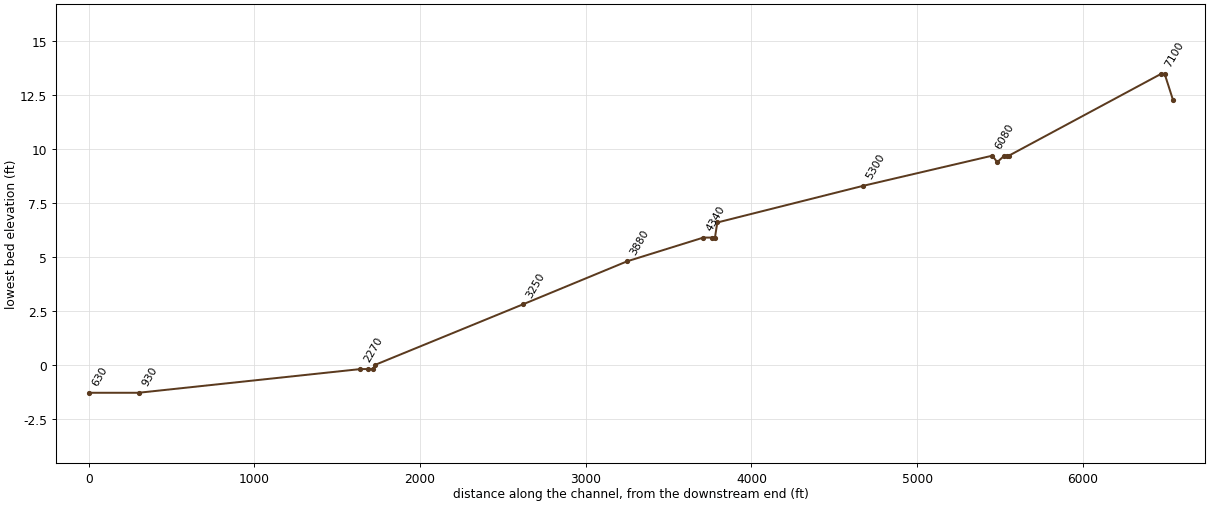
HEC-RAS study palmprop.prj: Palm Creek Proposed Cond.  1996

--- palmprop.g04 (geometry) --- (continued)

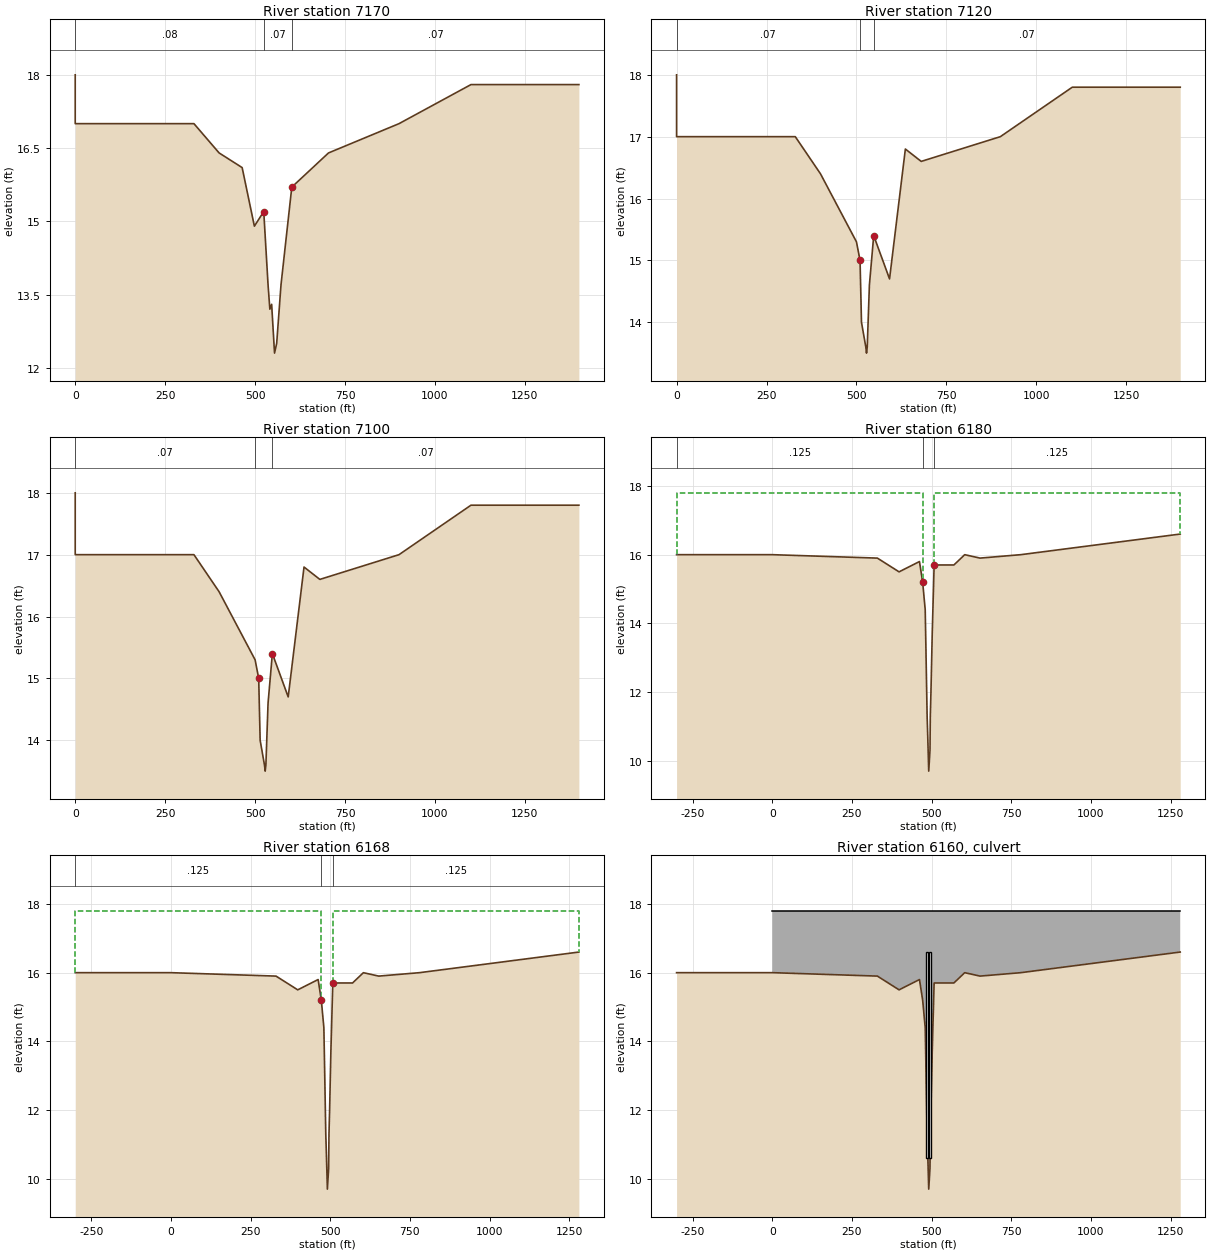
Type RM Length L Ch R =1,7170    ,50,50,50,0,0,0
Node Desc=SCS 105
#Sta/Elev= 19
       0      18       0      17     330      17     400    16.4     464    16.1
     498    14.9     524    15.2     536    13.7     541    13.2     546    13.3
     554    12.3     560    12.5     566    13.1     572    13.7     602    15.7
     704    16.4     900      17    1100    17.8    1400    17.8
#Mann=3,1
       0     .08       1     524     .07       7     602     .07      15
Bank Sta=524,602
Exp/Cntr=0.3,0.1

Type RM Length L Ch R =1,7120    ,20,20,20,0,0,0
Node Desc=SCS 100
#Sta/Elev= 18
       0      18       0      17     330      17     400    16.4     500    15.3
     510      15     514      14     526    13.6     528    13.5     530    13.6
     536    14.6     548    15.4     592    14.7     636    16.8     680    16.6
     900      17    1100    17.8    1400    17.8
#Mann=3,0
       0     .07       0     510     .07       0     548     .07       0
Bank Sta=510,548
Exp/Cntr=0.5,0.3

Type RM Length L Ch R =1,7100    ,920,920,920,0,0,0
Node Desc=SCS 95
#Sta/Elev= 18
       0      18       0      17     330      17     400    16.4     500    15.3
     510      15     514      14     526    13.6     528    13.5     530    13.6
     536    14.6     548    15.4     592    14.7     636    16.8     680    16.6
     900      17    1100    17.8    1400    17.8
#Mann=3,1
       0     .07       1     500     .07       5     548     .07      12
Bank Sta=510,548
Exp/Cntr=0.3,0.1

Type RM Length L Ch R =1,6180    ,12,12,12,0,0,0
Node Desc=SCS 852
#Sta/Elev= 21
    -300      16       0      16     330    15.9     398    15.5     462    15.8
     472    15.2     480    14.4     482    13.4     486    11.3     488    10.7
     491     9.7     495    10.3     496    11.3     498      12     502    13.7
     508    15.7     570    15.7     604      16     652    15.9     780      16
    1280    16.6
#Mann=3,0
    -300    .125       0     472     .07       0     508    .125       0
#XS Ineff= 2 , 0
             472    17.8     508            17.8
Bank Sta=472,508
Exp/Cntr=0.5,0.3

Type RM Length L Ch R =1,6168    ,15.4,15.4,15.4,0,0,0
Node Desc=SCS 852
#Sta/Elev= 21
    -300      16       0      16     330    15.9     398    15.5     462    15.8
     472    15.2     480    14.4     482    13.4     486    11.3     488    10.7
     491     9.7     495    10.3     496    11.3     498      12     502    13.7
     508    15.7     570    15.7     604      16     652    15.9     780      16
    1280    16.6
#Mann=3,0
    -300    .125       0     472     .07       0     508    .125       0
#XS Ineff= 2 , 0
             472    17.8     508            17.8
Bank Sta=472,508
Exp/Cntr=0.5,0.3

Type RM Length L Ch R =2,6160    ,,,,0,0,0
Node Desc=AQUA VISTA BOX CULVERT
Bridge Culvert--1,0,-1,-1
Deck Dist Width WeirC Skew NumUp NumDn MinLoCord MaxHiCord MaxSubmerge Is_Ogee
0,15.4,2.7,,17,17,17.8,,0.95,0
       0     330     398     462     472     480     482     482     498     498
     502     508     570     604     652     780    1280
    17.8    17.8    17.8    17.8    17.8    17.8    17.8    17.8    17.8    17.8
    17.8    17.8    17.8    17.8    17.8    17.8    17.8
       9       9       9       9       9       9       9       9       9       9
       9       9       9       9       9       9       9
       0     330     398     462     472     480     482     482     498     498
     502     508     570     604     652     780    1280
    17.8    17.8    17.8    17.8    17.8    17.8    17.8    17.8    17.8    17.8
    17.8    17.8    17.8    17.8    17.8    17.8    17.8
       9       9       9       9       9       9       9       9       9       9
       9       9       9       9       9       9       9
BR Coef= 0, 0,-1,1.25, 0,,,0.8006408,0,2,2,16.8
Multiple Barrel Culv=2,6,8,15,0.012,0.2,0.2,8,2,10.6,10.6, 2,Culvert #1  , 0
     485     485     495     495

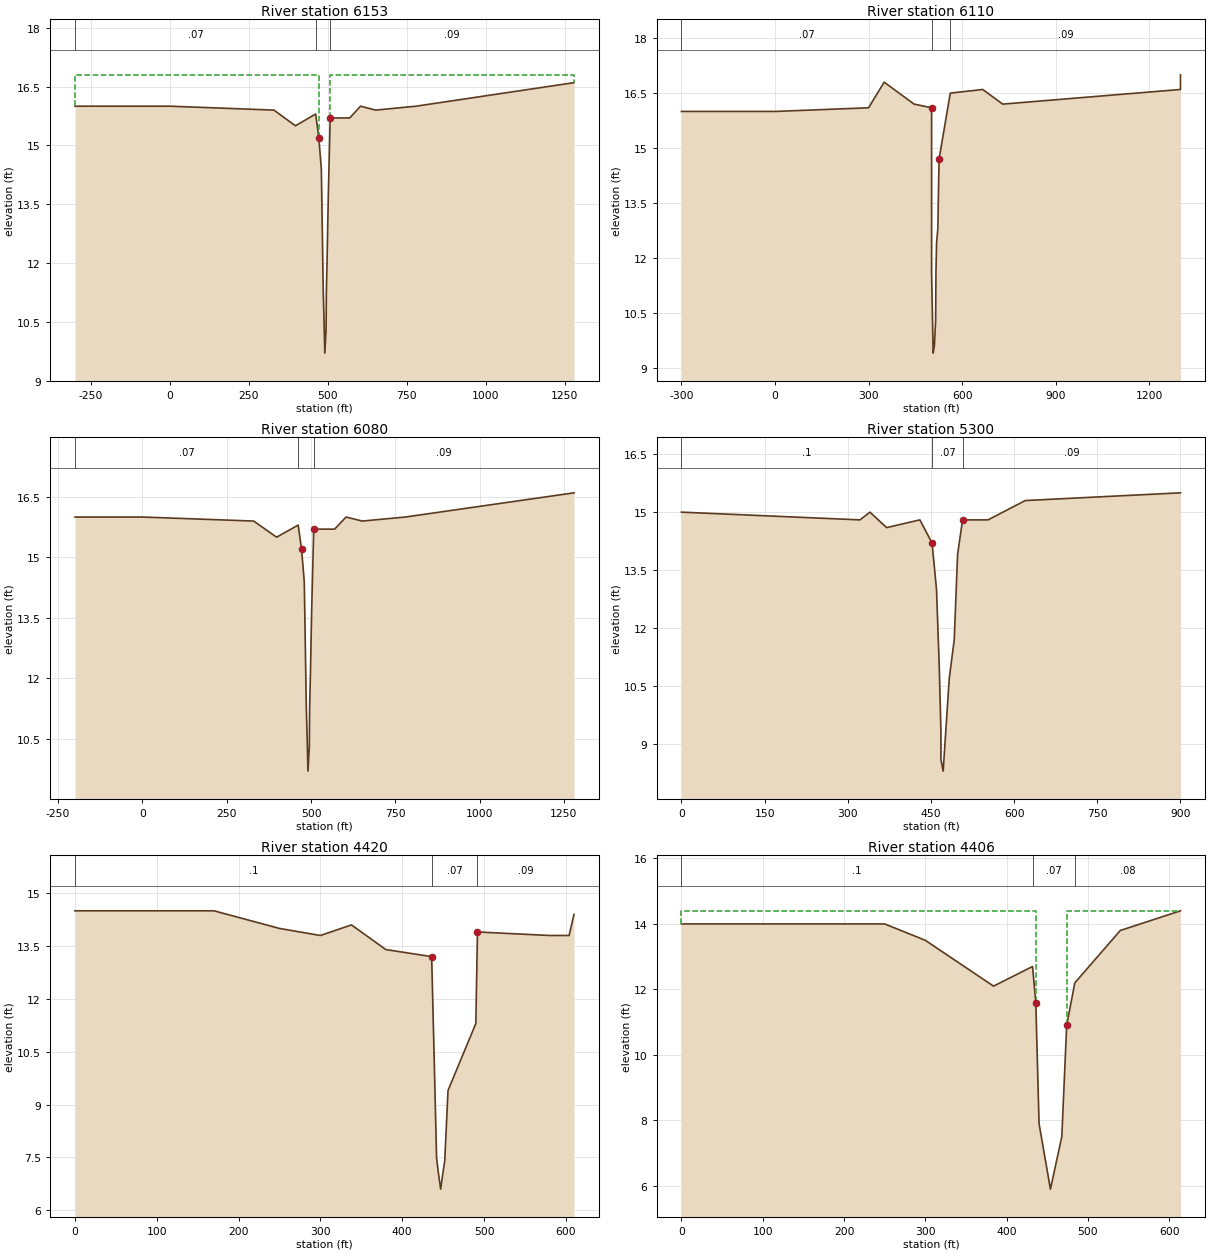
Type RM Length L Ch R =1,6153    ,43,43,43,0,0,0
Node Desc=SCS 851
#Sta/Elev= 21
    -300      16       0      16     330    15.9     398    15.5     462    15.8
     472    15.2     480    14.4     482    13.4     486    11.3     488    10.7
     491     9.7     495    10.3     496    11.3     498      12     502    13.7
     508    15.7     570    15.7     604      16     652    15.9     780      16
    1280    16.6
#Mann=3,1
    -300     .07       1     462     .07       5     508     .09      16
#XS Ineff= 2 , 0
             472    16.8     508            16.8
Bank Sta=472,508
Exp/Cntr=0.3,0.1

Type RM Length L Ch R =1,6110    ,30,30,30,0,0,0
Node Desc=SCS 90
#Sta/Elev= 19
    -300      16       0      16     300    16.1     350    16.8     446    16.2
     502    16.1     502    11.6     507     9.4     511     9.6     515    10.3
     516    11.6     518    12.4     522    12.8     526    14.7     562    16.5
     666    16.6     730    16.2    1300    16.6    1300      17
#Mann=3,1
    -300     .07       1     502     .07       7     562     .09      15
Bank Sta=502,526
Exp/Cntr=0.5,0.3

Type RM Length L Ch R =1,6080    ,780,780,780,0,0,0
Node Desc=SCS 80
#Sta/Elev= 21
    -200      16       0      16     330    15.9     398    15.5     462    15.8
     472    15.2     480    14.4     482    13.4     486    11.3     488    10.7
     491     9.7     495    10.3     496    11.3     498      12     502    13.7
     508    15.7     570    15.7     604      16     652    15.9     780      16
    1280    16.6
#Mann=3,1
    -200     .07       1     462     .07       5     508     .09      16
Bank Sta=472,508
Exp/Cntr=0.3,0.1

Type RM Length L Ch R =1,5300    ,880,880,880,0,0,0
Node Desc=Interp. XSEC
#Sta/Elev= 18
       0      15     322    14.8     340      15     370    14.6     430    14.8
     452    14.2     460      13     465      11     468     9.3     468     8.6
     472     8.3     483    10.7     492    11.7     498    13.9     507    14.8
     553    14.8     620    15.3     900    15.5
#Mann=3,0
       0      .1       0     452     .07       0     507     .09       0
Bank Sta=452,507
Exp/Cntr=0.3,0.1

Type RM Length L Ch R =1,4420    ,14,14,14,0,0,0
Node Desc=SCS 75
#Sta/Elev= 19
       0    14.5     170    14.5     250      14     300    13.8     338    14.1
     380    13.4     436    13.2     439    10.4     442     7.5     444     7.1
     447     6.6     450     7.1     452     7.4     456     9.4     490    11.3
     492    13.9     580    13.8     604    13.8     610    14.4
#Mann=3,1
       0      .1       1     436     .07       7     492     .09      16
Bank Sta=436,492
Exp/Cntr=0.3,0.1

Type RM Length L Ch R =1,4406    ,16,16,16,0,0,0
Node Desc=SCS 702
#Sta/Elev= 13
       0      14     250      14     300    13.5     384    12.1     432    12.7
     436    11.6     440     7.9     454     5.9     468     7.5     474    10.9
     484    12.2     540    13.8     614    14.4
#Mann=3,1
       0      .1       1     432     .07       5     484     .08      11
#XS Ineff= 2 , 0
             436    14.4     474            14.4
Bank Sta=436,474
Exp/Cntr=0.3,0.1

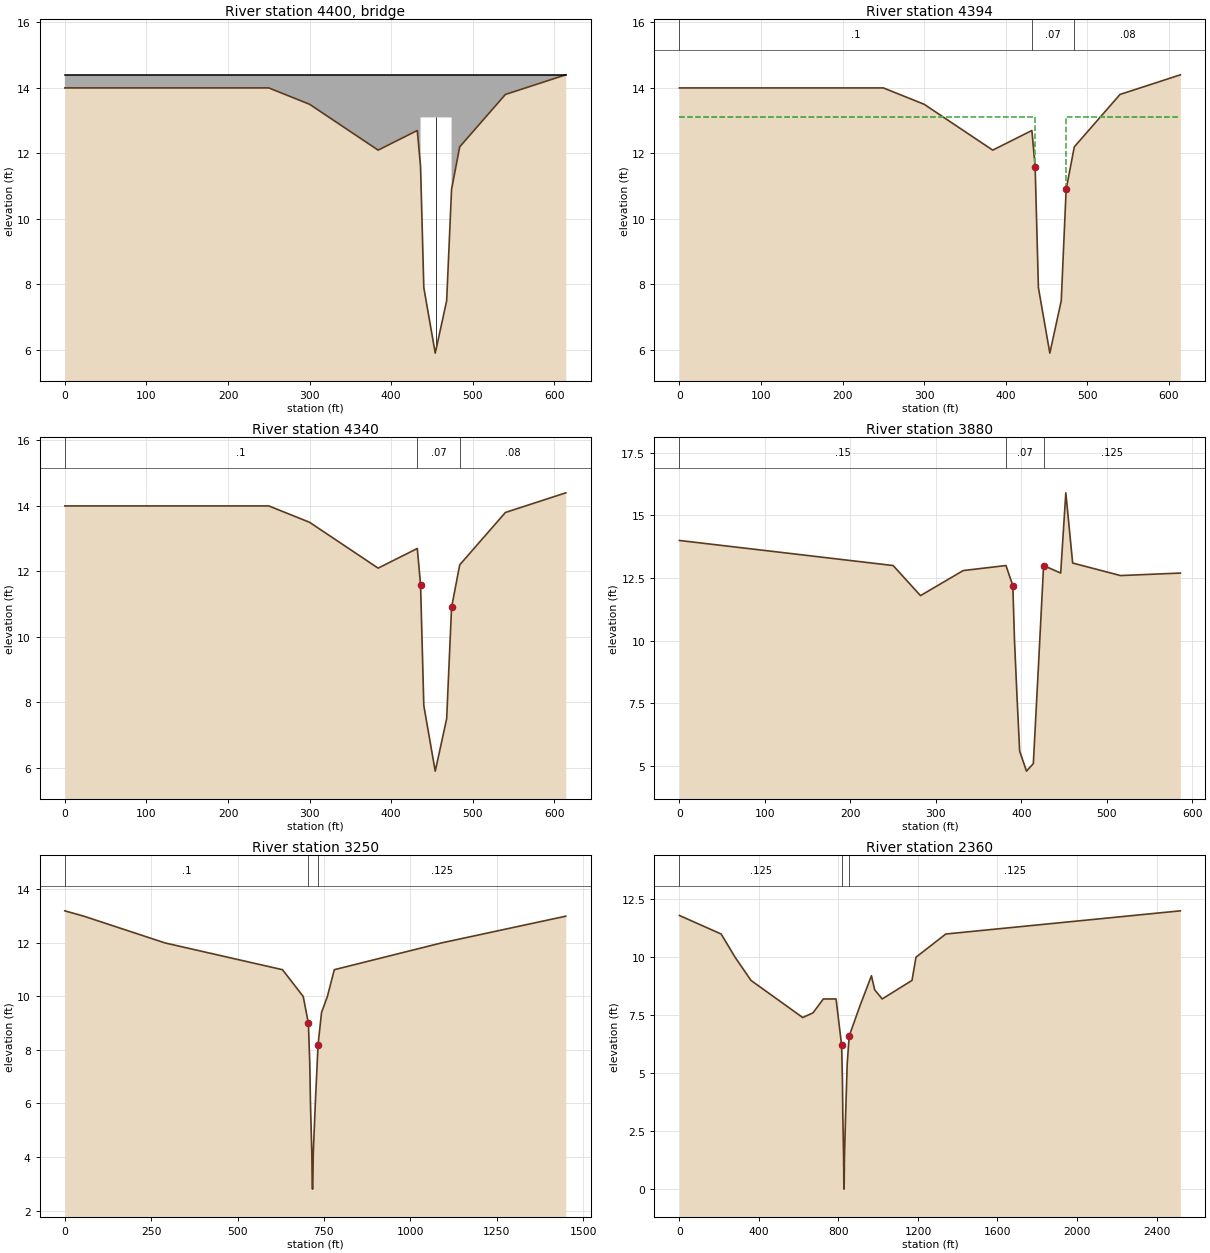
Type RM Length L Ch R =3,4400    ,,,,0,0,0
Node Desc=WOOD BRIDGE
Bridge Culvert--1,0,-1,-1
Deck Dist Width WeirC Skew NumUp NumDn MinLoCord MaxHiCord MaxSubmerge Is_Ogee
0,11.9,2.7,,12,12,14.4,,0.95,0
       0     250     300     384     432     436     436     474     474     484
     540     614
    14.4    14.4    14.4    14.4    14.4    14.4    14.4    14.4    14.4    14.4
    14.4    14.4
      14      14    13.5    12.1    12.7    11.6    13.1    13.1    10.9    12.2
    13.8    14.4
       0     250     300     384     432     436     436     474     474     484
     540     614
    14.4    14.4    14.4    14.4    14.4    14.4    14.4    14.4    14.4    14.4
    14.4    14.4
      14      14    13.5    12.1    12.7    11.6    13.1    13.1    10.9    12.2
    13.8    14.4
Pier Skew, UpSta & Num, DnSta & Num=,455, 2,455, 2, 0, 0
      .1      .1
     5.9    13.1
      .1      .1
     5.9    13.1
BR Coef= 0, 0,-1,1, 0,,,0.8006408,0,2,2,13.1

Type RM Length L Ch R =1,4394    ,54,54,54,0,0,0
Node Desc=SCS 701
#Sta/Elev= 13
       0      14     250      14     300    13.5     384    12.1     432    12.7
     436    11.6     440     7.9     454     5.9     468     7.5     474    10.9
     484    12.2     540    13.8     614    14.4
#Mann=3,1
       0      .1       1     432     .07       5     484     .08      11
#XS Ineff= 2 , 0
             436    13.1     474            13.1
Bank Sta=436,474
Exp/Cntr=0.3,0.1

Type RM Length L Ch R =1,4340    ,460,460,460,0,0,0
Node Desc=SCS 65
#Sta/Elev= 13
       0      14     250      14     300    13.5     384    12.1     432    12.7
     436    11.6     440     7.9     454     5.9     468     7.5     474    10.9
     484    12.2     540    13.8     614    14.4
#Mann=3,1
       0      .1       1     432     .07       5     484     .08      11
Bank Sta=436,474
Exp/Cntr=0.3,0.1

Type RM Length L Ch R =1,3880    ,630,630,630,0,0,0
Node Desc=SCS 2
#Sta/Elev= 18
       0      14     250      13     282    11.8     332    12.8     382      13
     390    12.2     392      10     395     7.7     398     5.6     406     4.8
     414     5.1     420       9     426      13     446    12.7     452    15.9
     460    13.1     516    12.6     586    12.7
#Mann=3,1
       0     .15       1     382     .07       5     426    .125      13
Bank Sta=390,426
Exp/Cntr=0.3,0.1

Type RM Length L Ch R =1,3250    ,890,890,890,0,0,0
Node Desc=SCS 56
#Sta/Elev= 20
       0    13.2      55      13     290      12     630      11     690      10
     705       9     709     7.5     711       6     715     4.1     716       3
     717     2.8     718     3.1     719     4.1     725       6     733     8.2
     743     9.4     760      10     780      11    1090      12    1450      13
#Mann=3,0
       0      .1       0     705     .07       0     733    .125       0
Bank Sta=705,733
Exp/Cntr=0.3,0.1

Type RM Length L Ch R =1,2360    ,13,13,13,0,0,0
Node Desc=SCS 55
#Sta/Elev= 27
       0    11.8     210      11     280      10     360       9     620     7.4
     672     7.6     724     8.2     788     8.2     816     6.2     820     4.7
     822     3.2     826     1.3     827      .3     828       0     829      .3
     830     1.3     836     3.2     844     5.4     854     6.6     908     7.9
     966     9.2     982     8.6    1020     8.2    1170       9    1190      10
    1340      11    2520      12
#Mann=3,0
       0    .125       0     816     .07       0     854    .125       0
#XS Ineff= 2 , 0
             816     6.2     854             6.6
Bank Sta=816,854
Exp/Cntr=0.3,0.1

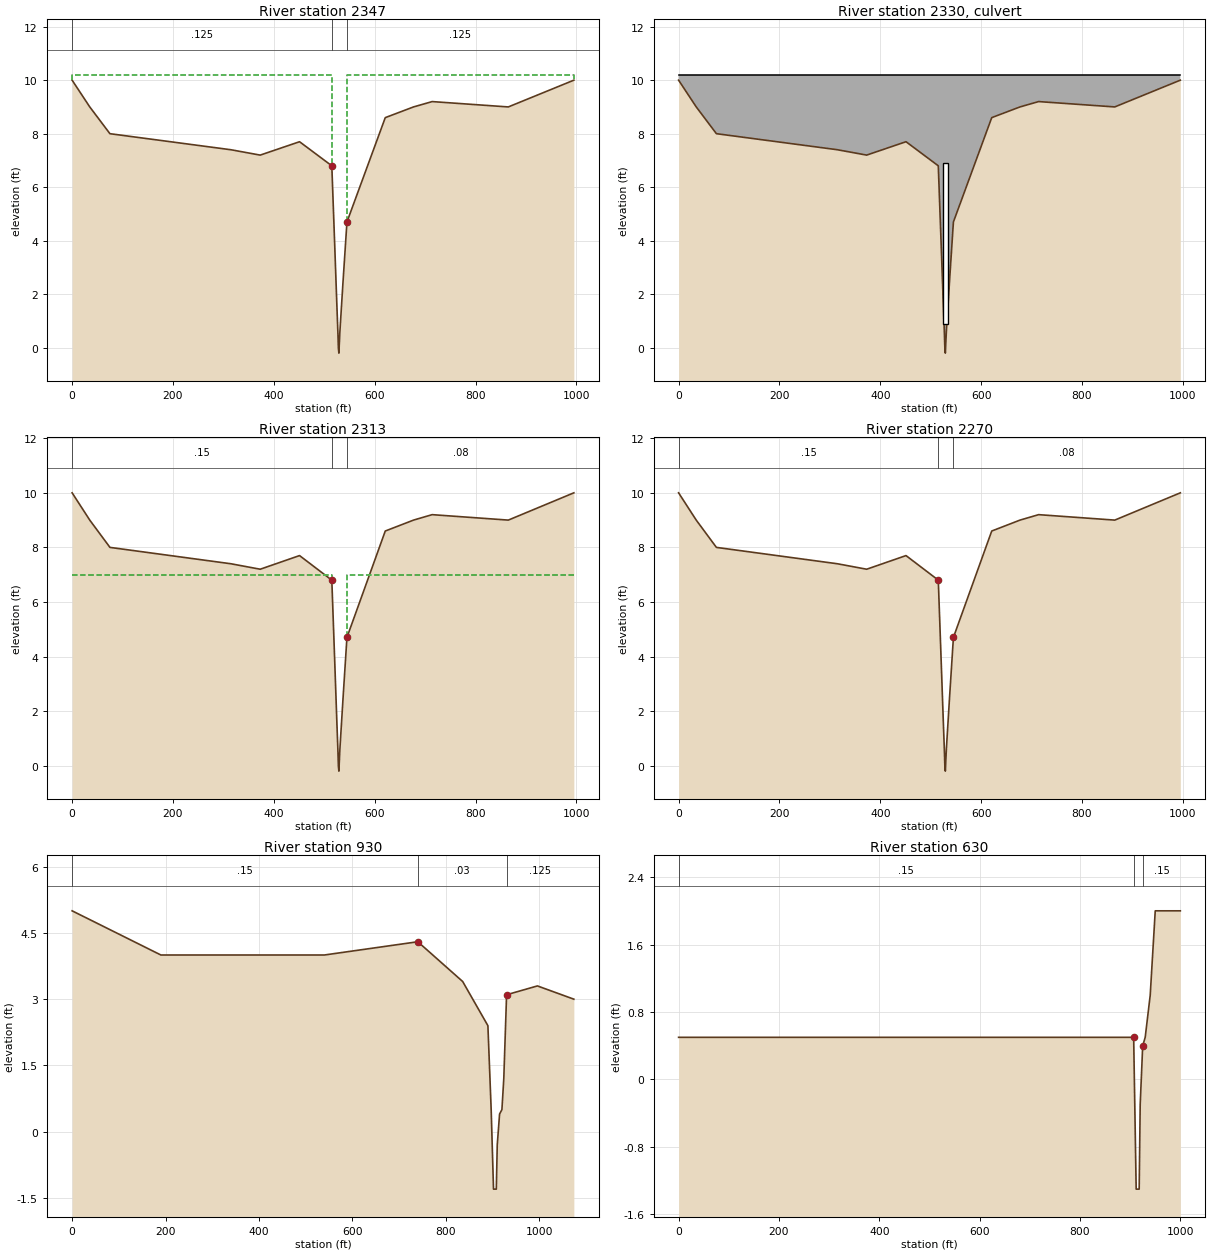
Type RM Length L Ch R =1,2347    ,34,34,34,0,0,0
Node Desc=SCS 502
#Sta/Elev= 21
       0      10      35       9      75       8     315     7.4     373     7.2
     451     7.7     515     6.8     521     3.7     525     1.6     527      .6
     528       0     529     -.2     531      .6     535     1.8     537     2.4
     545     4.7     621     8.6     677       9     714     9.2     865       9
     995      10
#Mann=3,0
       0    .125       0     515     .03       0     545    .125       0
#XS Ineff= 2 , 0
             515    10.2     545            10.2
Bank Sta=515,545
Exp/Cntr=0.3,0.1

Type RM Length L Ch R =2,2330    ,,,,0,0,0
Node Desc=SR 78
Bridge Culvert--1,0,-1,-1
Deck Dist Width WeirC Skew NumUp NumDn MinLoCord MaxHiCord MaxSubmerge Is_Ogee
0,34,2.7,,19,19,,,0.95,0
       0      35      75     315     373     451     515     521     525     525
     535     535     537     545     621     677     714     865     995
    10.2    10.2    10.2    10.2    10.2    10.2    10.2    10.2    10.2    10.2
    10.2    10.2    10.2    10.2    10.2    10.2    10.2    10.2    10.2
      -1      -1      -1      -1      -1      -1      -1      -1      -1      -1
      -1      -1      -1      -1      -1      -1      -1      -1      -1
       0      35      75     315     373     451     515     521     525     525
     535     535     537     545     621     677     714     865     995
    10.2    10.2    10.2    10.2    10.2    10.2    10.2    10.2    10.2    10.2
    10.2    10.2    10.2    10.2    10.2    10.2    10.2    10.2    10.2
      -1      -1      -1      -1      -1      -1      -1      -1      -1      -1
      -1      -1      -1      -1      -1      -1      -1      -1      -1
BR Coef= 0, 0,-1,1, 0,,,0.8,0,0,2,7
Culvert=2,6,10,34,0.012,0.2,0.2,10,1,0.9,530,0.9,530,Culvert #1  , 0

Type RM Length L Ch R =1,2313    ,43,43,43,0,0,0
Node Desc=SCS 501
#Sta/Elev= 21
       0      10      35       9      75       8     315     7.4     373     7.2
     451     7.7     515     6.8     521     3.7     525     1.6     527      .6
     528       0     529     -.2     531      .6     535     1.8     537     2.4
     545     4.7     621     8.6     677       9     714     9.2     865       9
     995      10
#Mann=3,0
       0     .15       0     515     .03       0     545     .08       0
#XS Ineff= 2 , 0
             515       7     545               7
Bank Sta=515,545
Exp/Cntr=0.3,0.1

Type RM Length L Ch R =1,2270    ,1340,1340,1340,0,0,0
Node Desc=SCS 45
#Sta/Elev= 21
       0      10      35       9      75       8     315     7.4     373     7.2
     451     7.7     515     6.8     521     3.7     525     1.6     527      .6
     528       0     529     -.2     531      .6     535     1.8     537     2.4
     545     4.7     621     8.6     677       9     714     9.2     865       9
     995      10
#Mann=3,0
       0     .15       0     515     .03       0     545     .08       0
Bank Sta=515,545
Exp/Cntr=0.3,0.1

Type RM Length L Ch R =1,930     ,300,300,300,0,0,0
Node Desc=SCS 3
#Sta/Elev= 16
       0       5     190       4     540       4     740     4.3     836     3.4
     890     2.4     897      .5     902    -1.3     908    -1.3     910     -.3
     915      .4     920      .5     924     1.2     930     3.1     996     3.3
    1074       3
#Mann=3,0
       0     .15       0     740     .03       0     930    .125       0
Bank Sta=740,930
Exp/Cntr=0.3,0.1

Type RM Length L Ch R =1,630     ,0,0,0,0,0,0
Node Desc=SCS 39
#Sta/Elev= 10
       0      .5     907      .5     912    -1.3     918    -1.3     920     -.3
     925      .4     930      .5     940       1     950       2    1000       2
#Mann=3,0
       0     .15       0     907     .03       0     925     .15       0
Bank Sta=907,925
Exp/Cntr=0.3,0.1